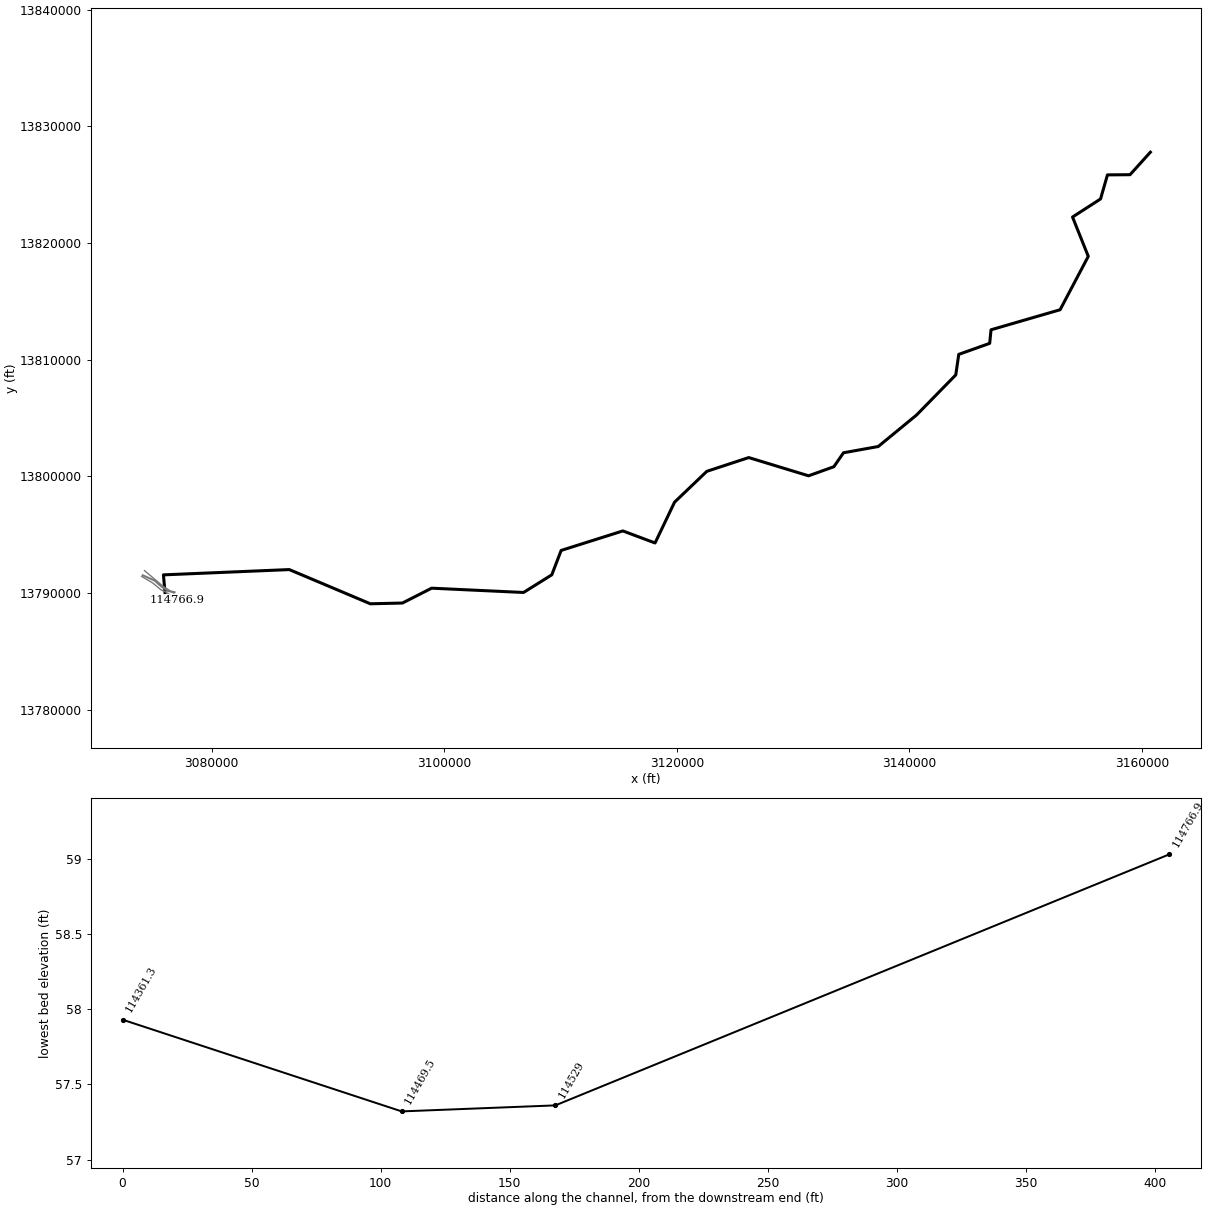
--- C100-00-00.prj (project) ---

Proj Title=C100-00-00
Current Plan=p01
Default Exp/Contr=0.3,0.1
English Units
Geom File=g01
Flow File=f02
Flow File=f01
Flow File=f03
Plan File=p03
Plan File=p01
Plan File=p02
Y Axis Title=Elevation
X Axis Title(PF)=Main Channel Distance
X Axis Title(XS)=Station
BEGIN DESCRIPTION:
UPDATED SV-SQ FOR US BASIN AND GOLF COURSE WPM KMM FEB 2015
Sims Bayou Watershed
Sims Bayou
HCFCD Unit C100-00-00
Flood Hazard Model
10, 2, 1, 0.2% Event
Filename C100-00-00.prj
Prepared by:  Watershed Concepts  Date:
Reviewed by:                      Date:
STATUS FINAL
TROPICAL STORM ALLISON RECOVERY PROJECT
END DESCRIPTION:
DSS Export Rating Curves= 0
DSS Export Rating Curve Sorted= 0
DSS Export Volume Flow Curves= 0
DXF Filename=..\..\2014\14003-00 Sims LOMR Effort\Design & Studies\Original Effective Models\New folder\Original Effective HEC-RAS (Effective CLOMR Downstream)\C100-00-00CLOMR.
DXF OffsetX= 0
DXF OffsetY= 0
DXF ScaleX= 1
DXF ScaleY= 10
Specific Locations Profile Table=SV-SQ SIMS                           , 26
C100-00-00      ,Reach - 1       ,112793.8
C100-00-00      ,Reach - 1       ,108876.3
C100-00-00      ,Reach - 1       ,104687.2
C100-00-00      ,Reach - 1       ,102854.9
C100-00-00      ,Reach - 1       ,97158.7
C100-00-00      ,Reach - 1       ,94709.2
C100-00-00      ,Reach - 1       ,92449.2
C100-00-00      ,Reach - 1       ,90514.2
C100-00-00      ,Reach - 1       ,88689.3
C100-00-00      ,Reach - 1       ,84978.4
C100-00-00      ,Reach - 1       ,81854.3
C100-00-00      ,Reach - 1       ,75449.6
C100-00-00      ,Reach - 1       ,69611.8
C100-00-00      ,Reach - 1       ,62254.1
C100-00-00      ,Reach - 1       ,57376.6
C100-00-00      ,Reach - 1       ,55054.7
C100-00-00      ,Reach - 1       ,48062.3
C100-00-00      ,Reach - 1       ,43139.0
C100-00-00      ,Reach - 1       ,39332.8
C100-00-00      ,Reach - 1       ,27576.8
C100-00-00      ,Reach - 1       ,20732.0
C100-00-00      ,Reach - 1       ,15118.2
C100-00-00      ,Reach - 1       ,13009.0
C100-00-00      ,Reach - 1       ,11812.4
C100-00-00      ,Reach - 1       ,6834.6
C100-00-00      ,Reach - 1       ,344.1
Specific Locations Profile Table=SV SQ                                , 28
C100-00-00      ,Reach - 1       ,112793.8
C100-00-00      ,Reach - 1       ,108876.3
C100-00-00      ,Reach - 1       ,104687.2
C100-00-00      ,Reach - 1       ,102854.9
C100-00-00      ,Reach - 1       ,97158.7
C100-00-00      ,Reach - 1       ,94709.2
C100-00-00      ,Reach - 1       ,92449.2
C100-00-00      ,Reach - 1       ,90514.2
C100-00-00      ,Reach - 1       ,88689.3
C100-00-00      ,Reach - 1       ,84978.4
C100-00-00      ,Reach - 1       ,81854.3
C100-00-00      ,Reach - 1       ,75449.6
C100-00-00      ,Reach - 1       ,69611.8
C100-00-00      ,Reach - 1       ,62254.1
C100-00-00      ,Reach - 1       ,57376.6
C100-00-00      ,Reach - 1       ,55054.7
C100-00-00      ,Reach - 1       ,48062.3
C100-00-00      ,Reach - 1       ,43139.0
C100-00-00      ,Reach - 1       ,39332.8
C100-00-00      ,Reach - 1       ,27576.8
C100-00-00      ,Reach - 1       ,20732.0
C100-00-00      ,Reach - 1       ,15118.2
C100-00-00      ,Reach - 1       ,13009.0
C100-00-00      ,Reach - 1       ,11812.4
C100-00-00      ,Reach - 1       ,6834.6
C100-00-00      ,Reach - 1       ,344.1
C100-00-00      ,Reach - 1       ,103850.6
C100-00-00      ,Reach - 1       ,103023.2

--- C100-00-00.p01 (plan) ---

Plan Title=Effective Multi-Profile 2019
Program Version=4.10
Short Identifier=Eff+PMR MP
Geom File=g01
Flow File=f01
Subcritical Flow
K Sum by GR= 0
Std Step Tol= 0.01
Critical Tol= 0.01
Num of Std Step Trials= 20
Max Error Tol= 0.3
Flow Tol Ratio= 0.001
Split Flow NTrial= 30
Split Flow Tol= 0.02
Split Flow Ratio= 0.02
Log Output Level= 0
Friction Slope Method= 1
Unsteady Friction Slope Method= 2
Unsteady Bridges Friction Slope Method= 1
Parabolic Critical Depth
Global Vel Dist= 0 , 0 , 0
Global Log Level= 0
CheckData=True
Encroach Param=-1 ,0,0, 0
Computation Interval=1HOUR
Output Interval=1HOUR
Run HTab= 0
Run UNet= 0
Run PostProcess= 0
Run WQNet= 0
UNET Theta= 1
UNET Theta Warmup= 1
UNET ZTol= 0.02
UNET ZSATol= 0.1
UNET MxIter= 20
UNET MaxInSteps= 20
UNET DtIC= 0
UNET DtMin= 0
UNET MaxCRTS= 20
UNET WFStab= 2
UNET SFStab= 1
UNET WFX= 1
UNET SFX= 1
UNET DSS MLevel= 4
UNET DZMax Abort= 100
UNET Convert EG Bridges=-1
UNET Use Existing IB Tables=-1
UNET Froude Reduction=False
UNET Froude Limit= 1
UNET Froude Power= 10
UNET Time Slicing=0,0, 5
UNET Junction Losses=0
Instantaneous Interval=1HOUR
Write IC File= 0
IC Time=0,,
Write IC File at Sim End=0
Echo Input=False
Echo Parameters=False
Echo Output=False
Write Detailed= 0
WQ AD Non Conservative
WQ ULTIMATE=-1
WQ Max Comp Step=1HOUR
WQ Output Interval=15MIN
WQ Output Selected Increments= 0
WQ Output face flow=0
WQ Output face velocity=0
WQ Output face area=0
WQ Output face dispersion=0
WQ Output cell volume=0
WQ Output cell surface area=0
WQ Output cell continuity=0
WQ Output cumulative cell continuity=0
WQ Output face conc=0
WQ Output face dconc_dx=0
WQ Output face courant=0
WQ Output face peclet=0
WQ Output face adv mass=0
WQ Output face disp mass=0
WQ Output cell mass=0
WQ Output cell source sink temp=0
WQ Output cell source sink nsm=0
WQ Output MaxMinRange=-1
WQ Daily Max Min Mean=-1
WQ Daily Range=0
WQ Daily Time=0
WQ Create Restart=0
WQ Fixed Restart=0
WQ System Summary=0
WQ Use Fixed Temperature=0
Sorting and Armoring Iterations= 10
XS Update Threshold= 0.02
Hydraulics Update Threshold= 0.02
Energy Slope Method= 1
Volume Change Method= 0
XS Weighting Method= 0
Number of US Weighted Cross Sections= 1
Number of DS Weighted Cross Sections= 1
Upstream XS Weight=0.25
Main XS Weight=0.5
Downstream XS Weight=0.25
Number of DS XS's Weighted with US Boundary= 1
Upstream Boundary Weight= 1
Weight of XSs Associated with US Boundary= 0
Number of US XS's Weighted with DS Boundary= 1
Downstream Boundary Weight= 0.5
Weight of XSs Associated with DS Boundary= 0.5
Sediment Output Level= 4
Mass or Volume Output= 0
Output Increment Type= 1
Profile and TS Output Increment= 10
XS Output Flag= 0
XS Output Increment= 10
Disregard all LS=0
Disregard all Conn=0
Disregard all Breaches=0
Disregard all Pumps=0

--- C100-00-00.p02 (plan) ---

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Plan Title=Effective Floodway 2019
Short Identifier=Eff+PMR FW
Geom File=g01
Flow File=f03

--- C100-00-00.p03 (plan) ---

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Plan Title=SV-SQ RiakMAP 2015
Short Identifier=SV-SQ RiskMAP
Geom File=g01
Flow File=f02

--- C100-00-00.f01 (steady flow) ---

Flow Title=Effective Multi-Profile 2019
Program Version=4.10
Number of Profiles= 6
Profile Names=10PCT_10yr,4PCT_25yr,2PCT_50yr,1PCT_100yr,1PCT_Plus,0.2PCT_500yr
River Rch & RM=C100-00-00,Reach - 1       ,114766.9
     665     851    1026    1217    1460    1786
River Rch & RM=C100-00-00,Reach - 1       ,112793.8
     704     902    1088    1291    1549    1895
River Rch & RM=C100-00-00,Reach - 1       ,112164.9
     745     954    1150    1365    1638    2005
River Rch & RM=C100-00-00,Reach - 1       ,111340
     805    1032    1245    1475    1770    2165
River Rch & RM=C100-00-00,Reach - 1       ,109969.1
     915    1173    1415    1675    2010    2460
River Rch & RM=C100-00-00,Reach - 1       ,109361.1
     970    1243    1500    1770    2124    2605
River Rch & RM=C100-00-00,Reach - 1       ,108688.4
    1032    1321    1593    1888    2266    2766
River Rch & RM=C100-00-00,Reach - 1       ,107447.5
    1165    1497    1810    2150    2580    3115
River Rch & RM=C100-00-00,Reach - 1       ,104687.2
    1520    1976    2410    2890    3468    4050
River Rch & RM=C100-00-00,Reach - 1       ,103850.6
    1650    2153    2632    3154    3785    4401
River Rch & RM=C100-00-00,Reach - 1       ,100247.4
    2025    2646    3240    3900    4680    5500
River Rch & RM=C100-00-00,Reach - 1       ,99056
    2170    2839    3480    4180    5016    5920
River Rch & RM=C100-00-00,Reach - 1       ,97158.7
    2416    3168    3889    4674    5609    6679
River Rch & RM=C100-00-00,Reach - 1       ,97145.1
    2425    3174    3890    4700    5640    6700
River Rch & RM=C100-00-00,Reach - 1       ,94709.2
    4216    5830    7449    9105   10926   13002
River Rch & RM=C100-00-00,Reach - 1       ,92449.2
    5053    6943    8829   10803   12964   15361
River Rch & RM=C100-00-00,Reach - 1       ,90514.2
    5778    7891    9990   12227   14672   17429
River Rch & RM=C100-00-00,Reach - 1       ,88689.3
    6041    8241   10423   12779   15335   18182
River Rch & RM=C100-00-00,Reach - 1       ,87741.1
    6150    8403   10640   13000   15600   18500
River Rch & RM=C100-00-00,Reach - 1       ,85338.7
    6440    8803   11150   13650   16380   19200
River Rch & RM=C100-00-00,Reach - 1       ,84978.4
    6531    8897   11242   13781   16537   19362
River Rch & RM=C100-00-00,Reach - 1       ,81854.3
    7797   10551   13263   16272   19526   22921
River Rch & RM=C100-00-00,Reach - 1       ,80895.12
    7940   10741   13500   16600   19920   23440
River Rch & RM=C100-00-00,Reach - 1       ,75449.6
    8928   12031   15076   18526   22231   26274
River Rch & RM=C100-00-00,Reach - 1       ,69611.8
    9387   12651   15855   19474   23369   27493
River Rch & RM=C100-00-00,Reach - 1       ,68923.8
    9480   12748   15950   19550   23460   27750
River Rch & RM=C100-00-00,Reach - 1       ,62254.1
   10368   13670   16850   20134   24161   30018
River Rch & RM=C100-00-00,Reach - 1       ,59422.5
   11620   15328   18900   22380   26856   30350
River Rch & RM=C100-00-00,Reach - 1       ,57988.3
   12378   16276   20021   23592   28310   30614
River Rch & RM=C100-00-00,Reach - 1       ,43139.0
   14627   19299   23802   27872   33446   35860
River Rch & RM=C100-00-00,Reach - 1       ,39416.9
   14850   19573   24120   28225   33870   36400
River Rch & RM=C100-00-00,Reach - 1       ,34371.0
   15170   20041   24740   28925   34710   37100
River Rch & RM=C100-00-00,Reach - 1       ,28012.6
   15512   20518   25353   29729   35675   37982
River Rch & RM=C100-00-00,Reach - 1       ,27576.8
   15600   20627   25480   29800   35760   38000
River Rch & RM=C100-00-00,Reach - 1       ,22102.6
   16000   21365   26590   30950   37140   38700
River Rch & RM=C100-00-00,Reach - 1       ,20102.8
   16242   21722   27066   31412   37694   38930
River Rch & RM=C100-00-00,Reach - 1       ,14519.4
   19850   26944   33950   39040   46848   51600
River Rch & RM=C100-00-00,Reach - 1       ,14475.5
   19920   27007   34000   39140   46968   51700
River Rch & RM=C100-00-00,Reach - 1       ,13754.5
   20359   27721   35011   40288   48346   53521
River Rch & RM=C100-00-00,Reach - 1       ,11812.4
   20557   28034   35449   40863   49036   54803
River Rch & RM=C100-00-00,Reach - 1       ,7014.6
   21430   29087   36650   42500   51000   57100
River Rch & RM=C100-00-00,Reach - 1       ,5970.7
   21580   29305   36938   42935   51522   57613
Boundary for River Rch & Prof#=C100-00-00,Reach - 1       , 1
Up Type= 0
Dn Type= 3
Dn Slope=0.0001
Boundary for River Rch & Prof#=C100-00-00,Reach - 1       , 2
Up Type= 0
Dn Type= 3
Dn Slope=0.0001
Boundary for River Rch & Prof#=C100-00-00,Reach - 1       , 3
Up Type= 0
Dn Type= 3
Dn Slope=0.0001
Boundary for River Rch & Prof#=C100-00-00,Reach - 1       , 4
Up Type= 0
Dn Type= 3
Dn Slope=0.0001
Observed WS=C100-00-00      ,Reach - 1       ,114529  ,0,,,65.92,
Observed WS=C100-00-00      ,Reach - 1       ,114469.5,0,,,65.9,
Observed WS=C100-00-00      ,Reach - 1       ,114361.3,0,,,65.88,
Observed WS=C100-00-00      ,Reach - 1       ,114219.9,0,,,65.84,
Observed WS=C100-00-00      ,Reach - 1       ,114128.4,0,,,65.81,
Observed WS=C100-00-00      ,Reach - 1       ,114068.9,0,,,65.8,
Observed WS=C100-00-00      ,Reach - 1       ,112164.9,0,,,64.81,
Observed WS=C100-00-00      ,Reach - 1       ,112116.9,0,,,64.74,
Observed WS=C100-00-00      ,Reach - 1       ,111340  ,0,,,64.31,
Observed WS=C100-00-00      ,Reach - 1       ,111228  ,0,,,64.1,
Observed WS=C100-00-00      ,Reach - 1       ,109969.1,0,,,63.66,
Observed WS=C100-00-00      ,Reach - 1       ,109845.3,0,,,63.46,
Observed WS=C100-00-00      ,Reach - 1       ,109361.1,0,,,63.07,
Observed WS=C100-00-00      ,Reach - 1       ,109313.1,0,,,62.77,
Observed WS=C100-00-00      ,Reach - 1       ,108688.4,0,,,62.06,
Observed WS=C100-00-00      ,Reach - 1       ,108614.3,0,,,61.7,
Observed WS=C100-00-00      ,Reach - 1       ,107447.5,0,,,60.7,
Observed WS=C100-00-00      ,Reach - 1       ,107333.3,0,,,60.41,
Observed WS=C100-00-00      ,Reach - 1       ,106702  ,0,,,60.03,
Observed WS=C100-00-00      ,Reach - 1       ,106654  ,0,,,59.94,
Observed WS=C100-00-00      ,Reach - 1       ,103850.6,0,,,58.72,
Observed WS=C100-00-00      ,Reach - 1       ,103829.6,0,,,58.66,
Observed WS=C100-00-00      ,Reach - 1       ,100247.4,0,,,56.52,
Observed WS=C100-00-00      ,Reach - 1       ,100194  ,0,,,56.45,
Observed WS=C100-00-00      ,Reach - 1       ,99056   ,0,,,55.93,
Observed WS=C100-00-00      ,Reach - 1       ,98989.3 ,0,,,55.91,
Observed WS=C100-00-00      ,Reach - 1       ,97158.7 ,0,,,55.44,
Observed WS=C100-00-00      ,Reach - 1       ,97145.1 ,0,,,55.44,
Observed WS=C100-00-00      ,Reach - 1       ,97004.9 ,0,,,55.28,
Observed WS=C100-00-00      ,Reach - 1       ,92449.2 ,0,,,54.58,
Observed WS=C100-00-00      ,Reach - 1       ,92415.4 ,0,,,54.56,
Observed WS=C100-00-00      ,Reach - 1       ,92389.2 ,0,,,54.51,
Observed WS=C100-00-00      ,Reach - 1       ,90514.2 ,0,,,53.77,
Observed WS=C100-00-00      ,Reach - 1       ,90402.6 ,0,,,53.77,
Observed WS=C100-00-00      ,Reach - 1       ,87741.1 ,0,,,53.1,
Observed WS=C100-00-00      ,Reach - 1       ,87683.6 ,0,,,53.01,
Observed WS=C100-00-00      ,Reach - 1       ,85338.7 ,0,,,52.55,
Observed WS=C100-00-00      ,Reach - 1       ,85232.4 ,0,,,52.45,
Observed WS=C100-00-00      ,Reach - 1       ,80895.12,0,,,50.92,
Observed WS=C100-00-00      ,Reach - 1       ,80789.12,0,,,50.1,
Observed WS=C100-00-00      ,Reach - 1       ,80778.13,0,,,50.12,
Observed WS=C100-00-00      ,Reach - 1       ,80765.09,0,,,50.25,
Observed WS=C100-00-00      ,Reach - 1       ,80732.1 ,0,,,50.07,
Observed WS=C100-00-00      ,Reach - 1       ,68923.8 ,0,,,46.28,
Observed WS=C100-00-00      ,Reach - 1       ,68685.3 ,0,,,46.06,
Observed WS=C100-00-00      ,Reach - 1       ,59422.5 ,0,,,41.01,
Observed WS=C100-00-00      ,Reach - 1       ,59305.9 ,0,,,40.69,
Observed WS=C100-00-00      ,Reach - 1       ,58818.1 ,0,,,40.5,
Observed WS=C100-00-00      ,Reach - 1       ,58713.1 ,0,,,40.4,
Observed WS=C100-00-00      ,Reach - 1       ,55054.7 ,0,,,38.42,
Observed WS=C100-00-00      ,Reach - 1       ,54964.9 ,0,,,38.36,
Observed WS=C100-00-00      ,Reach - 1       ,48194.8 ,0,,,36.4,
Observed WS=C100-00-00      ,Reach - 1       ,48062.3 ,0,,,36.23,
Observed WS=C100-00-00      ,Reach - 1       ,39416.9 ,0,,,33.64,
Observed WS=C100-00-00      ,Reach - 1       ,39360.9 ,0,,,33.38,
Observed WS=C100-00-00      ,Reach - 1       ,39332.8 ,0,,,33.4,
Observed WS=C100-00-00      ,Reach - 1       ,39266.8 ,0,,,32.29,
Observed WS=C100-00-00      ,Reach - 1       ,34371.0 ,0,,,30.96,
Observed WS=C100-00-00      ,Reach - 1       ,34309.0 ,0,,,30.63,
Observed WS=C100-00-00      ,Reach - 1       ,28012.6 ,0,,,28.38,
Observed WS=C100-00-00      ,Reach - 1       ,27897.6 ,0,,,27.93,
Observed WS=C100-00-00      ,Reach - 1       ,27576.8 ,0,,,27.78,
Observed WS=C100-00-00      ,Reach - 1       ,27444.8 ,0,,,27.18,
Observed WS=C100-00-00      ,Reach - 1       ,27441.7 ,0,,,27.24,
Observed WS=C100-00-00      ,Reach - 1       ,27420.7 ,0,,,27.14,
Observed WS=C100-00-00      ,Reach - 1       ,22102.6 ,0,,,25.68,
Observed WS=C100-00-00      ,Reach - 1       ,21986.6 ,0,,,25.43,
Observed WS=C100-00-00      ,Reach - 1       ,20400.1 ,0,,,25.04,
Observed WS=C100-00-00      ,Reach - 1       ,20103.1 ,0,,,24.51,
Observed WS=C100-00-00      ,Reach - 1       ,20102.8 ,0,,,24.51,
Observed WS=C100-00-00      ,Reach - 1       ,20079.8 ,0,,,24.43,
Observed WS=C100-00-00      ,Reach - 1       ,18570.5 ,0,,,24.01,
Observed WS=C100-00-00      ,Reach - 1       ,18538.5 ,0,,,23.81,
Observed WS=C100-00-00      ,Reach - 1       ,17913.5 ,0,,,23.59,
Observed WS=C100-00-00      ,Reach - 1       ,17879.5 ,0,,,23.53,
Observed WS=C100-00-00      ,Reach - 1       ,17488.2 ,0,,,23.4,
Observed WS=C100-00-00      ,Reach - 1       ,17456.2 ,0,,,23.33,
Observed WS=C100-00-00      ,Reach - 1       ,14519.4 ,0,,,22.46,
Observed WS=C100-00-00      ,Reach - 1       ,14482.4 ,0,,,22.38,
Observed WS=C100-00-00      ,Reach - 1       ,14475.5 ,0,,,22.34,
Observed WS=C100-00-00      ,Reach - 1       ,14462.0 ,0,,,21.86,
Observed WS=C100-00-00      ,Reach - 1       ,14382.6 ,0,,,21.47,
Observed WS=C100-00-00      ,Reach - 1       ,12676.6 ,0,,,21.17,
Observed WS=C100-00-00      ,Reach - 1       ,12622.2 ,0,,,20.9,
Observed WS=C100-00-00      ,Reach - 1       ,7014.6  ,0,,,19.78,
Observed WS=C100-00-00      ,Reach - 1       ,6834.6  ,0,,,19.55,
Observed WS=C100-00-00      ,Reach - 1       ,6038.8  ,0,,,18.98,
Observed WS=C100-00-00      ,Reach - 1       ,6011.8  ,0,,,18.62,
Observed WS=C100-00-00      ,Reach - 1       ,5970.7  ,0,,,18.33,
Observed WS=C100-00-00      ,Reach - 1       ,5951.5  ,0,,,17.85,
Observed WS=C100-00-00      ,Reach - 1       ,5852.9  ,0,,,17.04,
Observed WS=C100-00-00      ,Reach - 1       ,5792.1  ,0,,,16.24,
Observed WS=C100-00-00      ,Reach - 1       ,5755.1  ,0,,,15.58,
Observed WS=C100-00-00      ,Reach - 1       ,5099.4  ,0,,,15.73,
Observed WS=C100-00-00      ,Reach - 1       ,5071.4  ,0,,,14.39,
Observed WS=C100-00-00      ,Reach - 1       ,4958.6  ,0,,,13.72,
Observed WS=C100-00-00      ,Reach - 1       ,4921.6  ,0,,,13.17,
DSS Import GetInterval= 0
DSS Import GetPeak= 0
DSS Import FillOption= 0

--- C100-00-00.f02 (steady flow) ---

Flow Title=SV-SQ 2015 RiskMAP
Program Version=4.10
Number of Profiles= 8
Profile Names=20% of 1%AEP,40% of 1%AEP,60% of 1%AEP,80% of 1%AEP,100% of 1%AEP,120% of 1%AEP,150% of 1%AEP,200% of 1%AEP
River Rch & RM=C100-00-00,Reach - 1       ,114766.9
  258.14  516.28  774.42 1032.56  1290.7 1548.84 1936.05  2581.4
River Rch & RM=C100-00-00,Reach - 1       ,108876.3
  377.62  755.24 1132.86 1510.48  1888.1 2265.72 2832.15  3776.2
River Rch & RM=C100-00-00,Reach - 1       ,105041.6
  374.88  749.76 1124.64 1499.52  1874.4 2249.28  2811.6  3748.8
River Rch & RM=C100-00-00,Reach - 1       ,104148.9
  678.36 1356.72 2035.08 2713.44  3391.8 4070.16  5087.7  6783.6
River Rch & RM=C100-00-00,Reach - 1       ,103829.6
   678.7  1357.4  2036.1  2714.8  3393.5  4072.2 5090.25    6787
River Rch & RM=C100-00-00,Reach - 1       ,97311.9
   942.4  1884.8  2827.2  3769.6    4712  5654.4    7068    9424
River Rch & RM=C100-00-00,Reach - 1       ,95242.7
 1914.84 3829.68 5744.52 7659.36  9574.211489.04 14361.3 19148.4
River Rch & RM=C100-00-00,Reach - 1       ,92584.1
 2296.08 4592.16 6888.24 9184.32 11480.413776.48 17220.6 22960.8
River Rch & RM=C100-00-00,Reach - 1       ,90692.1
 2614.72 5229.44 7844.1610458.88 13073.615688.32 19610.4 26147.2
River Rch & RM=C100-00-00,Reach - 1       ,89609.4
 2736.64 5473.28 8209.9210946.56 13683.216419.84 20524.8 27366.4
River Rch & RM=C100-00-00,Reach - 1       ,85549.9
 2960.24 5920.48 8880.7211840.96 14801.217761.44 22201.8 29602.4
River Rch & RM=C100-00-00,Reach - 1       ,82878.3
 3499.14 6998.2810497.4213996.56 17495.720994.8426243.55 34991.4
River Rch & RM=C100-00-00,Reach - 1       ,76391.4
 4001.86 8003.7212005.5816007.44 20009.324011.1630013.95 40018.6
River Rch & RM=C100-00-00,Reach - 1       ,69873.4
 4205.04 8410.0812615.1216820.16 21025.225230.24 31537.8 42050.4
River Rch & RM=C100-00-00,Reach - 1       ,62854.9
 4243.76 8487.5212731.2816975.04 21218.825462.56 31828.2 42437.6
River Rch & RM=C100-00-00,Reach - 1       ,57988.3
 4446.64 8893.2813339.9217786.56 22233.226679.84 33349.8 44466.4
River Rch & RM=C100-00-00,Reach - 1       ,55348.5
 4643.44 9286.8813930.3218573.76 23217.227860.64 34825.8 46434.4
River Rch & RM=C100-00-00,Reach - 1       ,48527.1
 4975.76 9951.5214927.2819903.04 24878.829854.56 37318.2 49757.6
River Rch & RM=C100-00-00,Reach - 1       ,43932.0
  5585.1 11170.2 16755.3 22340.4 27925.5 33510.641888.25   55851
River Rch & RM=C100-00-00,Reach - 1       ,39416.9
 5789.0411578.0817367.1223156.16 28945.234734.24 43417.8 57890.4
River Rch & RM=C100-00-00,Reach - 1       ,28012.6
 6147.2412294.4818441.7224588.96 30736.236883.44 46104.3 61472.4
River Rch & RM=C100-00-00,Reach - 1       ,21135.2
 6279.7212559.4418839.1625118.88 31398.637678.32 47097.9 62797.2
River Rch & RM=C100-00-00,Reach - 1       ,16016.3
 6456.9812913.9619370.9425827.92 32284.938741.8848427.35 64569.8
River Rch & RM=C100-00-00,Reach - 1       ,13754.5
 8156.6616313.3224469.9832626.64 40783.348939.9661174.95 81566.6
River Rch & RM=C100-00-00,Reach - 1       ,12676.6
 8259.9816519.9624779.9433039.92 41299.949559.8861949.85 82599.8
River Rch & RM=C100-00-00,Reach - 1       ,7014.6
 8513.1417026.2825539.4234052.56 42565.751078.8463848.55 85131.4
River Rch & RM=C100-00-00,Reach - 1       ,1295.0
 8669.6617339.3226008.9834678.64 43348.352017.9665022.45 86696.6
Boundary for River Rch & Prof#=C100-00-00,Reach - 1       , 1
Up Type= 0
Dn Type= 3
Dn Slope=0.0001
Boundary for River Rch & Prof#=C100-00-00,Reach - 1       , 2
Up Type= 0
Dn Type= 3
Dn Slope=0.0001
Boundary for River Rch & Prof#=C100-00-00,Reach - 1       , 3
Up Type= 0
Dn Type= 3
Dn Slope=0.0001
Boundary for River Rch & Prof#=C100-00-00,Reach - 1       , 4
Up Type= 0
Dn Type= 3
Dn Slope=0.0001
Observed WS=C100-00-00      ,Reach - 1       ,114529  ,0,,,65.92,,,,,
Observed WS=C100-00-00      ,Reach - 1       ,114469.5,0,,,65.9,,,,,
Observed WS=C100-00-00      ,Reach - 1       ,114361.3,0,,,65.88,,,,,
Observed WS=C100-00-00      ,Reach - 1       ,114219.9,0,,,65.84,,,,,
Observed WS=C100-00-00      ,Reach - 1       ,114128.4,0,,,65.81,,,,,
Observed WS=C100-00-00      ,Reach - 1       ,114068.9,0,,,65.8,,,,,
Observed WS=C100-00-00      ,Reach - 1       ,112164.9,0,,,64.81,,,,,
Observed WS=C100-00-00      ,Reach - 1       ,112116.9,0,,,64.74,,,,,
Observed WS=C100-00-00      ,Reach - 1       ,111340  ,0,,,64.31,,,,,
Observed WS=C100-00-00      ,Reach - 1       ,111228  ,0,,,64.1,,,,,
Observed WS=C100-00-00      ,Reach - 1       ,109969.1,0,,,63.66,,,,,
Observed WS=C100-00-00      ,Reach - 1       ,109845.3,0,,,63.46,,,,,
Observed WS=C100-00-00      ,Reach - 1       ,109361.1,0,,,63.07,,,,,
Observed WS=C100-00-00      ,Reach - 1       ,109313.1,0,,,62.77,,,,,
Observed WS=C100-00-00      ,Reach - 1       ,108688.4,0,,,62.06,,,,,
Observed WS=C100-00-00      ,Reach - 1       ,108614.3,0,,,61.7,,,,,
Observed WS=C100-00-00      ,Reach - 1       ,107447.5,0,,,60.7,,,,,
Observed WS=C100-00-00      ,Reach - 1       ,107333.3,0,,,60.41,,,,,
Observed WS=C100-00-00      ,Reach - 1       ,106702  ,0,,,60.03,,,,,
Observed WS=C100-00-00      ,Reach - 1       ,106654  ,0,,,59.94,,,,,
Observed WS=C100-00-00      ,Reach - 1       ,103850.6,0,,,58.72,,,,,
Observed WS=C100-00-00      ,Reach - 1       ,103829.6,0,,,58.66,,,,,
Observed WS=C100-00-00      ,Reach - 1       ,100247.4,0,,,56.52,,,,,
Observed WS=C100-00-00      ,Reach - 1       ,100194  ,0,,,56.45,,,,,
Observed WS=C100-00-00      ,Reach - 1       ,99056   ,0,,,55.93,,,,,
Observed WS=C100-00-00      ,Reach - 1       ,98989.3 ,0,,,55.91,,,,,
Observed WS=C100-00-00      ,Reach - 1       ,97158.7 ,0,,,55.44,,,,,
Observed WS=C100-00-00      ,Reach - 1       ,97145.1 ,0,,,55.44,,,,,
Observed WS=C100-00-00      ,Reach - 1       ,97004.9 ,0,,,55.28,,,,,
Observed WS=C100-00-00      ,Reach - 1       ,92449.2 ,0,,,54.58,,,,,
Observed WS=C100-00-00      ,Reach - 1       ,92415.4 ,0,,,54.56,,,,,
Observed WS=C100-00-00      ,Reach - 1       ,92389.2 ,0,,,54.51,,,,,
Observed WS=C100-00-00      ,Reach - 1       ,90514.2 ,0,,,53.77,,,,,
Observed WS=C100-00-00      ,Reach - 1       ,90402.6 ,0,,,53.77,,,,,
Observed WS=C100-00-00      ,Reach - 1       ,87741.1 ,0,,,53.1,,,,,
Observed WS=C100-00-00      ,Reach - 1       ,87683.6 ,0,,,53.01,,,,,
Observed WS=C100-00-00      ,Reach - 1       ,85338.7 ,0,,,52.55,,,,,
Observed WS=C100-00-00      ,Reach - 1       ,85232.4 ,0,,,52.45,,,,,
Observed WS=C100-00-00      ,Reach - 1       ,80895.12,0,,,50.92,,,,,
Observed WS=C100-00-00      ,Reach - 1       ,80789.12,0,,,50.1,,,,,
Observed WS=C100-00-00      ,Reach - 1       ,80778.13,0,,,50.12,,,,,
Observed WS=C100-00-00      ,Reach - 1       ,80765.09,0,,,50.25,,,,,
Observed WS=C100-00-00      ,Reach - 1       ,80732.1 ,0,,,50.07,,,,,
Observed WS=C100-00-00      ,Reach - 1       ,68923.8 ,0,,,46.28,,,,,
Observed WS=C100-00-00      ,Reach - 1       ,68685.3 ,0,,,46.06,,,,,
Observed WS=C100-00-00      ,Reach - 1       ,59422.5 ,0,,,41.01,,,,,
Observed WS=C100-00-00      ,Reach - 1       ,59305.9 ,0,,,40.69,,,,,
Observed WS=C100-00-00      ,Reach - 1       ,58818.1 ,0,,,40.5,,,,,
Observed WS=C100-00-00      ,Reach - 1       ,58713.1 ,0,,,40.4,,,,,
Observed WS=C100-00-00      ,Reach - 1       ,55054.7 ,0,,,38.42,,,,,
Observed WS=C100-00-00      ,Reach - 1       ,54964.9 ,0,,,38.36,,,,,
Observed WS=C100-00-00      ,Reach - 1       ,48194.8 ,0,,,36.4,,,,,
Observed WS=C100-00-00      ,Reach - 1       ,48062.3 ,0,,,36.23,,,,,
Observed WS=C100-00-00      ,Reach - 1       ,39416.9 ,0,,,33.64,,,,,
Observed WS=C100-00-00      ,Reach - 1       ,39360.9 ,0,,,33.38,,,,,
Observed WS=C100-00-00      ,Reach - 1       ,39332.8 ,0,,,33.4,,,,,
Observed WS=C100-00-00      ,Reach - 1       ,39266.8 ,0,,,32.29,,,,,
Observed WS=C100-00-00      ,Reach - 1       ,34371.0 ,0,,,30.96,,,,,
Observed WS=C100-00-00      ,Reach - 1       ,34309.0 ,0,,,30.63,,,,,
Observed WS=C100-00-00      ,Reach - 1       ,28012.6 ,0,,,28.38,,,,,
Observed WS=C100-00-00      ,Reach - 1       ,27897.6 ,0,,,27.93,,,,,
Observed WS=C100-00-00      ,Reach - 1       ,27576.8 ,0,,,27.78,,,,,
Observed WS=C100-00-00      ,Reach - 1       ,27444.8 ,0,,,27.18,,,,,
Observed WS=C100-00-00      ,Reach - 1       ,27441.7 ,0,,,27.24,,,,,
Observed WS=C100-00-00      ,Reach - 1       ,27420.7 ,0,,,27.14,,,,,
Observed WS=C100-00-00      ,Reach - 1       ,22102.6 ,0,,,25.68,,,,,
Observed WS=C100-00-00      ,Reach - 1       ,21986.6 ,0,,,25.43,,,,,
Observed WS=C100-00-00      ,Reach - 1       ,20400.1 ,0,,,25.04,,,,,
Observed WS=C100-00-00      ,Reach - 1       ,20103.1 ,0,,,24.51,,,,,
Observed WS=C100-00-00      ,Reach - 1       ,20102.8 ,0,,,24.51,,,,,
Observed WS=C100-00-00      ,Reach - 1       ,20079.8 ,0,,,24.43,,,,,
Observed WS=C100-00-00      ,Reach - 1       ,18570.5 ,0,,,24.01,,,,,
Observed WS=C100-00-00      ,Reach - 1       ,18538.5 ,0,,,23.81,,,,,
Observed WS=C100-00-00      ,Reach - 1       ,17913.5 ,0,,,23.59,,,,,
Observed WS=C100-00-00      ,Reach - 1       ,17879.5 ,0,,,23.53,,,,,
Observed WS=C100-00-00      ,Reach - 1       ,17488.2 ,0,,,23.4,,,,,
Observed WS=C100-00-00      ,Reach - 1       ,17456.2 ,0,,,23.33,,,,,
Observed WS=C100-00-00      ,Reach - 1       ,14519.4 ,0,,,22.46,,,,,
Observed WS=C100-00-00      ,Reach - 1       ,14482.4 ,0,,,22.38,,,,,
Observed WS=C100-00-00      ,Reach - 1       ,14475.5 ,0,,,22.34,,,,,
Observed WS=C100-00-00      ,Reach - 1       ,14462.0 ,0,,,21.86,,,,,
Observed WS=C100-00-00      ,Reach - 1       ,14382.6 ,0,,,21.47,,,,,
Observed WS=C100-00-00      ,Reach - 1       ,12676.6 ,0,,,21.17,,,,,
Observed WS=C100-00-00      ,Reach - 1       ,12622.2 ,0,,,20.9,,,,,
Observed WS=C100-00-00      ,Reach - 1       ,7014.6  ,0,,,19.78,,,,,
Observed WS=C100-00-00      ,Reach - 1       ,6834.6  ,0,,,19.55,,,,,
Observed WS=C100-00-00      ,Reach - 1       ,6038.8  ,0,,,18.98,,,,,
Observed WS=C100-00-00      ,Reach - 1       ,6011.8  ,0,,,18.62,,,,,
Observed WS=C100-00-00      ,Reach - 1       ,5970.7  ,0,,,18.33,,,,,
Observed WS=C100-00-00      ,Reach - 1       ,5951.5  ,0,,,17.85,,,,,
Observed WS=C100-00-00      ,Reach - 1       ,5852.9  ,0,,,17.04,,,,,
Observed WS=C100-00-00      ,Reach - 1       ,5792.1  ,0,,,16.24,,,,,
Observed WS=C100-00-00      ,Reach - 1       ,5755.1  ,0,,,15.58,,,,,
Observed WS=C100-00-00      ,Reach - 1       ,5099.4  ,0,,,15.73,,,,,
Observed WS=C100-00-00      ,Reach - 1       ,5071.4  ,0,,,14.39,,,,,
Observed WS=C100-00-00      ,Reach - 1       ,4958.6  ,0,,,13.72,,,,,
Observed WS=C100-00-00      ,Reach - 1       ,4921.6  ,0,,,13.17,,,,,
DSS Import GetInterval= 0
DSS Import GetPeak= 0
DSS Import FillOption= 0

--- C100-00-00.f03 (steady flow) ---

Flow Title=Effective Floodway 2019
Program Version=4.10
Number of Profiles= 2
Profile Names=1PCT_100yr,Floodway
River Rch & RM=C100-00-00,Reach - 1       ,114766.9
    1217    1217
River Rch & RM=C100-00-00,Reach - 1       ,112793.8
    1291    1291
River Rch & RM=C100-00-00,Reach - 1       ,112164.9
    1365    1365
River Rch & RM=C100-00-00,Reach - 1       ,111340
    1475    1475
River Rch & RM=C100-00-00,Reach - 1       ,109969.1
    1675    1675
River Rch & RM=C100-00-00,Reach - 1       ,109361.1
    1770    1770
River Rch & RM=C100-00-00,Reach - 1       ,108688.4
    1888    1888
River Rch & RM=C100-00-00,Reach - 1       ,107447.5
    2150    2150
River Rch & RM=C100-00-00,Reach - 1       ,104687.2
    2890    2890
River Rch & RM=C100-00-00,Reach - 1       ,103850.6
    3154    3154
River Rch & RM=C100-00-00,Reach - 1       ,100247.4
    3900    3900
River Rch & RM=C100-00-00,Reach - 1       ,99056
    4180    4180
River Rch & RM=C100-00-00,Reach - 1       ,97158.7
    4674    4674
River Rch & RM=C100-00-00,Reach - 1       ,97145.1
    4700    4700
River Rch & RM=C100-00-00,Reach - 1       ,94709.2
    9105    9105
River Rch & RM=C100-00-00,Reach - 1       ,92449.2
   10803   10803
River Rch & RM=C100-00-00,Reach - 1       ,90514.2
   12227   12227
River Rch & RM=C100-00-00,Reach - 1       ,88689.3
   12779   12779
River Rch & RM=C100-00-00,Reach - 1       ,87741.1
   13000   13000
River Rch & RM=C100-00-00,Reach - 1       ,85338.7
   13650   13650
River Rch & RM=C100-00-00,Reach - 1       ,84978.4
   13781   13781
River Rch & RM=C100-00-00,Reach - 1       ,81854.3
   16272   16272
River Rch & RM=C100-00-00,Reach - 1       ,80895.12
   16600   16600
River Rch & RM=C100-00-00,Reach - 1       ,75449.6
   18526   18526
River Rch & RM=C100-00-00,Reach - 1       ,69611.8
   19474   19474
River Rch & RM=C100-00-00,Reach - 1       ,68923.8
   19550   19550
River Rch & RM=C100-00-00,Reach - 1       ,62254.1
   20134   20134
River Rch & RM=C100-00-00,Reach - 1       ,59422.5
   22380   22380
River Rch & RM=C100-00-00,Reach - 1       ,57988.3
   23592   23592
River Rch & RM=C100-00-00,Reach - 1       ,43139.0
   27872   27872
River Rch & RM=C100-00-00,Reach - 1       ,39416.9
   28225   28225
River Rch & RM=C100-00-00,Reach - 1       ,34371.0
   28925   28925
River Rch & RM=C100-00-00,Reach - 1       ,28012.6
   29729   29729
River Rch & RM=C100-00-00,Reach - 1       ,27576.8
   29800   29800
River Rch & RM=C100-00-00,Reach - 1       ,22102.6
   30950   30950
River Rch & RM=C100-00-00,Reach - 1       ,20102.8
   31412   31412
River Rch & RM=C100-00-00,Reach - 1       ,14519.4
   39040   39040
River Rch & RM=C100-00-00,Reach - 1       ,14475.5
   39140   39140
River Rch & RM=C100-00-00,Reach - 1       ,13754.5
   40288   40288
River Rch & RM=C100-00-00,Reach - 1       ,11812.4
   40863   40863
River Rch & RM=C100-00-00,Reach - 1       ,7014.6
   42500   42500
River Rch & RM=C100-00-00,Reach - 1       ,5970.7
   42935   42935
Boundary for River Rch & Prof#=C100-00-00,Reach - 1       , 1
Up Type= 0
Dn Type= 3
Dn Slope=0.0001
Boundary for River Rch & Prof#=C100-00-00,Reach - 1       , 2
Up Type= 0
Dn Type= 3
Dn Slope=0.0001
DSS Import GetInterval= 0
DSS Import GetPeak= 0
DSS Import FillOption= 0

--- C100-00-00.g01 (geometry) ---

Geom Title=C100-00-00 2019
Program Version=4.10

River Reach=C100-00-00      ,Reach - 1
Reach XY= 30
     3075990.662     13790022.26     3075852.641     13791573.04
     3086676.426     13792025.73     3093643.266     13789095.47
     3096401.858     13789158.94     3098916.213     13790431.98
     3106818.939     13790064.54     3109247.325     13791576.26
     3110052.446     13793666.11     3115358.436     13795337.29
     3118127.533      13794304.3      3119805.05     13797802.56
     3122580.658     13800443.62     3126183.089     13801622.01
     3131326.318     13800059.51      3133503.17     13800838.29
      3134329.49      13802031.9      3137320.61     13802570.15
     3140611.259     13805265.98      3143984.66     13808701.65
      3144241.75       13810463.        3146901.       13811407.
      3147016.75       13812568.      3152956.25       13814286.
      3155379.25       13818861.       3154024.5       13822229.
      3156432.75       13823776.        3157028.       13825840.
      3158969.99      13825855.6      3160718.25       13827785.

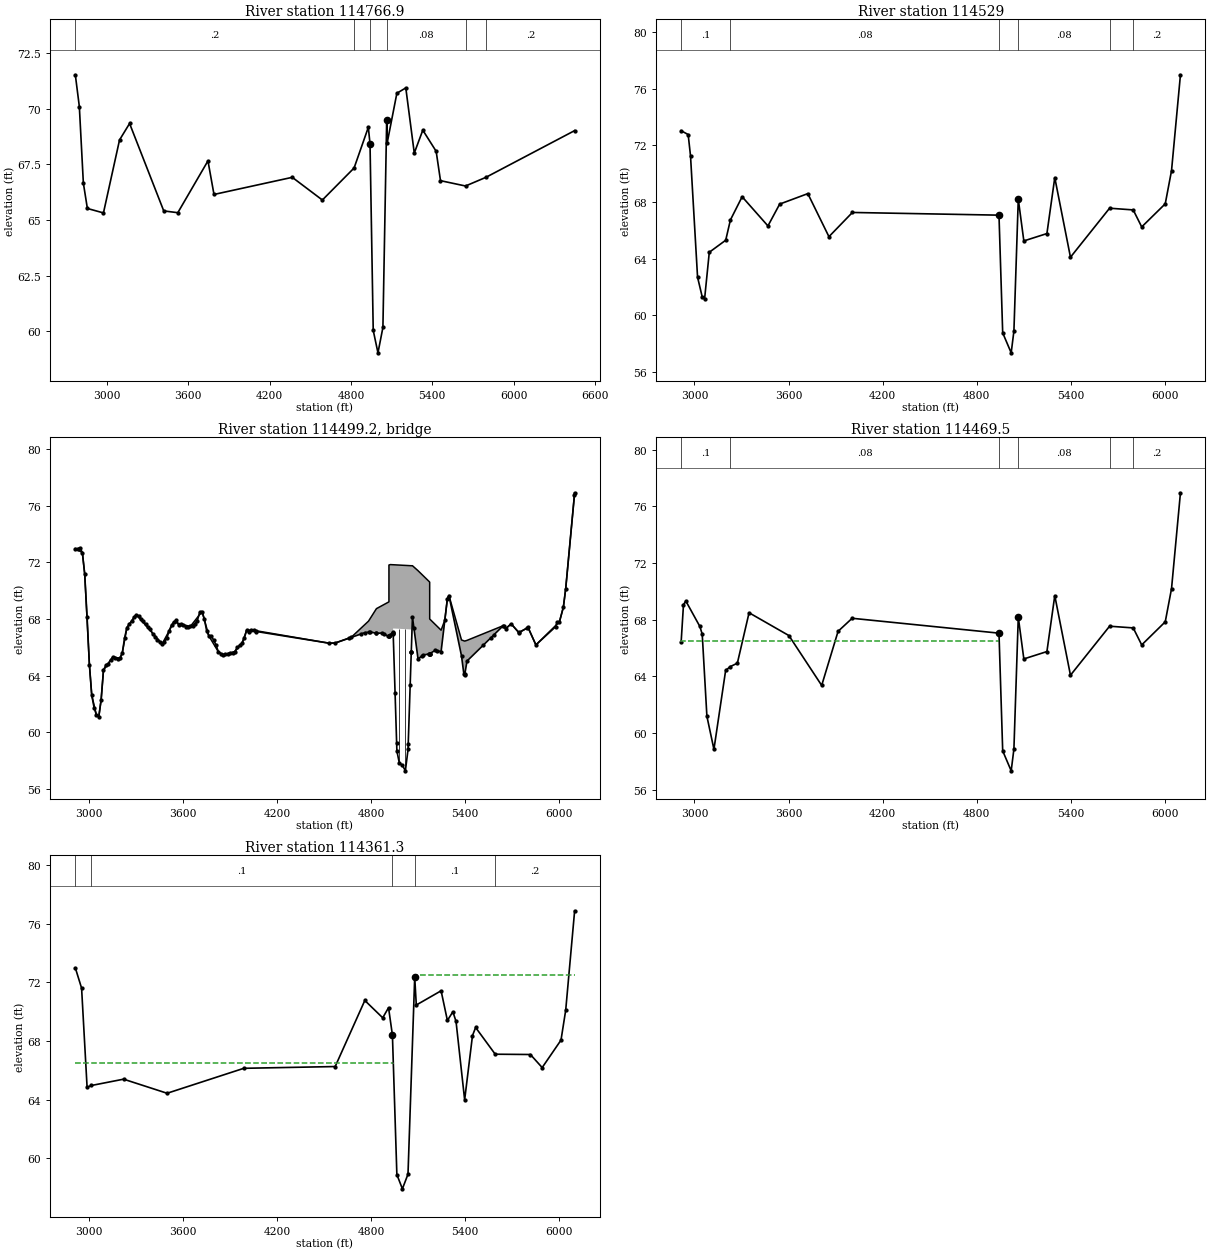
Type RM Length L Ch R = 1 ,114766.9,261.47,237.92,230.93
BEGIN DESCRIPTION:
Cross Section 116857.0 - Interpolated
END DESCRIPTION:
XS GIS Cut Line= 5
      3073976.23     13791441.51      3074945.78     13790867.69
      3075651.51     13790280.68      3076007.67     13790135.58
      3077035.94     13789413.82
#Sta/Elev= 30
  2765.7   71.53 2795.37    70.1 2825.04   66.66  2854.7   65.52 2973.37   65.32
 3092.05    68.6 3166.22   69.34 3418.39   65.41 3522.23   65.33 3744.74   67.66
 3789.24   66.15 4366.97   66.92  4589.1    65.9  4823.4   67.34  4928.5   69.17
 4940.94   68.42 4964.58   60.04 4999.54   59.03 5036.04   60.17 5063.91   69.48
    5068   68.48  5139.1    70.7    5205   70.94  5267.6   68.01  5330.5   69.04
  5429.1   68.09  5461.1   66.77  5645.8   66.53  5796.4   66.92  6451.2   69.02
#Mann= 6 ,-1 , 0
  2765.7      .2       0  4823.4     .08       0 4940.94    .035       0
 5063.91     .08       0  5645.8      .1       0  5796.4      .2       0
#XS Ineff= 2 , 0
       0  4809.8   67.12               0
Permanent Ineff=
       F       F
Bank Sta=4940.94,5063.91
XS Rating Curve= 0 ,0
Exp/Cntr=0.5,0.3

Type RM Length L Ch R = 1 ,114529  ,60.28,59.53,50.8
BEGIN DESCRIPTION:
Upstream Section of Bridge/Culvert/Weir
END DESCRIPTION:
XS GIS Cut Line= 6
      3074061.23     13791514.94       3075111.4     13791044.03
       3075454.4     13790725.82      3075840.63     13790430.73
      3076267.27     13790150.19      3076826.95     13790060.94
#Sta/Elev= 30
  2915.1   73.04 2959.96   72.77 2974.91   71.26 3019.77    62.7 3049.67    61.3
 3064.63   61.17 3094.53   64.46  3199.2   65.31 3229.11   66.74 3303.87   68.38
 3468.35   66.32 3543.11   67.86 3722.54    68.6 3857.12   65.56 4006.64   67.27
 4940.94   67.08 4964.58   58.77 5018.71   57.36 5036.04    58.9 5063.91   68.21
 5099.33   65.26  5246.4   65.78  5296.5   69.73  5396.5   64.11  5645.8   67.57
  5796.4   67.45  5850.6   66.25  6000.6   67.88  6040.6   70.22  6097.5   76.99
#Mann= 6 ,-1 , 0
  2915.1      .1       0 3229.11     .08       0 4940.94    .035       0
 5063.91     .08       0  5645.8      .1       0  5796.4      .2       0
#XS Ineff= 2 , 0
       0    4940   66.49    5064       0   68.14
Permanent Ineff=
       F       F
Bank Sta=4940.94,5063.91
XS Rating Curve= 0 ,0
Exp/Cntr=0.5,0.3

Type RM Length L Ch R = 3 ,114499.2,,,
BEGIN DESCRIPTION:
FRONTAGE ROAD BELTWAY SOUTH Skew Angle 40 Degrees
Structure ID: C00-57
END DESCRIPTION:
Bridge Culvert--1,0,-1,-1, 0
Deck Dist Width WeirC Skew NumUp NumDn MinLoCord MaxHiCord MaxSubmerge Is_Ogee
10,38.4,2.6,0, 60, 60, , , 0.95, 0, 1,1,,
  2915.1 2959.96 2974.91 3004.82 3019.77 3049.67 3064.63 3079.58 3094.53 3154.34
  3199.2 3214.15 3244.06 3303.87 3468.35 3543.11 3647.78 3722.54  3767.4 3827.21
 3857.12 3931.88 3976.74 4006.64 4036.55  4533.9  4571.3  4673.9  4783.9 4834.22
 4913.89    4914  4923.3 4940.85 4940.94 5056.25 5056.36 5063.91 5099.33  5171.6
  5173.6 5173.71  5246.4  5270.1  5286.5  5296.5  5376.5  5391.5  5396.5  5411.5
  5642.8  5657.8  5692.8  5742.8  5800.6  5850.6  6000.6  6025.6  6040.6  6097.5
   72.96   72.69   71.18   64.78   62.62   61.22   61.09   62.29   64.38   65.31
   65.23   65.58   67.39    68.3   66.24   67.78   67.47   68.52   66.78   65.67
   65.48    65.7   66.27   67.19   67.23   66.29   66.31   66.71   67.85   68.73
   69.21   71.81   71.84   71.83   71.83   71.76   71.76   71.76   71.41   70.63
    70.6      68   67.21   67.92   69.45   69.66   66.52   66.46   66.44   66.49
   67.53   67.31   67.66   67.03    67.4   66.17    67.8   68.83   70.14   76.91
      55      55      55      55      55      55      55      55      55      55
      55      55      55      55      55      55      55      55      55      55
      55      55      55      55      55      55    66.3    66.7   67.06   66.99
   66.81   66.81    66.9   67.03   67.33   67.26    65.7   68.13   65.18   65.54
   65.55   65.55    65.7   67.91   69.44   69.65   65.39   64.11   64.03   65.03
   67.53   67.31   67.66   67.03    67.4   66.17    67.8   68.83   70.14   76.91
  2915.1 2930.03 2944.96 2989.75 3034.54 3049.47 3079.33 3124.12 3139.05 3153.98
 3198.77  3213.7 3273.43 3318.22 3348.08 3392.87 3467.52  3557.1 3601.89 3721.33
 3751.19 3810.91 3840.77  3855.7 3885.57  3900.5 3915.43 4005.01  4533.9  4571.3
  4673.9 4834.22 4913.89    4914  4923.3 4940.85 4940.94 5056.25 5056.36 5063.91
 5099.33  5171.6  5173.6 5173.71  5246.4  5270.1  5286.5  5296.5  5376.5  5396.5
  5411.5  5642.8  5692.8  5742.8  5800.6  5850.6  6000.6  6025.6  6040.6  6097.5
    66.4   69.05   69.31    67.5   67.51   66.97   61.17   58.84      59   60.04
   64.41   64.97   64.92    67.7   68.48    68.1   68.28   66.97   66.87   65.43
   63.98   63.35   64.35   64.19   65.58    66.8   67.17   68.09   66.33   66.31
   66.71   68.73   69.21   71.81   71.84   71.83   71.83   71.76   71.76   71.76
   71.41   70.63    70.6      68   67.21   67.92   69.45   69.66   66.52   66.44
   66.49   67.53   67.66   67.03    67.4   66.17    67.8   68.83   70.14   76.91
      55      55      55      55      55      55      55      55      55      55
      55      55      55      55      55      55      55      55      55      55
      55      55      55      55      55      55      55      55      55    66.3
    66.7   66.99   66.81   66.81    66.9   67.03   67.33   67.26    65.7   68.13
   65.18   65.54   65.55   65.55    65.7   67.91   69.44   69.65   65.39   64.03
   65.03   67.53   67.66   67.03    67.4   66.17    67.8   68.83   70.14   76.91
Pier Skew, UpSta & Num, DnSta & Num=  ,4980.1, 2 ,4980.1, 2 , 0 , 0 , 0 ,,
     1.4     1.4
   56.82   68.31
     1.4     1.4
   56.82   68.31
Pier Skew, UpSta & Num, DnSta & Num=  ,5018.7, 2 ,5018.7, 2 , 0 , 0 , 0 ,,
     1.4     1.4
   56.29   68.28
     1.4     1.4
   56.29   68.28
BR Coef= 1 , 1 , 0 ,1.25, 0 ,,,0.8,0,2,0,
WSPro=,,,, 1 ,,,, 0 ,,,, 0 ,,,,-1 ,-1 ,-1 , 0 , 0 , 0 , 0 , 0
BR U #Sta/Elev= 152
  2915.1   72.96 2930.05   72.97 2945.01   73.01 2959.96   72.69 2974.91   71.18
 2989.86   68.17 3004.82   64.78 3019.77   62.62 3034.72   61.75 3049.67   61.22
 3064.63   61.09 3079.58   62.29 3094.53   64.38 3109.48   64.73 3124.44   64.84
 3139.39    65.1 3154.34   65.31 3169.29   65.27 3184.25   65.21  3199.2   65.23
 3214.15   65.58 3229.11   66.66 3244.06   67.39 3259.01   67.63 3273.96   67.85
 3288.92   68.12 3303.87    68.3 3318.82   68.22 3333.77   68.03 3348.73   67.84
 3363.68   67.64 3378.63   67.45 3393.58   67.26 3408.54   66.95 3423.49   66.74
 3438.44   66.55 3453.39   66.35 3468.35   66.24  3483.3   66.36 3498.25   66.65
 3513.21   67.17 3528.16   67.57 3543.11   67.78 3558.06   67.91 3573.02   67.57
 3587.97   67.65 3602.92   67.56 3617.87   67.45 3632.83   67.42 3647.78   67.47
 3662.73   67.54 3677.68   67.66 3692.64   67.89 3707.59   68.46 3722.54   68.52
 3737.49   68.02 3752.45   67.14  3767.4   66.78 3782.35   66.77 3797.31    66.5
 3812.26   66.15 3827.21   65.67 3842.16   65.55 3857.12   65.48 3872.07   65.51
 3887.02   65.54 3901.97   65.57 3916.93    65.6 3931.88    65.7 3946.83   65.99
 3961.78   66.13 3976.74   66.27 3991.69   66.63 4006.64   67.19 4021.59   67.11
 4036.55   67.23  4051.5   67.22 4066.45   67.11 4067.21   67.12  4533.9   66.29
  4571.3    66.3  4658.9   66.64  4673.9    66.7  4735.2   66.94  4758.6   67.03
  4783.9   67.06 4796.03   67.08 4834.22   66.99  4834.4   66.99  4872.8   67.01
  4883.2   66.94 4910.06   66.77 4913.89   66.81    4914   66.81 4914.11   66.81
  4923.3    66.9 4940.74   67.07 4940.85   67.03 4940.94      67 4941.02   66.97
 4953.03   62.79 4963.12   59.25 4964.58   58.69 4980.13   57.83 4999.54   57.68
 5018.71   57.28 5036.04   58.82 5036.88   59.19 5049.05   63.35 5056.19   65.65
 5056.25   65.67 5056.36    65.7 5063.91   68.13  5073.2   67.36 5099.33   65.18
  5123.2   65.38 5131.05   65.45  5170.4   65.53  5171.6   65.54 5173.49   65.55
  5173.6   65.55 5173.71   65.55 5208.29   65.78  5222.5   65.75  5246.4    65.7
  5270.1   67.91  5286.5   69.44  5296.5   69.65  5376.5   65.39  5391.5   64.11
  5396.5   64.03  5397.9   64.12  5411.5   65.03  5512.9   66.13  5562.9   66.67
  5584.7    66.9  5642.8   67.53  5645.8   67.49  5657.8   67.31  5692.8   67.66
  5742.8   67.03  5745.6   67.07  5796.4   67.37  5800.6    67.4  5850.6   66.17
  5975.6   67.45  5985.6   67.76  6000.6    67.8  6025.6   68.83  6040.6   70.14
  6095.6   76.75  6097.5   76.91
BR U #Mann= 6
  2915.1      .1 3229.11     .08 4940.94    .035 5063.91     .08  5645.8      .1
  5796.4      .2
BR U Banks=4940.94,5063.91
BR D #Sta/Elev= 152
  2915.1   66.36 2930.03   69.01 2944.96   69.27 2959.89   68.61 2974.82   67.94
 2989.75   67.46 3004.68   67.22 3019.61   67.45 3034.54   67.47 3049.47   66.93
  3064.4   63.76 3079.33   61.13 3094.26    60.2 3109.19   59.32 3124.12    58.8
 3139.05   58.96 3153.98      60 3168.91   61.67 3183.84   63.16 3198.77   64.37
  3213.7   64.93 3228.63   64.64 3243.57   64.88  3258.5   65.06 3273.43   64.88
 3288.36   65.57 3303.29   66.73 3318.22   67.66 3333.15   68.15 3348.08   68.44
 3363.01   68.44 3377.94   68.25 3392.87   68.06  3407.8   68.31 3422.73   68.14
 3437.66   68.11 3452.59   68.31 3467.52   68.24 3482.45   68.09 3497.38   67.85
 3512.31   67.57 3527.24   67.49 3542.17   67.23  3557.1   66.93 3572.03   66.92
 3586.96   66.95 3601.89   66.83 3616.82   66.53 3631.75   66.28 3646.68   66.14
 3661.61   65.99 3676.54   65.84 3691.47   65.69  3706.4   65.53 3721.33   65.39
 3736.26   64.79 3751.19   63.94 3766.12   63.64 3781.05   63.55 3795.98   63.45
 3810.91   63.31 3825.84   63.82 3840.77   64.31  3855.7   64.15 3870.64   64.83
 3885.57   65.54  3900.5   66.76 3915.43   67.13 3930.36   67.26 3945.29   67.43
 3960.22   67.57 3975.15   67.76 3990.08   67.98 4005.01   68.05 4019.94   68.06
 4034.87   68.03  4049.8   68.09 4064.73   68.07 4065.81   68.07  4533.9   66.29
  4571.3    66.3  4658.9   66.64  4673.9    66.7  4735.2   66.94  4758.6   67.03
  4783.9   67.06 4796.03   67.08 4834.22   66.99  4834.4   66.99  4872.8   67.01
  4883.2   66.94 4910.06   66.77 4913.89   66.81    4914   66.81 4914.11   66.81
  4923.3    66.9 4940.74   67.07 4940.85   67.03 4940.94      67 4941.02   66.97
 4953.03   62.79 4963.12   59.25 4964.58   58.69 4980.13   57.83 4999.54   57.68
 5018.71   57.28 5036.04   58.82 5036.88   59.19 5049.05   63.35 5056.19   65.65
 5056.25   65.67 5056.36    65.7 5063.91   68.13  5073.2   67.36 5099.33   65.18
  5123.2   65.38 5131.05   65.45  5170.4   65.53  5171.6   65.54 5173.49   65.55
  5173.6   65.55 5173.71   65.55 5208.29   65.78  5222.5   65.75  5246.4    65.7
  5270.1   67.91  5286.5   69.44  5296.5   69.65  5376.5   65.39  5391.5   64.11
  5396.5   64.03  5397.9   64.12  5411.5   65.03  5512.9   66.13  5562.9   66.67
  5584.7    66.9  5642.8   67.53  5645.8   67.49  5657.8   67.31  5692.8   67.66
  5742.8   67.03  5745.6   67.07  5796.4   67.37  5800.6    67.4  5850.6   66.17
  5975.6   67.45  5985.6   67.76  6000.6    67.8  6025.6   68.83  6040.6   70.14
  6095.6   76.75  6097.5   76.91
BR D #Mann= 6
  2915.1      .1 3228.63     .08 4940.94    .035 5063.91     .08  5645.8      .1
  5796.4      .2
BR D Banks=4940.94,5063.91
BC Design=,, 0 ,, 0 ,,,,,,
BC HTab HWMax=76.99
BC Use User HTab Curves=0
BC User HTab FreeFlow(D)= 0

Type RM Length L Ch R = 1 ,114469.5,108.06,108.15,104.9
BEGIN DESCRIPTION:
Downstream Section of Bridge/Culvert/Weir
END DESCRIPTION:
XS GIS Cut Line= 6
      3074060.63     13791573.34       3075110.8     13791102.43
       3075453.8     13790784.22      3075840.03     13790489.13
      3076266.67     13790208.59      3076826.35     13790119.34
#Sta/Elev= 30
  2915.1    66.4 2930.03   69.05 2944.96   69.31 3034.54   67.51 3049.47   66.97
 3079.33   61.17 3124.12   58.84 3198.77   64.41 3228.63   64.68 3273.43   64.92
 3348.08   68.48 3601.89   66.87 3810.91   63.35 3915.43   67.17 4005.01   68.09
 4940.94   67.04 4964.58   58.73 5018.71   57.32 5036.04   58.86 5063.91   68.17
 5099.33   65.22  5246.4   65.74  5296.5   69.69  5396.5   64.07  5645.8   67.53
  5796.4   67.41  5850.6   66.21  6000.6   67.84  6040.6   70.18  6097.5   76.95
#Mann= 6 ,-1 , 0
  2915.1      .1       0 3228.63     .08       0 4940.94    .035       0
 5063.91     .08       0  5645.8      .1       0  5796.4      .2       0
#XS Ineff= 2 , 0
       0    4940   66.49    5064       0   68.14
Permanent Ineff=
       F       F
Bank Sta=4940.94,5063.91
XS Rating Curve= 0 ,0
Exp/Cntr=0.5,0.3

Type RM Length L Ch R = 1 ,114361.3,143.2,141.47,147.03
BEGIN DESCRIPTION:
Upstream Section of Bridge/Culvert/Weir
END DESCRIPTION:
XS GIS Cut Line= 5
      3074222.65     13791939.29       3075267.1     13791060.81
      3075627.38     13790752.57      3075996.25     13790479.17
      3076747.31      13790012.3
#Sta/Elev= 30
  2915.1   72.98  2955.1    71.6  2990.1   64.85  3017.9   64.97  3222.7    65.4
  3500.1   64.44    3989   66.14  4571.3   66.26 4760.22   70.76 4874.34   69.58
 4911.45   70.27 4936.17    68.4  4964.5    58.9 4999.77   57.93 5035.42   58.93
 5078.23   72.35 5088.32   70.45  5246.4   71.42  5286.5    69.4  5321.5   69.99
  5341.5   69.34  5396.5   63.99  5446.5   68.37  5466.5   68.92  5591.3    67.1
  5815.6   67.08  5890.6   66.19  6010.6   68.06  6040.6    70.1  6097.5   76.87
#Mann= 5 , 1 , 0
  2915.1      .2       0  3017.9      .1       0 4936.17    .035       0
 5078.23      .1       0  5591.3      .2       0
#XS Ineff= 2 , 0
       0    4942    66.5    5078       0   72.48
Permanent Ineff=
       F       F
Bank Sta=4936.17,5078.23
XS Rating Curve= 0 ,0
Exp/Cntr=0.5,0.3