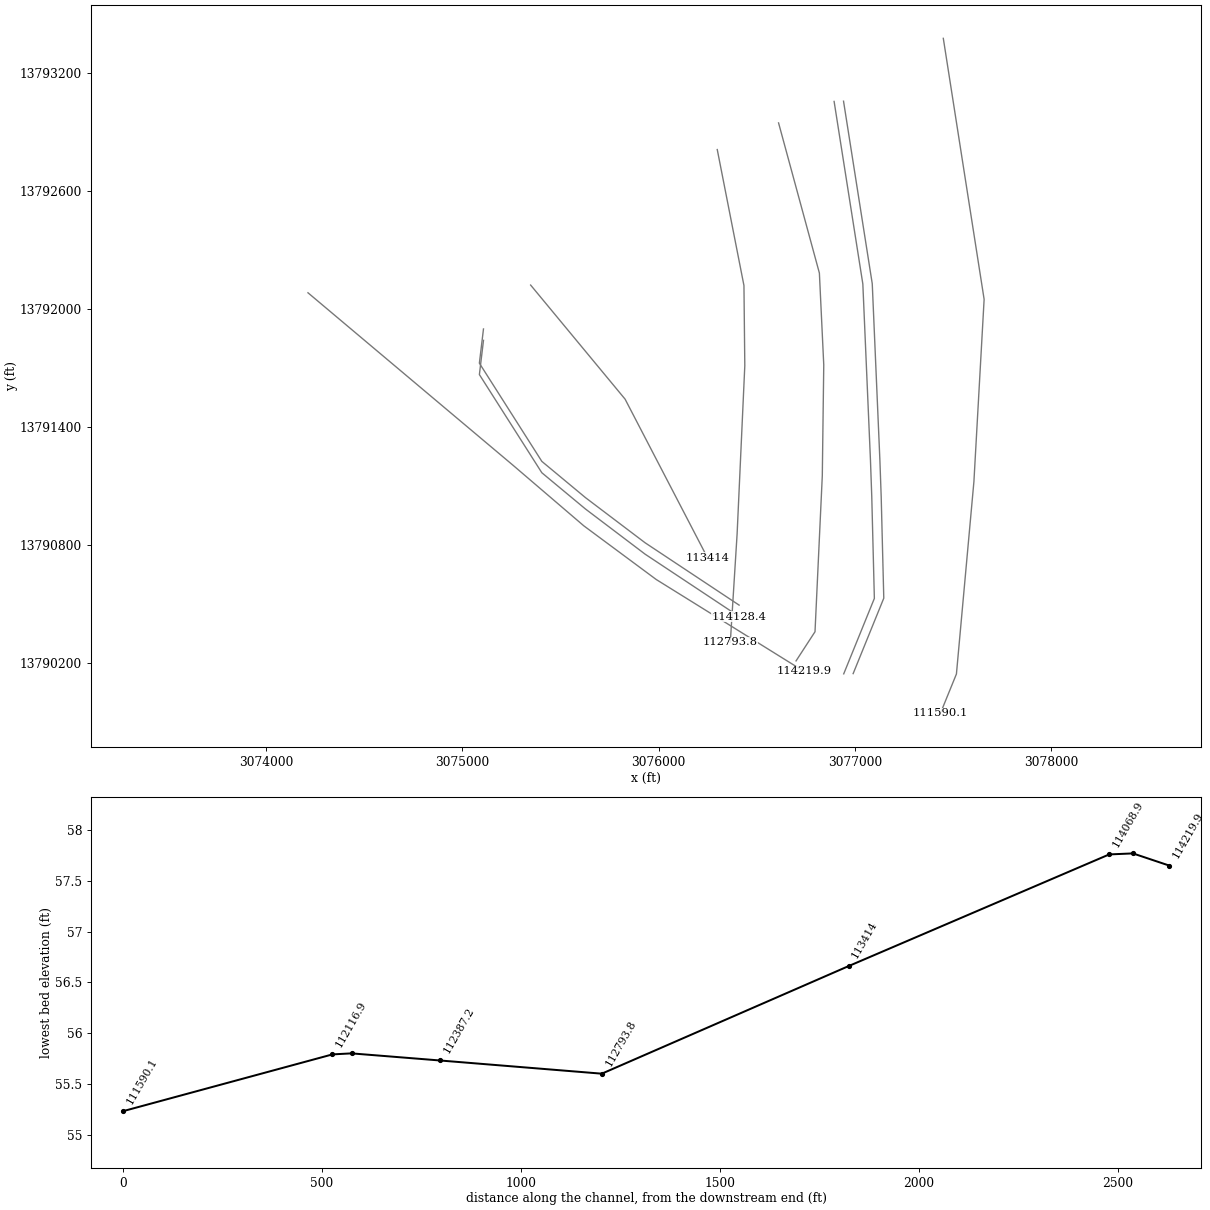
HEC-RAS study C100-00-00.prj: C100-00-00

--- C100-00-00.g01 (geometry) --- (continued)

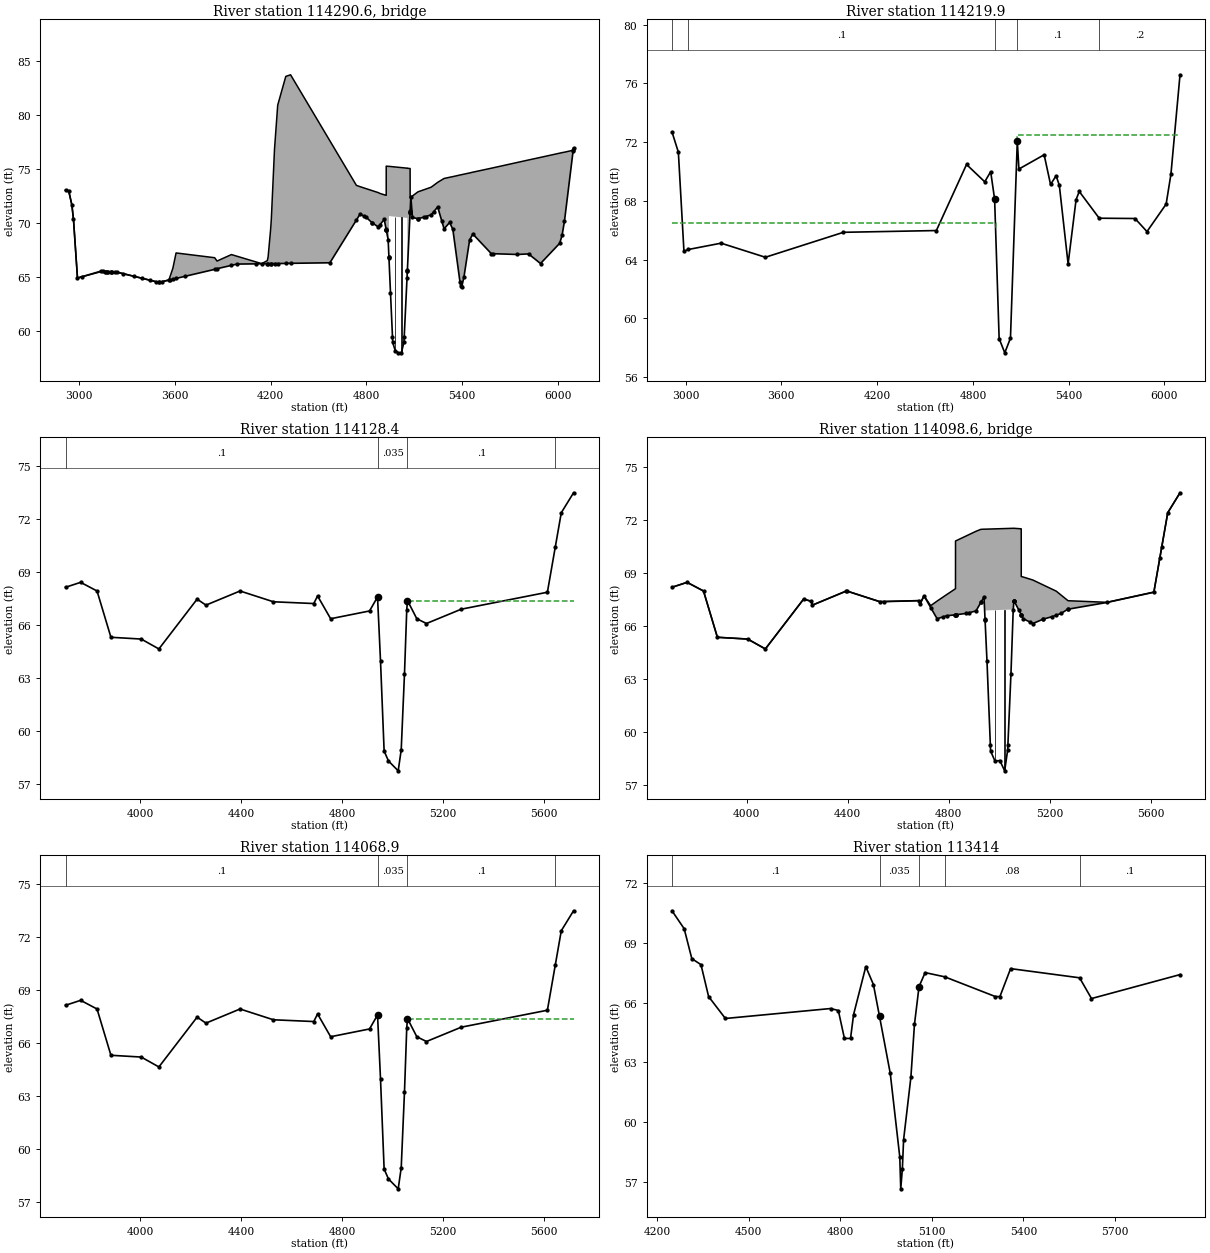
Type RM Length L Ch R = 3 ,114290.6,,,
BEGIN DESCRIPTION:
BELTWAY MAIN LANES Skew Angle 40 Degrees
Structure ID: C00-56
END DESCRIPTION:
Bridge Culvert--1,0,-1,-1, 0
Deck Dist Width WeirC Skew NumUp NumDn MinLoCord MaxHiCord MaxSubmerge Is_Ogee
10,124,2.6,0, 60, 60, , , 0.95, 0, 1,1,,
  2915.1  2935.1  2955.1  2965.1  2990.1  3147.7  3240.1  3500.1  3562.7  3587.7
  3607.7  3849.3  3864.3  3954.3  4144.3  4179.3  4184.3  4199.3  4204.3  4224.3
  4244.3  4294.9  4324.9  4571.3  4737.3 4760.22 4874.34  4883.9 4911.45 4923.99
  4924.1 4936.17 4941.01  4941.1 5056.56 5056.67  5073.8 5074.01 5078.23 5088.32
 5122.66 5205.44  5246.4  5286.5  5321.5  5341.5  5386.5  5391.5  5396.5  5411.5
  5446.5  5466.5  5582.8  5815.6  5890.6  6010.6  6025.6  6040.6  6094.7  6097.5
   73.02   72.96   71.64   70.31   64.89   65.52   65.43   64.49   64.71    65.8
   67.21   66.77   66.46   67.06   66.22    66.5   66.85   69.28   70.32   76.81
   80.88   83.54   83.69   77.58   73.46   73.34   72.79   72.72   72.59   72.54
   75.24   75.22   75.22   75.22   75.05   75.04   75.02   72.32    72.4   72.48
   72.86   73.29   73.74    74.1   74.21   74.27   74.42   74.44   74.45    74.5
   74.61   74.68   75.05   75.81   76.05   76.44   76.49   76.53   76.71   76.91
   73.02   72.96   71.64   70.31   64.89   65.51   65.42   64.48    64.7   64.78
   64.85   65.69   65.75   66.06   66.21   66.22   66.22   66.22   66.22   66.23
   66.23   66.24   66.25    66.3   70.25    70.8   69.62    69.8   70.31   69.36
   69.35   68.44   66.82   70.62   70.45   65.62      71   71.06   72.39   70.49
   70.38   70.74   71.46   69.44   70.03   69.38   64.48   64.11   64.03   65.03
   68.41   68.96   67.14   67.12   66.23    68.1   68.83   70.14   76.64   76.91
  2915.1  2935.1  2955.1  2965.1  2990.1  3147.7  3240.1  3500.1  3562.7  3587.7
  3607.7  3849.3  3864.3  3954.3  4144.3  4179.3  4184.3  4199.3  4204.3  4224.3
  4244.3  4294.9  4324.9  4571.3  4737.3 4760.22 4874.34  4883.9 4911.45 4923.99
  4924.1 4936.17 4941.01  4941.1 5056.56 5056.67  5073.8 5074.01 5078.23 5088.32
 5122.66 5205.44  5246.4  5286.5  5321.5  5341.5  5386.5  5391.5  5396.5  5411.5
  5446.5  5466.5  5582.8  5815.6  5890.6  6010.6  6025.6  6040.6  6094.7  6097.5
   73.02   72.96   71.64   70.31   64.89   65.52   65.43   64.49   64.71    65.8
   67.21   66.77   66.46   67.06   66.22    66.5   66.85   69.28   70.32   76.81
   80.88   83.54   83.69   77.58   73.46   73.34   72.79   72.72   72.59   72.54
   75.24   75.22   75.22   75.22   75.05   75.04   75.02   72.32    72.4   72.48
   72.86   73.29   73.74    74.1   74.21   74.27   74.42   74.44   74.45    74.5
   74.61   74.68   75.05   75.81   76.05   76.44   76.49   76.53   76.71   76.91
   72.69   72.63   71.31   69.98   64.56   65.18   65.09   64.15   64.37   64.45
   64.52   65.36   65.42   65.73   65.88   65.89   65.89   65.89   65.89    65.9
    65.9   65.91   65.92   65.97   69.92   70.47   69.29   69.47   69.98   69.03
   69.02   68.11   66.49   70.29   70.12   65.29   70.67   70.73   72.06   70.16
   70.05   70.41   71.13   69.11    69.7   69.05   64.15   63.78    63.7    64.7
   68.08   68.63   66.81   66.79    65.9   67.77    68.5   69.81   76.31   76.58
Pier Skew, UpSta & Num, DnSta & Num=  ,4980.6, 2 ,4980.6, 2 , 0 , 0 , 0 ,,
     1.4     1.4
   57.17   71.56
     1.4     1.4
   56.84   71.23
Pier Skew, UpSta & Num, DnSta & Num=  ,5019.3, 2 ,5019.3, 2 , 0 , 0 , 0 ,,
     1.4     1.4
   56.99    71.5
     1.4     1.4
   56.66   71.17
BR Coef= 1 , 1 , 0 ,1.25, 0 ,,,0.8,0,2,0,
WSPro=,,,, 1 ,,,, 0 ,,,, 0 ,,,,-1 ,-1 ,-1 , 0 , 0 , 0 , 0 , 0
BR U #Sta/Elev= 108
  2915.1   73.02  2935.1   72.96  2955.1   71.64  2965.1   70.31  2990.1   64.89
  3017.9   65.01  3135.1   65.52  3147.7   65.51  3162.7   65.49  3167.7   65.49
  3172.7   65.48  3182.7   65.47  3197.7   65.46  3202.7   65.46  3207.7   65.45
  3222.7   65.44  3240.1   65.42  3272.7    65.3  3342.7   65.05  3392.7   64.87
  3442.7   64.69  3482.7   64.54  3497.7   64.49  3500.1   64.48  3517.7   64.54
  3562.7    64.7  3572.7   64.73  3587.7   64.78  3607.7   64.85  3664.3   65.05
  3849.3   65.69  3864.3   65.75  3954.3   66.06    3989   66.18  4109.3    66.2
  4144.3   66.21  4179.3   66.22  4184.3   66.22  4199.3   66.22  4204.3   66.22
  4224.3   66.23  4244.3   66.23  4294.9   66.24  4324.9   66.25  4571.3    66.3
  4737.3   70.25 4760.22    70.8    4786   70.61  4798.8   70.51  4835.5      70
 4836.22   69.99 4874.34   69.62  4883.9    69.8 4911.45   70.31  4923.5    69.4
 4923.99   69.36  4924.1   69.35 4924.21   69.34 4936.17   68.44 4941.01   66.82
  4941.1   66.79 4941.17   66.77  4950.8   63.54 4963.35   59.44  4964.5   58.94
  4980.6   58.18 4999.77   57.97 5019.25   57.99 5035.42   58.97 5036.65   59.41
 5054.29   64.87  5056.5   65.56 5056.56   65.58 5056.67   65.62  5073.6   70.94
 5073.69   70.96  5073.8      71 5074.01   71.06 5078.23   72.39 5088.32   70.49
  5122.2   70.38 5122.66   70.38 5163.47   70.53  5173.4   70.58 5205.44   70.74
  5221.9   71.03  5246.4   71.46  5272.4   70.15  5286.5   69.44  5321.5   70.03
  5341.5   69.38  5386.5   64.48  5391.5   64.11  5396.5   64.03  5411.5   65.03
  5446.5   68.41  5466.5   68.96  5582.8   67.14  5591.3   67.14  5745.6   67.07
  5815.6   67.12  5890.6   66.23  6010.6    68.1  6025.6   68.83  6040.6   70.14
  6094.7   76.64  6095.6   76.75  6097.5   76.91
BR U #Mann= 5
  2915.1      .2  3017.9      .1 4936.17    .035 5078.23      .1  5591.3      .2
BR U Banks=4936.17,5078.23
BR D #Sta/Elev= 108
  2915.1   72.69  2935.1   72.63  2955.1   71.31  2965.1   69.98  2990.1   64.56
  3017.9   64.68  3135.1   65.19  3147.7   65.18  3162.7   65.16  3167.7   65.16
  3172.7   65.15  3182.7   65.14  3197.7   65.13  3202.7   65.13  3207.7   65.12
  3222.7   65.11  3240.1   65.09  3272.7   64.97  3342.7   64.72  3392.7   64.54
  3442.7   64.36  3482.7   64.21  3497.7   64.16  3500.1   64.15  3517.7   64.21
  3562.7   64.37  3572.7    64.4  3587.7   64.45  3607.7   64.52  3664.3   64.72
  3849.3   65.36  3864.3   65.42  3954.3   65.73    3989   65.85  4109.3   65.87
  4144.3   65.88  4179.3   65.89  4184.3   65.89  4199.3   65.89  4204.3   65.89
  4224.3    65.9  4244.3    65.9  4294.9   65.91  4324.9   65.92  4571.3   65.97
  4737.3   69.92 4760.22   70.47    4786   70.28  4798.8   70.18  4835.5   69.67
 4836.22   69.66 4874.34   69.29  4883.9   69.47 4911.45   69.98  4923.5   69.07
 4923.99   69.03  4924.1   69.02 4924.21   69.01 4936.17   68.11 4941.01   66.49
  4941.1   66.46 4941.17   66.44  4950.8   63.21 4963.35   59.11  4964.5   58.61
  4980.6   57.85 4999.77   57.64 5019.25   57.66 5035.42   58.64 5036.65   59.08
 5054.29   64.54  5056.5   65.23 5056.56   65.25 5056.67   65.29  5073.6   70.61
 5073.69   70.63  5073.8   70.67 5074.01   70.73 5078.23   72.06 5088.32   70.16
  5122.2   70.05 5122.66   70.05 5163.47    70.2  5173.4   70.25 5205.44   70.41
  5221.9    70.7  5246.4   71.13  5272.4   69.82  5286.5   69.11  5321.5    69.7
  5341.5   69.05  5386.5   64.15  5391.5   63.78  5396.5    63.7  5411.5    64.7
  5446.5   68.08  5466.5   68.63  5582.8   66.81  5591.3   66.81  5745.6   66.74
  5815.6   66.79  5890.6    65.9  6010.6   67.77  6025.6    68.5  6040.6   69.81
  6094.7   76.31  6095.6   76.42  6097.5   76.58
BR D #Mann= 5
  2915.1      .2  3017.9      .1 4936.17    .035 5078.23      .1  5591.3      .2
BR D Banks=4936.17,5078.23
BC Design=,, 0 ,, 0 ,,,,,,
BC HTab HWMax=76.87
BC Use User HTab Curves=0
BC User HTab FreeFlow(D)= 0

Type RM Length L Ch R = 1 ,114219.9,91.78,91.43,94.02
BEGIN DESCRIPTION:
Downstream Section of Bridge/Culvert/Weir
END DESCRIPTION:
XS GIS Cut Line= 5
      3074214.59     13792083.07      3075259.04     13791204.59
      3075619.32     13790896.35      3075988.19     13790622.95
      3076739.25     13790156.08
#Sta/Elev= 30
  2915.1    72.7  2955.1   71.32  2990.1   64.57  3017.9   64.69  3222.7   65.12
  3500.1   64.16    3989   65.86  4571.3   65.98 4760.22   70.48 4874.34    69.3
 4911.45   69.99 4936.17   68.12  4964.5   58.62 4999.77   57.65 5035.42   58.65
 5078.23   72.07 5088.32   70.17  5246.4   71.14  5286.5   69.12  5321.5   69.71
  5341.5   69.06  5396.5   63.71  5446.5   68.09  5466.5   68.64  5591.3   66.82
  5815.6    66.8  5890.6   65.91  6010.6   67.78  6040.6   69.82  6097.5   76.59
#Mann= 5 , 1 , 0
  2915.1      .2       0  3017.9      .1       0 4936.17    .035       0
 5078.23      .1       0  5591.3      .2       0
#XS Ineff= 2 , 0
       0    4942    66.5    5078       0   72.48
Permanent Ineff=
       F       F
Bank Sta=4936.17,5078.23
XS Rating Curve= 0 ,0
Exp/Cntr=0.5,0.3

Type RM Length L Ch R = 1 ,114128.4,54.58,59.53,61.98
BEGIN DESCRIPTION:
Upstream Section of Bridge/Culvert/Weir
END DESCRIPTION:
XS GIS Cut Line= 6
      3075108.43     13791840.86      3075087.51     13791666.55
      3075405.59      13791166.6      3075627.72     13790982.06
      3075931.49     13790752.06      3076410.18     13790434.62
#Sta/Elev= 30
  3704.1   68.16    3764   68.44    3829   67.95    3884   65.33    4004   65.23
    4074   64.67  4225.4   67.49  4260.4   67.15  4395.4   67.95  4527.5   67.34
  4687.5   67.24  4702.5   67.67 4754.29   66.38 4908.29   66.82 4940.02   67.61
  4951.8   63.99 4966.12   58.89 4983.29   58.33 5021.87   57.77  5033.8   58.96
 5046.74   63.25 5055.75   66.89  5058.6   67.41 5095.56   66.38 5133.83   66.11
  5271.6   66.92  5612.8   67.88  5644.2   70.45  5667.8   72.38  5716.4   73.51
#Mann= 4 , 1 , 0
  3704.1      .1       0 4940.02    .035       0  5058.6      .1       0
  5644.2      .2       0
#XS Ineff= 2 , 0
       0    4945      66    5059       0    67.4
Permanent Ineff=
       F       F
Bank Sta=4940.02,5058.6
XS Rating Curve= 0 ,0
Exp/Cntr=0.5,0.3

Type RM Length L Ch R = 3 ,114098.6,,,
BEGIN DESCRIPTION:
FRONTAGE ROAD NORTH BELTWAY Skew Angle 40 degrees
Structure ID: C00-55
END DESCRIPTION:
Bridge Culvert--1,0,-1,-1, 0
Deck Dist Width WeirC Skew NumUp NumDn MinLoCord MaxHiCord MaxSubmerge Is_Ogee
10,38,2.6,0, 36, 36, , , 0.95, 0, 1,1,,
  3704.1    3764    3829    3884    4004    4074  4225.4  4255.4  4260.4  4395.4
  4527.5  4682.5  4687.5  4702.5  4728.9 4754.29 4791.48 4827.09  4827.2 4908.29
  4927.5 4940.02 4944.09 4944.18 5055.75  5058.6  5087.5 5087.61 5095.56 5133.83
  5226.3  5272.9  5426.6  5612.8  5667.8  5716.4
   68.17   68.45   67.96   65.34   65.24   64.68    67.5   67.38   67.16   67.97
   67.36   67.42   67.26   67.69   67.13   67.39   67.75   68.09   70.79   71.34
   71.45   71.46   71.46   71.46   71.51   71.51   71.48   68.78   68.75   68.58
   67.95   67.41   67.32    67.9   72.39   73.52
   68.17   68.45   67.96   65.34   65.24   64.68    67.5   67.38   67.16   67.96
   67.35   67.41   67.25   67.68   67.02   66.39   66.56   66.61   66.61   66.83
   67.31   67.62   66.37   66.86   66.91   67.42   66.61   66.61   66.39   66.12
   66.59   66.93   67.31   67.89   72.39   73.52
  3704.1    3764    3829    3884    4004    4074  4225.4  4255.4  4260.4  4395.4
  4527.5  4682.5  4687.5  4702.5  4728.9 4754.29 4791.48 4827.09  4827.2 4908.29
  4927.5 4940.02 4944.09 4944.18 5055.75  5058.6  5087.5 5087.61 5095.56 5133.83
  5226.3  5272.9  5426.6  5612.8  5667.8  5716.4
   68.17   68.45   67.96   65.34   65.24   64.68    67.5   67.38   67.16   67.97
   67.36   67.42   67.26   67.69   67.13   67.39   67.75   68.09   70.79   71.34
   71.45   71.46   71.46   71.46   71.51   71.51   71.48   68.78   68.75   68.58
   67.95   67.41   67.32    67.9   72.39   73.52
   68.17   68.45   67.96   65.34   65.24   64.68    67.5   67.38   67.16   67.96
   67.35   67.41   67.25   67.68   67.02   66.39   66.56   66.61   66.61   66.83
   67.31   67.62   66.37   66.86   66.91   67.42   66.61   66.61   66.39   66.12
   66.59   66.93   67.31   67.89   72.39   73.52
Pier Skew, UpSta & Num, DnSta & Num=  ,4983.3, 2 ,4983.3, 2 , 0 , 0 , 0 ,,
     1.4     1.4
   57.34   67.88
     1.4     1.4
   57.34   67.88
Pier Skew, UpSta & Num, DnSta & Num=  ,5021.9, 2 ,5021.9, 2 , 0 , 0 , 0 ,,
     1.4     1.4
    56.8   67.89
     1.4     1.4
    56.8   67.89
BR Coef= 1 , 1 , 0 ,1.25, 0 ,,,0.8,0,2,0,
WSPro=,,,, 1 ,,,, 0 ,,,, 0 ,,,,-1 ,-1 ,-1 , 0 , 0 , 0 , 0 , 0
BR U #Sta/Elev= 68
  3704.1   68.17    3764   68.45    3829   67.96    3884   65.34    4004   65.24
    4074   64.68  4225.4    67.5  4255.4   67.38  4260.4   67.16  4394.3   67.95
  4395.4   67.96  4527.5   67.35  4544.3   67.36  4682.5   67.41  4687.5   67.25
  4702.5   67.68  4728.9   67.02 4754.29   66.39  4779.4    66.5 4791.48   66.56
    4827   66.61 4827.09   66.61  4827.2   66.61 4827.31   66.61 4830.68   66.62
 4868.56   66.69  4880.6   66.73 4908.29   66.83  4927.5   67.31    4928   67.32
 4940.02   67.62 4944.09   66.37 4944.18   66.34 4944.25   66.32  4951.8      64
  4965.2   59.25 4966.12    58.9 4983.29   58.34 5002.85   58.36 5021.87   57.78
  5033.8   58.97 5034.73   59.27 5046.74   63.26 5055.75    66.9  5058.6   67.42
  5059.5   67.39 5059.57   67.39 5059.68   67.39  5077.5   66.89 5087.39   66.62
  5087.5   66.61 5087.61   66.61 5095.56   66.39  5123.9   66.19 5133.83   66.12
 5173.33   66.36  5175.1   66.37 5210.44   66.51  5226.3   66.59 5246.94    66.7
  5271.6   66.93  5272.9   66.93  5426.6   67.31  5612.8   67.89  5636.7   69.85
  5644.2   70.46  5667.8   72.39  5716.4   73.52
BR U #Mann= 4
  3704.1      .1 4940.02    .035  5058.6      .1  5644.2      .2
BR U Banks=4940.02,5058.6
BR D #Sta/Elev= 68
  3704.1   68.17    3764   68.45    3829   67.96    3884   65.34    4004   65.24
    4074   64.68  4225.4    67.5  4255.4   67.38  4260.4   67.16  4394.3   67.95
  4395.4   67.96  4527.5   67.35  4544.3   67.36  4682.5   67.41  4687.5   67.25
  4702.5   67.68  4728.9   67.02 4754.29   66.39  4779.4    66.5 4791.48   66.56
    4827   66.61 4827.09   66.61  4827.2   66.61 4827.31   66.61 4830.68   66.62
 4868.56   66.69  4880.6   66.73 4908.29   66.83  4927.5   67.31    4928   67.32
 4940.02   67.62 4944.09   66.37 4944.18   66.34 4944.25   66.32  4951.8      64
  4965.2   59.25 4966.12    58.9 4983.29   58.34 5002.85   58.36 5021.87   57.78
  5033.8   58.97 5034.73   59.27 5046.74   63.26 5055.75    66.9  5058.6   67.42
  5059.5   67.39 5059.57   67.39 5059.68   67.39  5077.5   66.89 5087.39   66.62
  5087.5   66.61 5087.61   66.61 5095.56   66.39  5123.9   66.19 5133.83   66.12
 5173.33   66.36  5175.1   66.37 5210.44   66.51  5226.3   66.59 5246.94    66.7
  5271.6   66.93  5272.9   66.93  5426.6   67.31  5612.8   67.89  5636.7   69.85
  5644.2   70.46  5667.8   72.39  5716.4   73.52
BR D #Mann= 4
  3704.1      .1 4940.02    .035  5058.6      .1  5644.2      .2
BR D Banks=4940.02,5058.6
BC Design=,, 0 ,, 0 ,,,,,,
BC HTab HWMax=73.51
BC Use User HTab Curves=0
BC User HTab FreeFlow(D)= 0

Type RM Length L Ch R = 1 ,114068.9,644.75,654.84,642.21
BEGIN DESCRIPTION:
Downstream Section of Bridge/Culvert/Weir
END DESCRIPTION:
XS GIS Cut Line= 6
      3075108.37     13791898.86      3075087.45     13791724.55
      3075405.53      13791224.6      3075627.66     13791040.06
      3075931.43     13790810.06      3076410.11     13790492.62
#Sta/Elev= 30
  3704.1   68.15    3764   68.43    3829   67.94    3884   65.32    4004   65.22
    4074   64.66  4225.4   67.48  4260.4   67.14  4395.4   67.94  4527.5   67.33
  4687.5   67.23  4702.5   67.66 4754.29   66.37 4908.29   66.81 4940.02    67.6
  4951.8   63.98 4966.12   58.88 4983.29   58.32 5021.87   57.76  5033.8   58.95
 5046.74   63.24 5055.75   66.88  5058.6    67.4 5095.56   66.37 5133.83    66.1
  5271.6   66.91  5612.8   67.87  5644.2   70.44  5667.8   72.37  5716.4    73.5
#Mann= 4 , 1 , 0
  3704.1      .1       0 4940.02    .035       0  5058.6      .1       0
  5644.2      .2       0
#XS Ineff= 2 , 0
       0    4945      66    5059       0    67.4
Permanent Ineff=
       F       F
Bank Sta=4940.02,5058.6
XS Rating Curve= 0 ,0
Exp/Cntr=0.5,0.3

Type RM Length L Ch R = 1 ,113414  ,642.19,620.29,580.35
BEGIN DESCRIPTION:
Cross Section 115510.1-Interpolated
END DESCRIPTION:
XS GIS Cut Line= 3
      3075348.49     13792122.43      3075829.62     13791541.31
      3076249.23     13790733.88
#Sta/Elev= 30
  4248.7    70.6  4288.7    69.7  4313.7    68.2  4343.7    67.9  4368.7    66.3
  4423.7    65.2  4768.7    65.7  4793.7    65.6  4813.7    64.2  4833.7    64.2
  4843.7    65.4  4883.7    67.8  4908.7    66.9  4928.7    65.3  4963.8   62.45
    4995   58.26  4998.2   56.66  5003.5   57.66  5007.5   59.12  5031.4   62.25
  5043.1    64.9  5058.1    66.8  5078.1    67.5  5142.1   67.29  5308.1    66.3
  5323.1    66.3  5358.1    67.7  5584.1   67.24  5623.1    66.2  5913.1    67.4
#Mann= 5 , 1 , 0
  4248.7      .1       0  4928.7    .035       0  5058.1      .1       0
  5142.1     .08       0  5584.1      .1       0
Bank Sta=4928.7,5058.1
XS Rating Curve= 0 ,0
Exp/Cntr=0.3,0.1

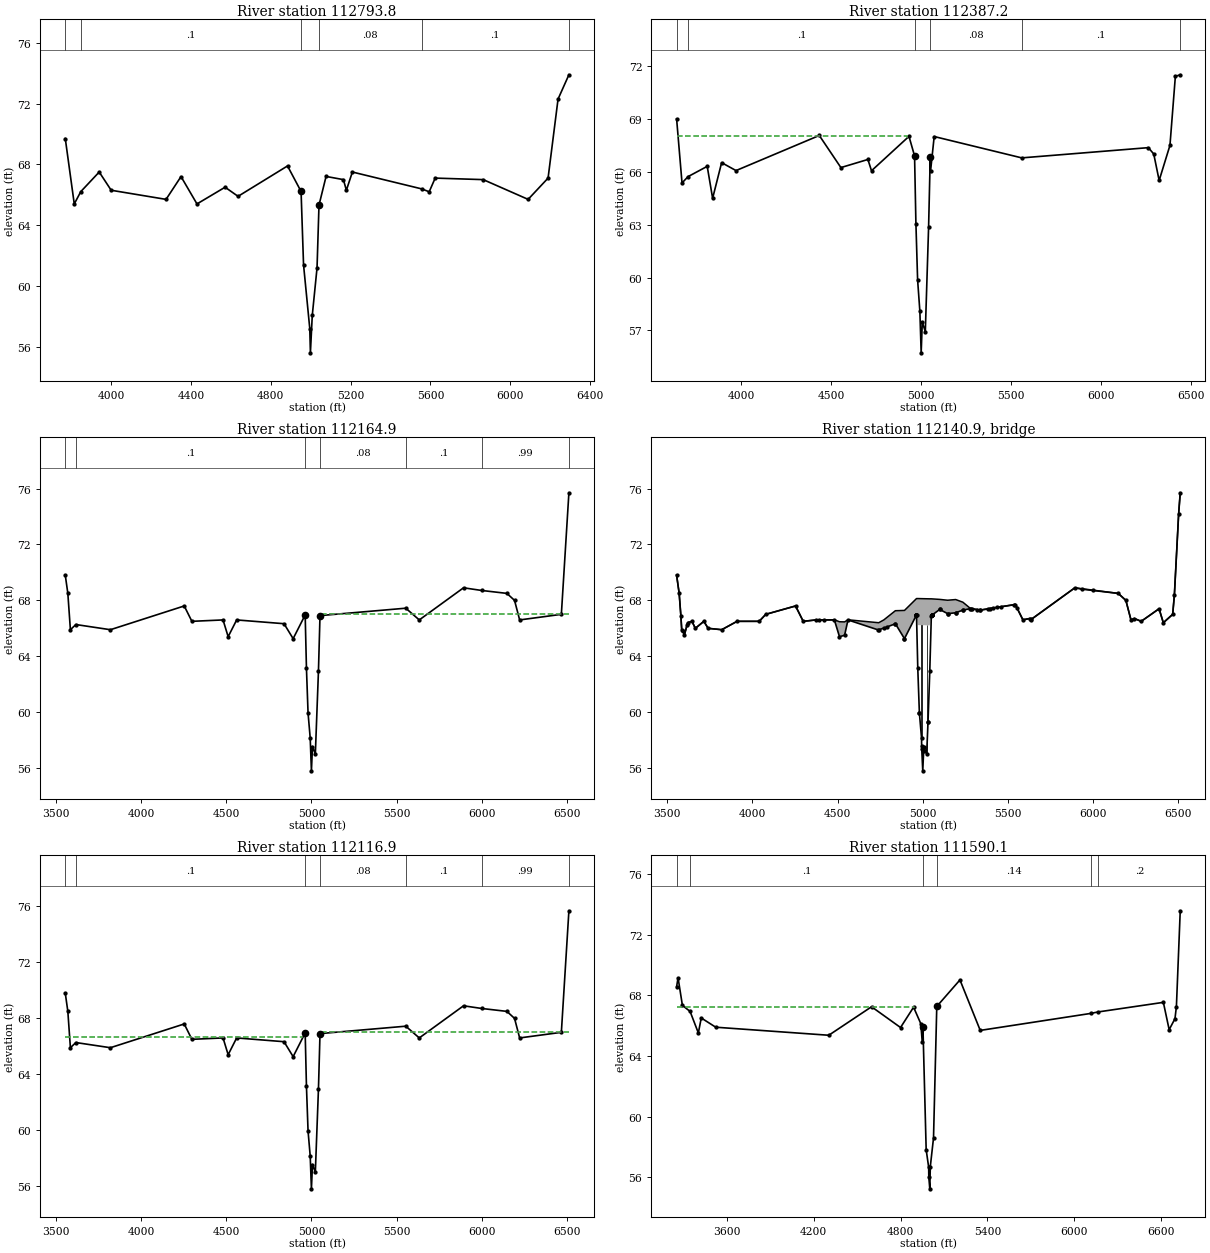
Type RM Length L Ch R = 1 ,112793.8,405.71,406.57,408.92
BEGIN DESCRIPTION:
Cross Section  114891.1
END DESCRIPTION:
XS GIS Cut Line= 5
      3076298.88     13792812.45      3076434.86     13792119.84
       3076439.2     13791711.91      3076400.14       13790857.
      3076365.43      13790303.7
#Sta/Elev= 30
  3769.7    69.7  3814.7    65.4  3847.4   66.21  3939.7    67.5  3999.7    66.3
  4274.7    65.7  4349.7    67.2  4429.7    65.4  4570.6    66.5  4635.6    65.9
  4883.5    67.9  4951.4   66.22  4963.8   61.39    4995    57.2  4998.2    55.6
  5007.5   58.06  5031.4   61.19  5041.2   65.32  5076.7   67.21  5163.5      67
  5178.5    66.3  5208.5    67.5    5556   66.39  5593.5    66.2  5623.5    67.1
  5864.3      67  6089.3    65.7  6189.3    67.1  6239.3    72.3  6293.7    73.9
#Mann= 6 , 1 , 0
  3769.7      .2       0  3847.4      .1       0  4951.4    .035       0
  5041.2     .08       0    5556      .1       0  6293.7      .2       0
Bank Sta=4951.4,5041.2
XS Rating Curve= 0 ,0
Exp/Cntr=0.3,0.1

Type RM Length L Ch R = 1 ,112387.2,219.85,222.32,226.21
BEGIN DESCRIPTION:
Cross Section 114484.0 - Interpolated
END DESCRIPTION:
XS GIS Cut Line= 6
      3076611.14     13792948.19      3076819.02     13792183.47
      3076841.29     13791715.74      3076833.87     13791151.48
      3076796.75     13790357.07      3076700.23     13790208.59
#Sta/Elev= 30
  3641.7   68.99  3671.7   65.36  3705.6   65.72  3811.7    66.3  3841.7   64.49
  3891.7   66.51  3971.7   66.06  4434.2   68.05  4554.2   66.23  4704.2   66.69
  4724.2   66.05  4932.4      68  4963.4   66.89  4970.9   63.06  4980.3   59.87
  4992.9   58.08  5000.1   55.73  5006.3   57.47  5023.1   56.93  5041.3   62.84
  5050.5   66.84  5052.4   66.05  5072.4   67.99  5558.7   66.78    6262   67.36
    6292      67    6322    65.5    6382   67.49    6412    71.4  6439.1   71.49
#Mann= 6 , 1 , 0
  3641.7      .2       0  3705.6      .1       0  4963.4    .035       0
  5050.5     .08       0  5558.7      .1       0  6439.1      .2       0
#XS Ineff= 2 , 0
       0    4924      68    5080       0    67.9
Permanent Ineff=
       F       F
Bank Sta=4963.4,5050.5
XS Rating Curve= 0 ,0
Exp/Cntr=0.5,0.3

Type RM Length L Ch R = 1 ,112164.9,48.01,47.99,49.08
BEGIN DESCRIPTION:
Upstream Section of Bridge/Culvert/Weir
END DESCRIPTION:
XS GIS Cut Line= 6
        3076894.     13793057.53      3077040.28      13792128.1
      3077079.17     13791229.62      3077085.77     13791044.94
      3077099.01     13790526.64      3076942.98     13790142.58
#Sta/Elev= 30
  3554.4    69.8  3569.4    68.5  3584.4    65.9  3616.6   66.27  3819.4    65.9
    4253    67.6    4298    66.5    4481    66.6    4511    65.4    4561    66.6
  4839.2   66.33  4892.7   65.26  4963.4   66.96  4970.9   63.13  4980.3   59.94
  4992.9   58.15  5000.1    55.8  5006.3   57.54  5023.1      57  5041.3   62.91
  5050.5   66.91  5554.3   67.44  5633.5    66.6  5893.5    68.9  5999.4   68.71
  6148.1    68.5  6193.1      68  6223.1    66.6  6468.1      67  6512.4    75.7
#Mann= 7 , 1 , 0
  3554.4      .2       0  3616.6      .1       0  4963.4    .035       0
  5050.5     .08       0  5554.3      .1       0  5999.4     .99       0
  6512.4      .2       0
#XS Ineff= 2 , 0
       0    4951   66.66    5062       0      67
Permanent Ineff=
       F       F
Bank Sta=4963.4,5050.5
XS Rating Curve= 0 ,0
Exp/Cntr=0.5,0.3

Type RM Length L Ch R = 3 ,112140.9,,,
BEGIN DESCRIPTION:
SETTEMONT STREET
Structure ID: C00-54
END DESCRIPTION:
Bridge Culvert--1,0,-1,-1, 0
Deck Dist Width WeirC Skew NumUp NumDn MinLoCord MaxHiCord MaxSubmerge Is_Ogee
10,28,2.6,0, 52, 52, , , 0.95, 0, 1,1,,
  3554.4  3569.4  3579.4  3584.4  3594.4  3599.4  3619.4  3644.4  3664.4  3714.4
  3739.4  3819.4  3909.4  4039.4    4078    4253    4298    4373    4481    4511
    4541    4561  4741.2  4771.2  4839.2  4892.7  4963.4  4970.9  5041.3  5050.5
  5099.6  5146.2  5193.3  5235.6  5280.2  5336.5  5543.5  5588.5  5628.5  5633.5
  5893.5  6148.1  6193.1  6223.1  6243.1  6283.1  6388.1  6413.1  6468.1  6478.1
  6503.1  6512.4
    69.8    68.5    66.9    65.9    65.8    65.5    66.4    66.5      66    66.5
      66    65.9    66.5    66.5      67    67.6    66.5    66.6   66.61   66.47
   66.46   66.61    66.4    66.6   67.26   67.28   68.13   68.13   68.11   68.11
   68.07   68.01   68.06   67.87   67.42   67.31   67.71   66.61   66.71   66.61
    68.9    68.5      68    66.6    66.7    66.5    67.4    66.4      67    68.4
    74.2    75.7
    69.8    68.5    66.9    65.9    65.8    65.5    66.4    66.5      66    66.5
      66    65.9    66.5    66.5      67    67.6    66.5    66.6    66.6    65.4
    65.5    66.6   65.89   66.02   66.33   65.26   66.96   66.23   66.21   66.91
   67.35   67.05   67.11    67.3   67.41    67.3    67.7    66.6    66.7    66.6
    68.9    68.5      68    66.6    66.7    66.5    67.4    66.4      67    68.4
    74.2    75.7
  3554.4  3569.4  3579.4  3584.4  3594.4  3599.4  3619.4  3644.4  3664.4  3714.4
  3739.4  3819.4  3909.4  4039.4    4078    4253    4298    4373    4481    4511
    4541    4561  4741.2  4771.2  4839.2  4892.7  4963.4  4970.9  5041.3  5050.5
  5099.6  5146.2  5193.3  5235.6  5280.2  5336.5  5543.5  5588.5  5628.5  5633.5
  5893.5  6148.1  6193.1  6223.1  6243.1  6283.1  6388.1  6413.1  6468.1  6478.1
  6503.1  6512.4
    69.8    68.5    66.9    65.9    65.8    65.5    66.4    66.5      66    66.5
      66    65.9    66.5    66.5      67    67.6    66.5    66.6   66.61   66.47
   66.46   66.61    66.4    66.6   67.26   67.28   68.13   68.13   68.11   68.11
   68.07   68.01   68.06   67.87   67.42   67.31   67.71   66.61   66.71   66.61
    68.9    68.5      68    66.6    66.7    66.5    67.4    66.4      67    68.4
    74.2    75.7
    69.8    68.5    66.9    65.9    65.8    65.5    66.4    66.5      66    66.5
      66    65.9    66.5    66.5      67    67.6    66.5    66.6    66.6    65.4
    65.5    66.6   65.89   66.02   66.33   65.26   66.96   66.23   66.21   66.91
   67.35   67.05   67.11    67.3   67.41    67.3    67.7    66.6    66.7    66.6
    68.9    68.5      68    66.6    66.7    66.5    67.4    66.4      67    68.4
    74.2    75.7
Pier Skew, UpSta & Num, DnSta & Num=  ,4992.9, 2 ,4992.9, 2 , 0 , 0 , 0 ,,
     1.4     1.4
   56.64   67.22
     1.4     1.4
   56.64   67.22
Pier Skew, UpSta & Num, DnSta & Num=  ,5023.1, 2 ,5023.1, 2 , 0 , 0 , 0 ,,
     1.4     1.4
   56.02   67.22
     1.4     1.4
   56.02   67.22
Abutment Skew #Up #Dn= , 2 , 2
  4961.6  4980.4
   66.92   59.93
  4961.6  4980.4
   66.92   59.93
Abutment Skew #Up #Dn= , 2 , 2
    5031 5052.79
   59.31   66.93
    5031 5052.79
   59.31   66.93
BR Coef= 1 , 1 , 0 ,1.25, 0 ,,,0.8,0,2,0,
WSPro=,,,, 1 ,,,, 0 ,,,, 0 ,,,,-1 ,-1 ,-1 , 0 , 0 , 0 , 0 , 0
BR U #Sta/Elev= 100
  3554.4    69.8  3569.4    68.5  3579.4    66.9  3584.4    65.9  3594.4    65.8
  3599.4    65.5  3616.6   66.27  3619.4    66.4  3644.4    66.5  3664.4      66
  3714.4    66.5  3739.4      66  3819.4    65.9  3909.4    66.5  4039.4    66.5
    4078      67    4253    67.6    4298    66.5    4373    66.6  4391.2    66.6
    4421    66.6    4481    66.6    4511    65.4    4541    65.5    4561    66.6
  4739.9   65.88  4741.2   65.89  4771.2   66.02  4790.5    66.1    4836   66.31
  4839.2   66.33  4892.6   65.26  4892.7   65.26  4961.6   66.92 4961.71   66.92
  4961.8   66.92 4962.09   66.93  4962.2   66.93 4962.31   66.93  4963.4   66.96
  4970.9   63.13  4980.3   59.94  4980.4   59.93  4992.9   58.15  4993.7   57.57
  4994.3   57.34  5000.1    55.8  5005.4   57.24  5006.3   57.54  5023.1      57
  5030.9   59.27    5031   59.31  5041.3   62.91  5050.5   66.91 5052.29   66.93
  5052.4   66.93 5052.51   66.93 5052.59   66.93  5052.7   66.93  5052.8   66.93
  5099.6   67.35  5099.7   67.35  5146.2   67.05  5146.5   67.05  5192.7   67.11
  5193.3   67.11  5235.3    67.3  5235.6    67.3  5280.2   67.41  5281.2   67.41
  5291.2   67.39  5321.2   67.33  5336.5    67.3  5338.5    67.3  5381.2   67.38
  5394.6   67.41  5414.6   67.45  5434.6   67.49  5459.6   67.54  5534.6   67.68
  5543.5    67.7  5554.3   67.44  5588.5    66.6  5628.5    66.7  5633.5    66.6
  5637.8   66.64  5893.5    68.9  5935.4    68.8  5999.4   68.71  6148.1    68.5
  6193.1      68  6223.1    66.6  6243.1    66.7  6283.1    66.5  6388.1    67.4
  6413.1    66.4  6468.1      67  6478.1    68.4  6503.1    74.2  6512.4    75.7
BR U #Mann= 7
  3554.4      .2  3616.6      .1  4963.4    .035  5050.5     .08  5554.3      .1
  5999.4     .99  6512.4      .2
BR U Banks=4963.4,5050.5
BR D #Sta/Elev= 100
  3554.4    69.8  3569.4    68.5  3579.4    66.9  3584.4    65.9  3594.4    65.8
  3599.4    65.5  3616.6   66.27  3619.4    66.4  3644.4    66.5  3664.4      66
  3714.4    66.5  3739.4      66  3819.4    65.9  3909.4    66.5  4039.4    66.5
    4078      67    4253    67.6    4298    66.5    4373    66.6  4391.2    66.6
    4421    66.6    4481    66.6    4511    65.4    4541    65.5    4561    66.6
  4739.9   65.88  4741.2   65.89  4771.2   66.02  4790.5    66.1    4836   66.31
  4839.2   66.33  4892.6   65.26  4892.7   65.26  4961.6   66.92 4961.71   66.92
  4961.8   66.92 4962.09   66.93  4962.2   66.93 4962.31   66.93  4963.4   66.96
  4970.9   63.13  4980.3   59.94  4980.4   59.93  4992.9   58.15  4993.7   57.57
  4994.3   57.34  5000.1    55.8  5005.4   57.24  5006.3   57.54  5023.1      57
  5030.9   59.27    5031   59.31  5041.3   62.91  5050.5   66.91 5052.29   66.93
  5052.4   66.93 5052.51   66.93 5052.59   66.93  5052.7   66.93  5052.8   66.93
  5099.6   67.35  5099.7   67.35  5146.2   67.05  5146.5   67.05  5192.7   67.11
  5193.3   67.11  5235.3    67.3  5235.6    67.3  5280.2   67.41  5281.2   67.41
  5291.2   67.39  5321.2   67.33  5336.5    67.3  5338.5    67.3  5381.2   67.38
  5394.6   67.41  5414.6   67.45  5434.6   67.49  5459.6   67.54  5534.6   67.68
  5543.5    67.7  5554.3   67.44  5588.5    66.6  5628.5    66.7  5633.5    66.6
  5637.8   66.64  5893.5    68.9  5935.4    68.8  5999.4   68.71  6148.1    68.5
  6193.1      68  6223.1    66.6  6243.1    66.7  6283.1    66.5  6388.1    67.4
  6413.1    66.4  6468.1      67  6478.1    68.4  6503.1    74.2  6512.4    75.7
BR D #Mann= 7
  3554.4      .2  3616.6      .1  4963.4    .035  5050.5     .08  5554.3      .1
  5999.4     .99  6512.4      .2
BR D Banks=4963.4,5050.5
BC Design=,, 0 ,, 0 ,,,,,,
BC HTab HWMax=75.7
BC Use User HTab Curves=0
BC User HTab FreeFlow(D)= 0

Type RM Length L Ch R = 1 ,112116.9,530.75,526.8,521.82
BEGIN DESCRIPTION:
Downstream Section of Bridge/Culvert/Weir
END DESCRIPTION:
XS GIS Cut Line= 6
      3076941.99     13793058.72      3077088.26     13792129.28
      3077127.15      13791230.8      3077133.75     13791046.12
      3077146.99     13790527.82      3076990.97     13790143.77
#Sta/Elev= 30
  3554.4   69.79  3569.4   68.49  3584.4   65.89  3616.6   66.26  3819.4   65.89
    4253   67.59    4298   66.49    4481   66.59    4511   65.39    4561   66.59
  4839.2   66.32  4892.7   65.25  4963.4   66.95  4970.9   63.12  4980.3   59.93
  4992.9   58.14  5000.1   55.79  5006.3   57.53  5023.1   56.99  5041.3    62.9
  5050.5    66.9  5554.3   67.43  5633.5   66.59  5893.5   68.89  5999.4    68.7
  6148.1   68.49  6193.1   67.99  6223.1   66.59  6468.1   66.99  6512.4   75.69
#Mann= 7 , 1 , 0
  3554.4      .2       0  3616.6      .1       0  4963.4    .035       0
  5050.5     .08       0  5554.3      .1       0  5999.4     .99       0
  6512.4      .2       0
#XS Ineff= 2 , 0
       0    4951   66.66    5062       0      67
Permanent Ineff=
       F       F
Bank Sta=4963.4,5050.5
XS Rating Curve= 0 ,0
Exp/Cntr=0.5,0.3

Type RM Length L Ch R = 1 ,111590.1,246.1,250.07,254.74
BEGIN DESCRIPTION:
Cross Section 113688.0 - Interpolated
END DESCRIPTION:
XS GIS Cut Line= 5
      3077450.09      13793378.8      3077657.98     13792049.83
        3077606.     13791121.79      3077516.91     13790141.77
      3077435.24     13789941.31
#Sta/Elev= 30
  3255.1   68.57  3265.1   69.15  3295.1   67.33  3348.1   66.93  3405.1   65.51
  3425.1    66.5  3525.1   65.89  4305.1   65.36  4600.2   67.24  4800.2   65.87
  4890.2   67.21  4940.2   66.12  4950.2   64.89  4954.7   65.93  4977.1   57.81
  4994.4   56.65  4995.3      56  5002.1   55.23  5005.7    56.7  5027.8   58.59
  5050.3   67.26  5210.2   69.01  5350.2   65.68  6112.7    66.8  6165.2    66.9
  6613.8   67.53  6653.8   65.73  6693.8   66.45  6703.8   67.25  6730.2   73.57
#Mann= 6 , 1 , 0
  3255.1      .2       0  3348.1      .1       0  4954.7    .035       0
  5050.3     .14       0  6112.7     .08       0  6165.2      .2       0
#XS Ineff= 2 , 0
       0    4894    67.2    5054       0   67.23
Permanent Ineff=
       F       F
Bank Sta=4954.7,5050.3
XS Rating Curve= 0 ,0
Exp/Cntr=0.5,0.3