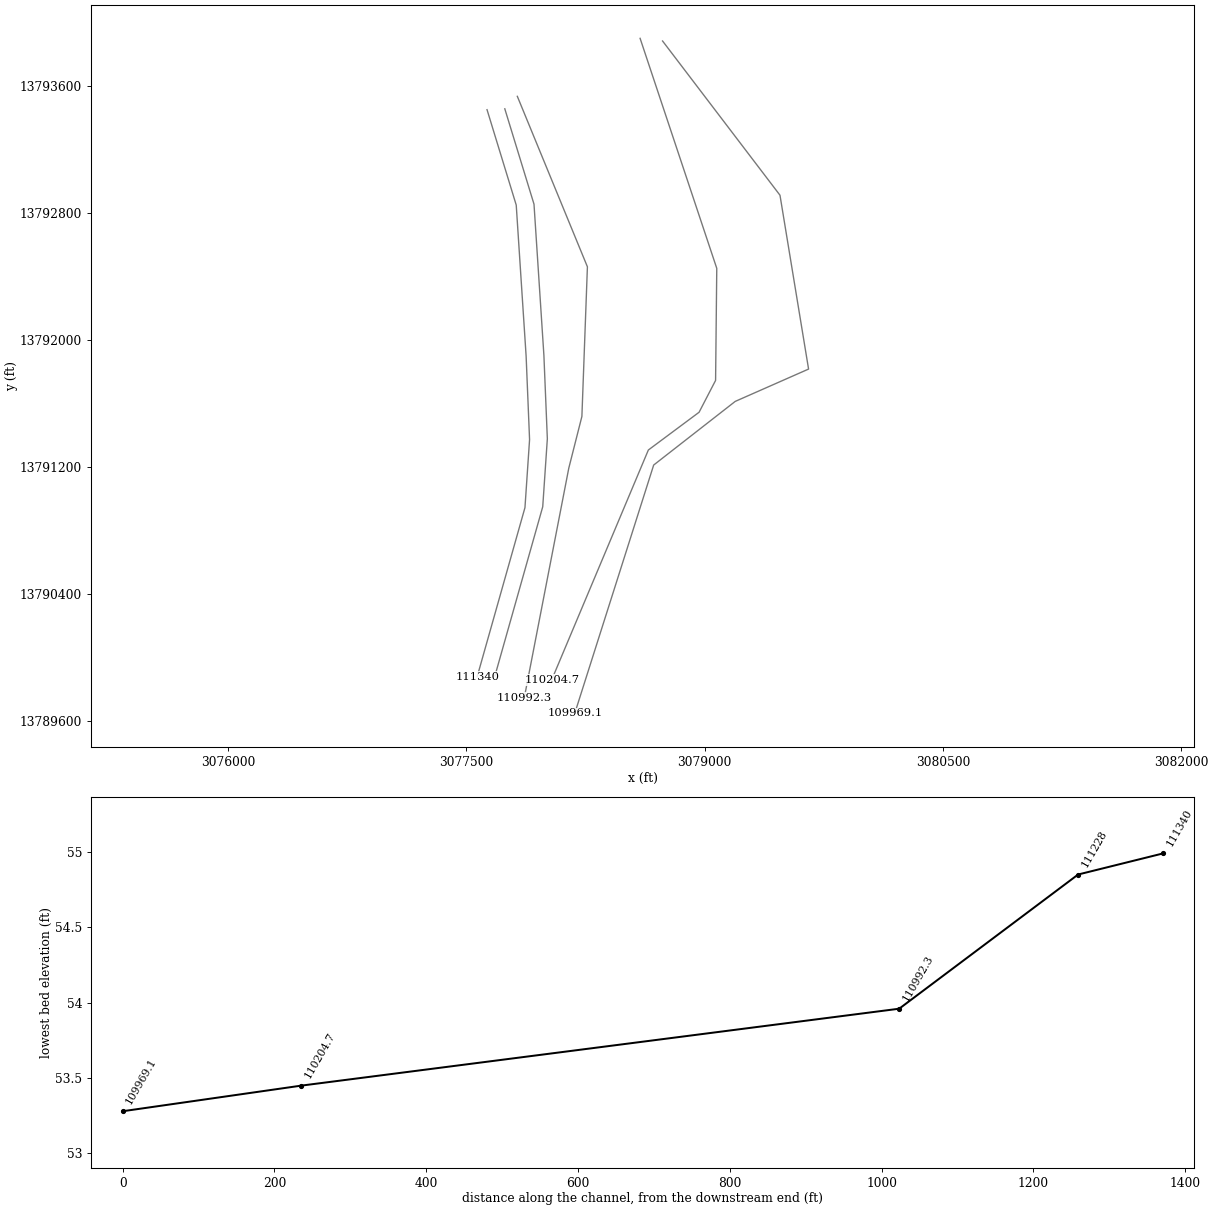
HEC-RAS study C100-00-00.prj: C100-00-00

--- C100-00-00.g01 (geometry) --- (continued)

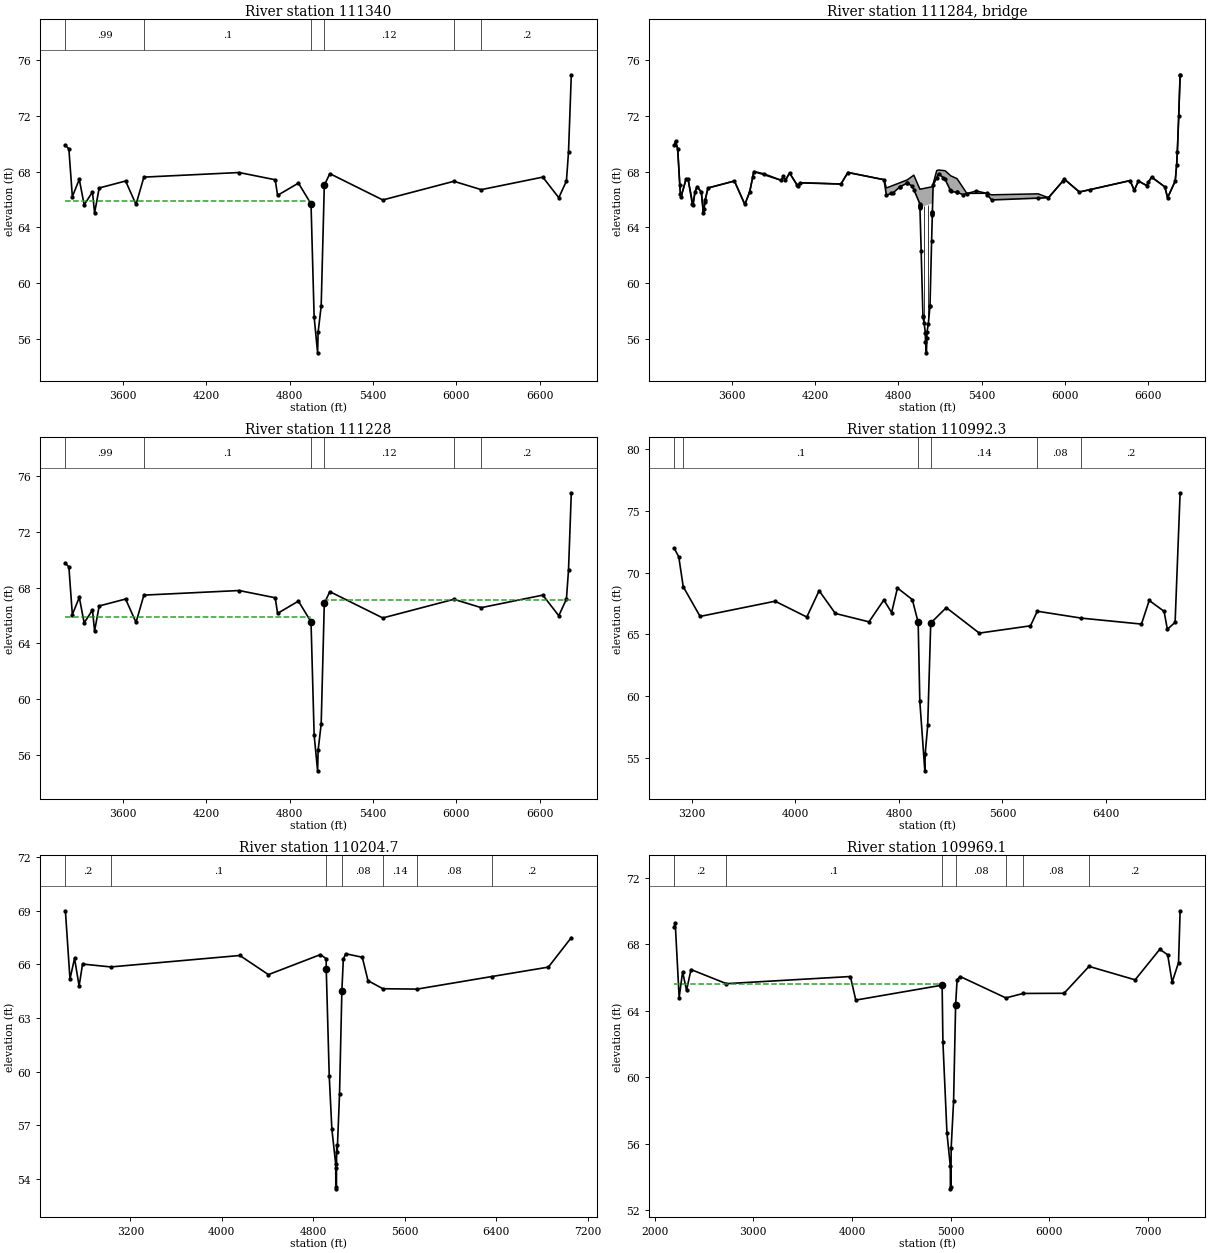
Type RM Length L Ch R = 1 ,111340  ,112,111.99,111.99
BEGIN DESCRIPTION:
Upstream Section of Bridge/Culvert/Weir
END DESCRIPTION:
XS GIS Cut Line= 6
      3077630.03     13793449.48      3077813.83     13792849.07
       3077876.1     13791897.94       3077897.8     13791372.84
      3077868.78     13790944.76      3077567.95     13789880.53
#Sta/Elev= 30
  3186.6   69.89  3211.6   69.64  3236.6   66.21  3286.6   67.45  3321.6   65.62
  3381.6   66.54  3396.6   65.03  3429.9   66.83  3619.9   67.33  3694.9   65.65
  3751.6   67.61  4436.9   67.94  4696.9   67.42    4714    66.3    4864   67.18
  4954.7   65.69  4977.1   57.57  5002.1   54.99  5005.7   56.46  5027.8   58.35
  5050.3   67.02  5089.9   67.86  5471.2   65.97  5982.9   67.31  6179.8   66.71
  6623.2   67.61  6738.2   66.13  6793.2   67.33  6808.2   69.41  6828.3   74.96
#Mann= 6 , 1 , 0
  3186.6     .99       0  3751.6      .1       0  4954.7    .035       0
  5050.3     .12       0  5982.9     .08       0  6179.8      .2       0
#XS Ineff= 2 , 0
       0    4945   65.92    5055       0   67.09
Permanent Ineff=
       F       F
Bank Sta=4954.7,5050.3
XS Rating Curve= 0 ,0
Exp/Cntr=0.5,0.3

Type RM Length L Ch R = 3 ,111284  ,,,
BEGIN DESCRIPTION:
FONDREN STREET
Structure ID: C00-53
END DESCRIPTION:
Bridge Culvert--1,0,-1,-1, 0
Deck Dist Width WeirC Skew NumUp NumDn MinLoCord MaxHiCord MaxSubmerge Is_Ogee
10,92,2.6,0, 60, 60, , , 0.95, 0, 1,1,,
  3186.6  3196.6  3211.6  3226.6  3231.6  3236.6  3271.6  3286.6  3321.6  3336.6
  3351.6  3381.6  3396.6  3409.9  3429.9  3619.9  3694.9  3729.9  3759.9  3956.9
  3971.9  3986.9  4016.9  4076.9  4091.9  4386.9  4436.9  4696.9    4714    4864
  4911.3  4954.7 4955.41 5044.89    5045  5050.3  5076.4  5089.9  5136.5    5178
  5222.4  5293.3  5436.7  5471.2  5806.6  5880.6  5995.6  6103.2  6468.2  6498.2
  6528.2  6588.2  6623.2  6718.2  6738.2  6793.2  6803.2  6808.2  6818.2  6828.3
   69.88   70.17   69.63   67.06   66.42    66.2   67.46   67.44   65.61   66.55
   66.91   66.53   65.02   65.98   66.82   67.32   65.64   66.54      68   67.37
   67.66   67.36    67.9   66.94    67.2   67.11   67.94   67.42   66.82    67.4
   67.74   66.74   66.73   66.91   66.91   67.11   68.07   68.11   68.06   67.69
   67.49   66.43   66.44   66.33    66.4   66.12   67.45   66.53   67.35   66.65
   67.32   66.99    67.6    66.9   66.12   67.32   68.47    69.4   71.96   74.95
   69.88   70.17   69.63   67.06   66.42    66.2   67.46   67.44   65.61   66.55
   66.91   66.53   65.02   65.98   66.82   67.32   65.64   66.54      68   67.37
   67.66   67.36    67.9   66.93   67.19    67.1   67.93   67.41   66.29   67.17
   66.71   65.68   65.43   65.71   65.07   67.01   67.56   67.85   67.44   66.58
    66.5   66.42   66.43   65.96   66.09   66.12   67.45   66.53   67.35   66.65
   67.32   66.99    67.6    66.9   66.12   67.32   68.47    69.4   71.96   74.95
  3186.6  3196.6  3211.6  3226.6  3231.6  3236.6  3271.6  3286.6  3321.6  3336.6
  3351.6  3381.6  3396.6  3409.9  3429.9  3619.9  3694.9  3729.9  3759.9  3956.9
  3971.9  3986.9  4016.9  4076.9  4091.9  4386.9  4436.9  4696.9    4714    4864
  4911.3  4954.7 4955.41 5044.89    5045  5050.3  5076.4  5089.9  5136.5    5178
  5222.4  5293.3  5436.7  5471.2  5806.6  5880.6  5995.6  6103.2  6468.2  6498.2
  6528.2  6588.2  6623.2  6718.2  6738.2  6793.2  6803.2  6808.2  6818.2  6828.3
   69.88   70.17   69.63   67.06   66.42    66.2   67.46   67.44   65.61   66.55
   66.91   66.53   65.02   65.98   66.82   67.32   65.64   66.54      68   67.37
   67.66   67.36    67.9   66.94    67.2   67.11   67.94   67.42   66.82    67.4
   67.74   66.74   66.73   66.91   66.91   67.11   68.07   68.11   68.06   67.69
   67.49   66.43   66.44   66.33    66.4   66.12   67.45   66.53   67.35   66.65
   67.32   66.99    67.6    66.9   66.12   67.32   68.47    69.4   71.96   74.95
   69.79   70.08   69.54   66.97   66.33   66.11   67.37   67.35   65.52   66.46
   66.82   66.44   64.93   65.89   66.73   67.23   65.55   66.45   67.91   67.28
   67.57   67.27   67.81   66.84    67.1   67.01   67.84   67.32    66.2   67.08
   66.62   65.59   65.34   65.62   64.98   66.92   67.47   67.76   67.35   66.49
   66.41   66.33   66.34   65.87      66   66.03   67.36   66.44   67.26   66.56
   67.23    66.9   67.51   66.81   66.03   67.23   68.38   69.31   71.87   74.86
Pier Skew, UpSta & Num, DnSta & Num=  ,4985.9, 2 ,4985.9, 2 , 0 , 0 , 0 ,,
     1.4     1.4
   56.05   66.59
     1.4     1.4
   55.96    66.5
Pier Skew, UpSta & Num, DnSta & Num=  ,5015.4, 2 ,5015.4, 2 , 0 , 0 , 0 ,,
     1.4     1.4
   55.98   66.65
     1.4     1.4
   55.89   66.56
Abutment Skew #Up #Dn= , 2 , 2
  4955.3  4977.1
   65.53   57.56
  4955.3  4977.1
   65.44   57.47
Abutment Skew #Up #Dn= , 2 , 2
  5027.8 5045.09
   58.34   65.71
  5027.8 5045.09
   58.25   65.62
BR Coef= 1 , 1 , 0 ,1.25, 0 ,,,0.8,0,2,0,
WSPro=,,,, 1 ,,,, 0 ,,,, 0 ,,,,-1 ,-1 ,-1 , 0 , 0 , 0 , 0 , 0
BR U #Sta/Elev= 104
  3186.6   69.88  3196.6   70.17  3211.6   69.63  3226.6   67.06  3231.6   66.42
  3236.6    66.2  3271.6   67.46  3286.6   67.44  3316.6   65.69  3321.6   65.61
  3336.6   66.55  3351.6   66.91  3381.6   66.53  3396.6   65.02  3401.6   65.29
  3406.6   65.78  3409.9   65.98  3429.9   66.82  3619.9   67.32  3694.9   65.64
  3729.9   66.54  3751.6    67.6  3759.9      68  3831.9   67.84  3956.9   67.37
  3971.9   67.66  3986.9   67.36  4016.9    67.9  4071.5   67.02  4076.9   66.93
  4091.9   67.19  4386.9    67.1  4436.9   67.93  4696.9   67.41    4714   66.29
  4748.7   66.43  4763.5   66.49  4812.3    66.9  4813.3   66.91  4861.3   67.16
    4864   67.17  4901.5   66.94  4911.3   66.71  4954.7   65.68 4954.99   65.58
  4955.1   65.54 4955.21    65.5  4955.3   65.47 4955.41   65.43  4955.5    65.4
  4964.2   62.32    4977    57.6  4977.1   57.56  4985.9   57.11  4994.4    56.4
  4995.3   55.75  5002.1   54.98  5005.3   56.01  5005.7   56.45  5015.4   57.02
  5027.6   58.32  5027.8   58.34  5039.4   63.01 5044.59   64.91  5044.7   64.95
 5044.81      65 5044.89   65.02    5045   65.07  5045.1    65.1  5050.3   67.01
  5076.4   67.56  5089.9   67.85  5121.9   67.57  5136.5   67.44  5174.6   66.65
    5178   66.58  5222.2    66.5  5222.4    66.5  5266.5   66.35  5293.3   66.42
  5361.7    66.6  5436.7   66.43  5441.2   66.33  5471.2   65.96  5806.6   66.09
  5880.6   66.12  5982.9    67.3  5995.6   67.45  6103.2   66.53  6179.8    66.7
  6468.2   67.35  6498.2   66.65  6528.2   67.32  6588.2   66.99  6598.2   67.23
  6623.2    67.6  6718.2    66.9  6738.2   66.12  6793.2   67.32  6803.2   68.47
  6808.2    69.4  6818.2   71.96  6828.2   74.94  6828.3   74.95
BR U #Mann= 6
  3186.6     .99  3751.6      .1  4954.7    .035  5050.3     .12  5982.9     .08
  6179.8      .2
BR U Banks=4954.7,5050.3
BR D #Sta/Elev= 104
  3186.6   69.79  3196.6   70.08  3211.6   69.54  3226.6   66.97  3231.6   66.33
  3236.6   66.11  3271.6   67.37  3286.6   67.35  3316.6    65.6  3321.6   65.52
  3336.6   66.46  3351.6   66.82  3381.6   66.44  3396.6   64.93  3401.6    65.2
  3406.6   65.69  3409.9   65.89  3429.9   66.73  3619.9   67.23  3694.9   65.55
  3729.9   66.45  3751.6   67.51  3759.9   67.91  3831.9   67.75  3956.9   67.28
  3971.9   67.57  3986.9   67.27  4016.9   67.81  4071.5   66.93  4076.9   66.84
  4091.9    67.1  4386.9   67.01  4436.9   67.84  4696.9   67.32    4714    66.2
  4748.7   66.34  4763.5    66.4  4812.3   66.81  4813.3   66.82  4861.3   67.07
    4864   67.08  4901.5   66.85  4911.3   66.62  4954.7   65.59 4954.99   65.49
  4955.1   65.45 4955.21   65.41  4955.3   65.38 4955.41   65.34  4955.5   65.31
  4964.2   62.23    4977   57.51  4977.1   57.47  4985.9   57.02  4994.4   56.31
  4995.3   55.66  5002.1   54.89  5005.3   55.92  5005.7   56.36  5015.4   56.93
  5027.6   58.23  5027.8   58.25  5039.4   62.92 5044.59   64.82  5044.7   64.86
 5044.81   64.91 5044.89   64.93    5045   64.98  5045.1   65.01  5050.3   66.92
  5076.4   67.47  5089.9   67.76  5121.9   67.48  5136.5   67.35  5174.6   66.56
    5178   66.49  5222.2   66.41  5222.4   66.41  5266.5   66.26  5293.3   66.33
  5361.7   66.51  5436.7   66.34  5441.2   66.24  5471.2   65.87  5806.6      66
  5880.6   66.03  5982.9   67.21  5995.6   67.36  6103.2   66.44  6179.8   66.61
  6468.2   67.26  6498.2   66.56  6528.2   67.23  6588.2    66.9  6598.2   67.14
  6623.2   67.51  6718.2   66.81  6738.2   66.03  6793.2   67.23  6803.2   68.38
  6808.2   69.31  6818.2   71.87  6828.2   74.85  6828.3   74.86
BR D #Mann= 6
  3186.6     .99  3751.6      .1  4954.7    .035  5050.3     .12  5982.9     .08
  6179.8      .2
BR D Banks=4954.7,5050.3
BC Design=,, 0 ,, 0 ,,,,,,
BC HTab HWMax=74.96
BC Use User HTab Curves=0
BC User HTab FreeFlow(D)= 0

Type RM Length L Ch R = 1 ,111228  ,239.43,235.74,232.09
BEGIN DESCRIPTION:
Downstream Section of Bridge/Culvert/Weir
END DESCRIPTION:
XS GIS Cut Line= 6
      3077741.89     13793454.98      3077925.69     13792854.57
      3077987.96     13791903.44      3078009.66     13791378.34
      3077980.64     13790950.26      3077679.82     13789886.02
#Sta/Elev= 30
  3186.6   69.75  3211.6    69.5  3236.6   66.07  3286.6   67.31  3321.6   65.48
  3381.6    66.4  3396.6   64.89  3429.9   66.69  3619.9   67.19  3694.9   65.51
  3751.6   67.47  4436.9    67.8  4696.9   67.28    4714   66.16    4864   67.04
  4954.7   65.55  4977.1   57.43  5002.1   54.85  5005.7   56.32  5027.8   58.21
  5050.3   66.88  5089.9   67.72  5471.2   65.83  5982.9   67.17  6179.8   66.57
  6623.2   67.47  6738.2   65.99  6793.2   67.19  6808.2   69.27  6828.3   74.82
#Mann= 6 , 1 , 0
  3186.6     .99       0  3751.6      .1       0  4954.7    .035       0
  5050.3     .12       0  5982.9     .08       0  6179.8      .2       0
#XS Ineff= 2 , 0
       0    4945   65.92    5055       0   67.09
Permanent Ineff=
       F       F
Bank Sta=4954.7,5050.3
XS Rating Curve= 0 ,0
Exp/Cntr=0.5,0.3

Type RM Length L Ch R = 1 ,110992.3,809.6,787.6,765.64
BEGIN DESCRIPTION:
Cross Section  113089.1
END DESCRIPTION:
XS GIS Cut Line= 5
      3077820.75     13793533.44      3078261.84      13792460.5
      3078227.13      13791518.8      3078144.67     13791193.33
      3077864.66     13789748.98
#Sta/Elev= 30
  3063.6   71.96  3098.6   71.28  3133.3   68.85  3263.6   66.45  3843.3   67.68
  4088.3    66.4  4183.3   68.53  4308.6   66.69  4568.6   66.01  4683.6   67.78
  4743.6   66.76  4788.6   68.75  4903.6   67.81  4948.7   65.97  4961.5   59.59
  5000.2   53.96  5003.3   55.35  5022.4   57.63  5045.9   65.91    5166   67.16
    5421    65.1  5816.7   65.69  5869.2   66.87  6210.8   66.31  6674.2   65.83
  6734.2   67.74  6849.2   66.86  6874.2   65.41  6934.2   65.97    6973   76.45
#Mann= 6 , 1 , 0
  3063.6      .2       0  3133.3      .1       0  4948.7    .035       0
  5045.9     .14       0  5869.2     .08       0  6210.8      .2       0
Bank Sta=4948.7,5045.9
XS Rating Curve= 0 ,0
Exp/Cntr=0.3,0.1

Type RM Length L Ch R = 1 ,110204.7,349.92,235.58,169.53
BEGIN DESCRIPTION:
Cross Section 112305.0 - Interpolated
END DESCRIPTION:
XS GIS Cut Line= 6
      3078593.45     13793898.51      3079076.03     13792450.75
      3079068.61     13791745.43      3078964.67     13791544.98
      3078645.42      13791307.4      3078036.62     13789859.64
#Sta/Elev= 30
  2631.8      69  2671.8   65.18  2711.8   66.34  2751.8   64.79  2781.8   66.02
  3029.3   65.86  4157.9    66.5  4407.9   65.43  4863.2   66.55  4913.2   66.32
 4913.75   65.72 4939.95   59.76 4962.75    56.8  4996.7   54.82  4997.5   53.45
  5002.9   53.56 5003.25   54.59 5005.25   55.91 5009.55   55.52 5029.85   58.74
  5050.4   64.52  5063.2   66.29  5083.2    66.6    5229    66.4    5279   65.09
  5409.5   64.64  5708.1   64.62  6359.7   65.32    6857   65.85  7057.5    67.5
#Mann= 7 , 1 , 0
  2631.8      .2       0  3029.3      .1       0 4913.75    .035       0
  5050.4     .08       0  5409.5     .14       0  5708.1     .08       0
  6359.7      .2       0
Bank Sta=4913.75,5050.4
XS Rating Curve= 0 ,0
Exp/Cntr=0.5,0.3

Type RM Length L Ch R = 1 ,109969.1,111.84,123.82,119.36
BEGIN DESCRIPTION:
Upstream Section of Bridge/Culvert/Weir
END DESCRIPTION:
XS GIS Cut Line= 6
      3078734.88     13793881.75      3079473.91     13792911.09
      3079653.87     13791816.83      3079192.21     13791613.32
      3078678.97     13791212.82      3078182.18     13789649.73
#Sta/Elev= 30
  2198.8   69.08  2208.8   69.32  2248.8    64.8  2283.8   66.35  2323.8   65.24
  2368.8   66.49  2727.2   65.64  3983.9   66.07  4038.9   64.65 4913.75   65.55
 4921.65   62.13 4962.75   56.63  4996.7   54.65  4997.5   53.28  5002.9   53.39
 5005.25   55.74 5029.85   58.57  5050.4   64.35  5065.3   65.87 5096.45   66.07
    5560   64.78  5734.9   65.05  6149.4   65.06  6402.4   66.68  6869.4   65.87
  7119.4   67.71  7199.4   67.38  7244.4   65.73  7309.4   66.91  7325.4   70.03
#Mann= 7 , 1 , 0
  2198.8      .2       0  2727.2      .1       0 4913.75    .035       0
  5050.4     .08       0    5560     .14       0  5734.9     .08       0
  6402.4      .2       0
#XS Ineff= 2 , 0
       0    4900   65.63    5060       0   65.16
Permanent Ineff=
       F       F
Bank Sta=4913.75,5050.4
XS Rating Curve= 0 ,0
Exp/Cntr=0.5,0.3