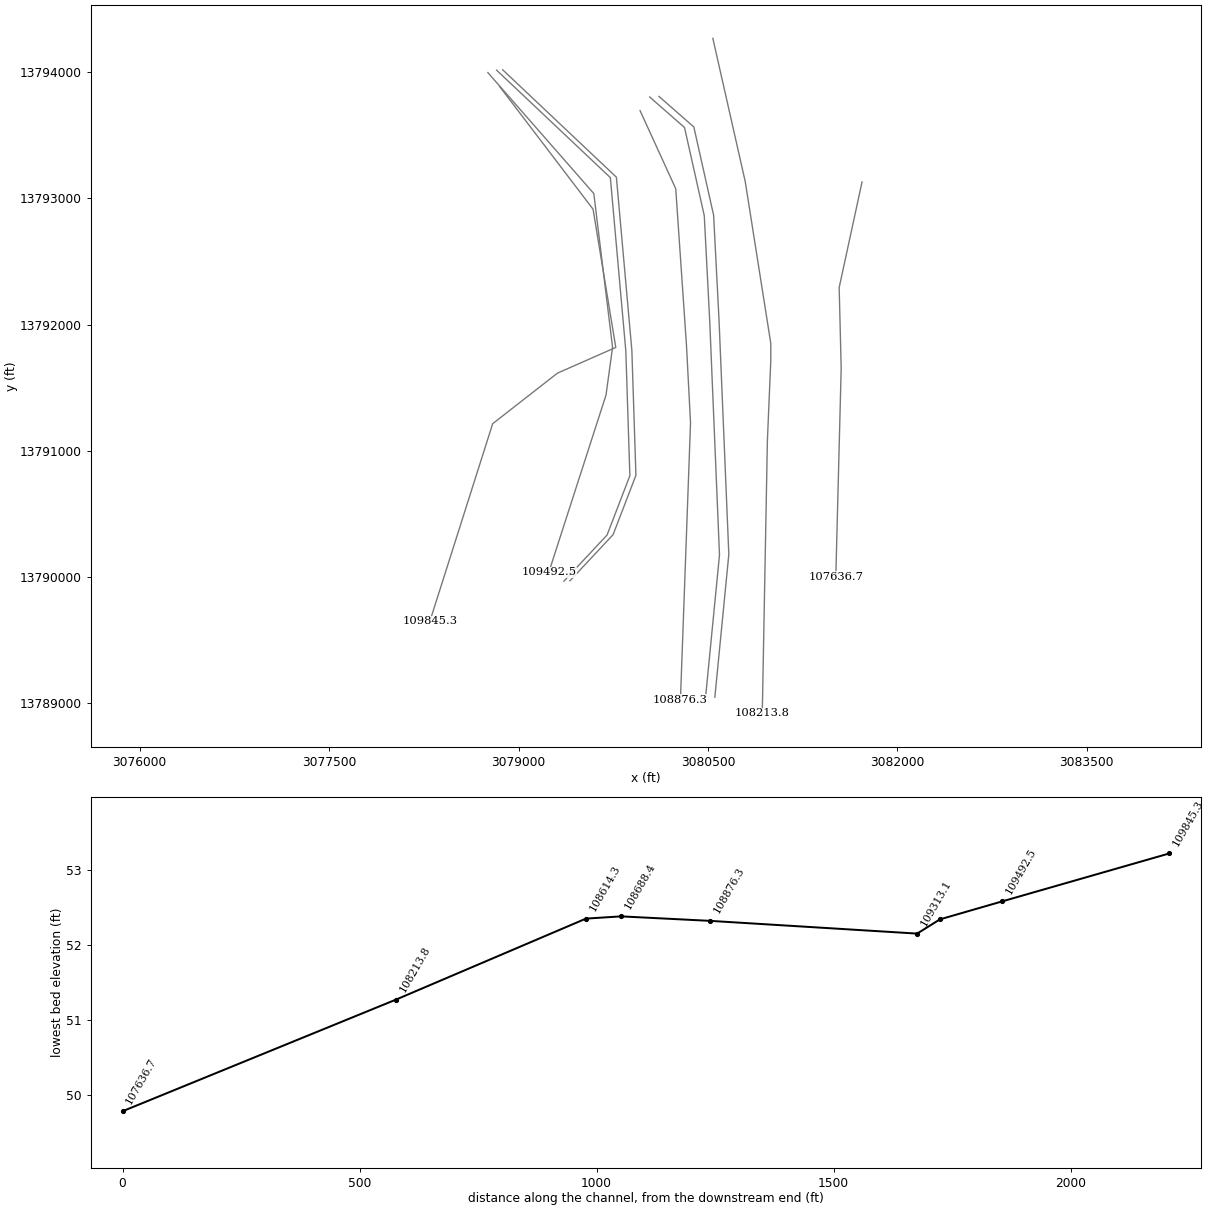
HEC-RAS study C100-00-00.prj: C100-00-00

--- C100-00-00.g01 (geometry) --- (continued)

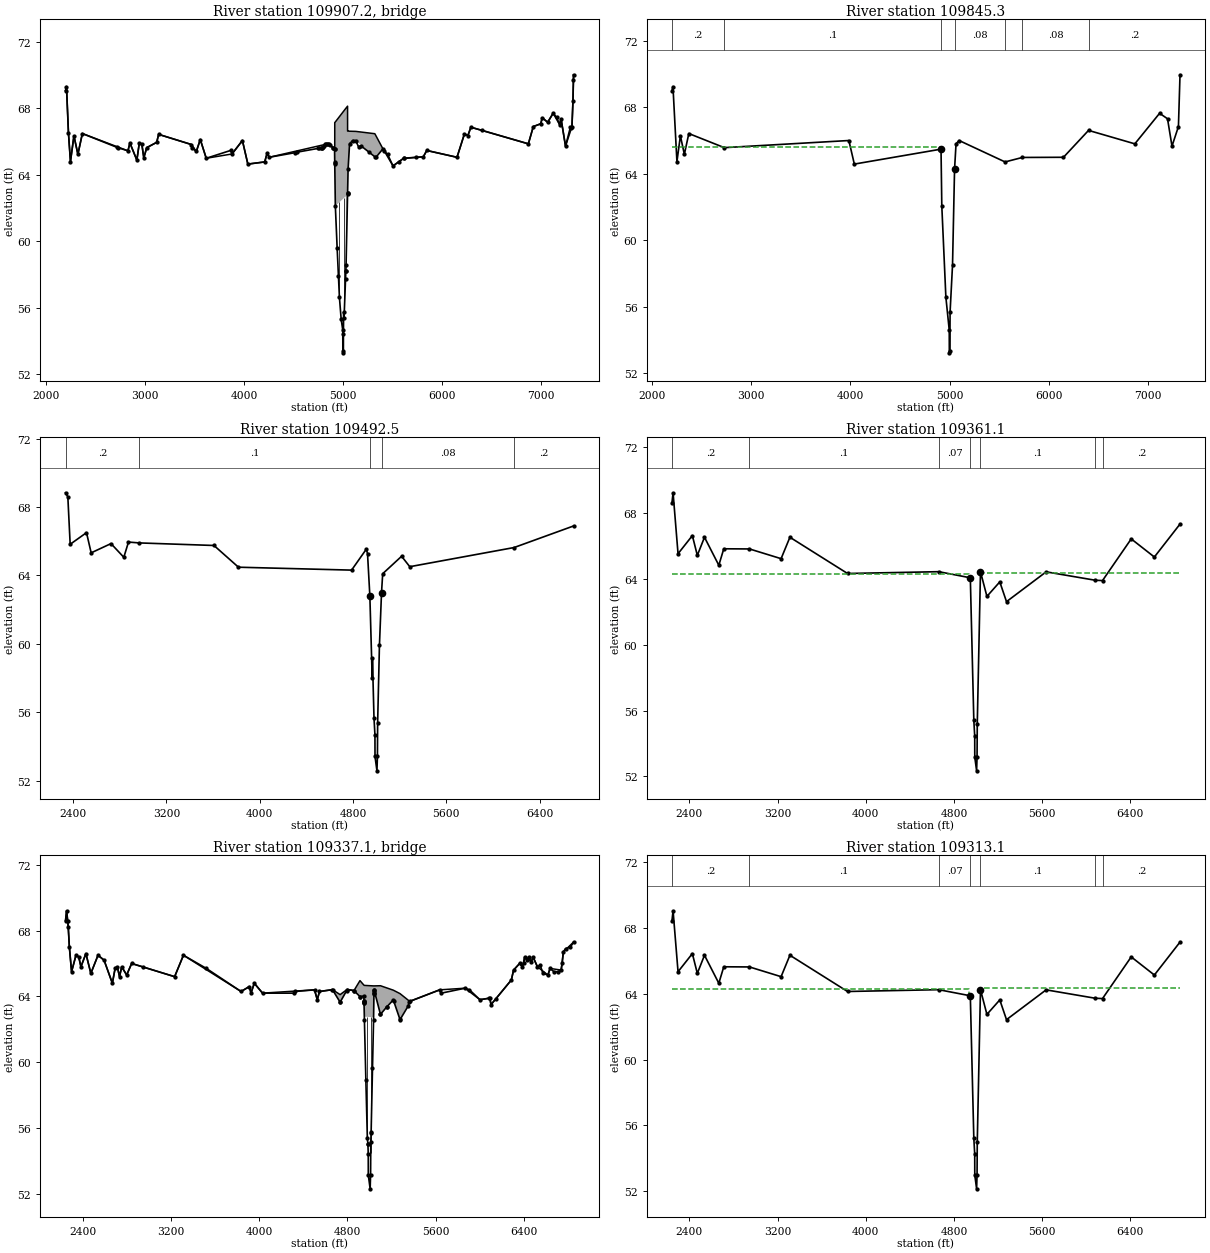
Type RM Length L Ch R = 3 ,109907.2,,,
BEGIN DESCRIPTION:
OREM DRIVE - Skewed 60 Degrees
Structure ID: C00-52
END DESCRIPTION:
Bridge Culvert--1,0,-1,-1, 0
Deck Dist Width WeirC Skew NumUp NumDn MinLoCord MaxHiCord MaxSubmerge Is_Ogee
10,96,2.6,0, 60, 60, , , 0.95, 0, 1,1,,
  2198.8  2208.8  2228.8  2248.8  2283.8  2323.8  2368.8  2828.8  2848.8  2918.8
  2943.8  2968.8  2988.8  3018.8  3118.8  3138.8  3468.8  3518.9  3558.9  3618.9
  3878.9  3983.9  4038.9  4208.9  4233.9  4253.9  4852.3 4913.75 4915.59  4915.7
 4921.65 5027.59  5027.7  5045.2 5045.31  5050.4  5065.3 5127.55  5320.3  5398.4
  5503.4  5613.4  5809.4  5844.4  6149.4  6224.4  6259.4  6289.4  6869.4  6919.4
  6994.4  7009.4  7064.4  7119.4  7184.4  7199.4  7244.4  7309.4  7319.4  7325.4
   69.07   69.31   66.49   64.79   66.34   65.23   66.48   65.44   65.91   64.88
   65.92   65.85   65.02   65.63   65.95   66.43   65.82    65.4   66.12   64.99
   65.25   66.06   64.64   64.77   65.31   65.05   65.87   65.55   65.64   67.14
   67.18      68      68   68.13   66.63   66.63   66.62   66.61   66.47    65.6
   64.53      65   65.08   65.46   65.05   66.46   66.36   66.86   65.86    66.9
   67.07   67.43   67.16    67.7   67.02   67.37   65.72    66.9   68.44   70.02
   69.07   69.31   66.49   64.79   66.34   65.23   66.48   65.44   65.91   64.88
   65.92   65.85   65.02   65.63   65.95   66.43   65.82    65.4   66.12   64.99
   65.25   66.06   64.64   64.77   65.31   65.05   65.86   65.54   64.74    64.7
   62.12    62.7   58.22   62.88   62.91   64.34   65.86   66.06   65.08   65.53
   64.53      65   65.08   65.46   65.05   66.46   66.36   66.86   65.86    66.9
   67.07   67.43   67.16    67.7   67.02   67.37   65.72    66.9   68.44   70.02
  2198.8  2208.8  2228.8  2248.8  2283.8  2323.8  2368.8  2828.8  2848.8  2918.8
  2943.8  2968.8  2988.8  3018.8  3118.8  3138.8  3468.8  3518.9  3558.9  3618.9
  3878.9  3983.9  4038.9  4208.9  4233.9  4253.9  4852.3 4913.75 4915.59  4915.7
 4921.65 5027.59  5027.7  5045.2 5045.31  5050.4  5065.3 5127.55  5320.3  5398.4
  5503.4  5613.4  5809.4  5844.4  6149.4  6224.4  6259.4  6289.4  6869.4  6919.4
  6994.4  7009.4  7064.4  7119.4  7184.4  7199.4  7244.4  7309.4  7319.4  7325.4
   69.07   69.31   66.49   64.79   66.34   65.23   66.48   65.44   65.91   64.88
   65.92   65.85   65.02   65.63   65.95   66.43   65.82    65.4   66.12   64.99
   65.25   66.06   64.64   64.77   65.31   65.05   65.87   65.55   65.64   67.14
   67.18      68      68   68.13   66.63   66.63   66.62   66.61   66.47    65.6
   64.53      65   65.08   65.46   65.05   66.46   66.36   66.86   65.86    66.9
   67.07   67.43   67.16    67.7   67.02   67.37   65.72    66.9   68.44   70.02
   69.04   69.28   66.46   64.76   66.31    65.2   66.45   65.41   65.88   64.85
   65.89   65.82   64.99    65.6   65.92    66.4   65.79   65.37   66.09   64.96
   65.22   66.03   64.61   64.74   65.28   65.02   65.83   65.51   64.71   64.67
   62.09   62.67   58.19   62.85   62.88   64.31   65.83   66.03   65.05    65.5
    64.5   64.97   65.05   65.43   65.02   66.43   66.33   66.83   65.83   66.87
   67.04    67.4   67.13   67.67   66.99   67.34   65.69   66.87   68.41   69.99
Pier Skew, UpSta & Num, DnSta & Num=  ,4962.8, 2 ,4962.8, 2 , 0 , 0 , 0 ,,
     1.4     1.4
   55.57   63.21
     1.4     1.4
   55.54   63.18
Pier Skew, UpSta & Num, DnSta & Num=  ,5005.3, 2 ,5005.3, 2 , 0 , 0 , 0 ,,
     1.4     1.4
   54.27   63.53
     1.4     1.4
   54.24    63.5
Abutment Skew #Up #Dn= , 2 , 2
  4900.2 4952.85
   65.61   57.91
  4900.2 4952.85
   65.58   57.88
Abutment Skew #Up #Dn= , 2 , 2
 5024.55 5027.79
   57.72    62.7
 5024.55 5027.79
   57.69   62.67
BR Coef= 1 , 1 , 0 ,1.25, 0 ,,,0.8,0,2,0,
WSPro=,,,, 1 ,,,, 0 ,,,, 0 ,,,,-1 ,-1 ,-1 , 0 , 0 , 0 , 0 , 0
BR U #Sta/Elev= 110
  2198.8   69.07  2208.8   69.31  2228.8   66.49  2248.8   64.79  2283.8   66.34
  2323.8   65.23  2368.8   66.48  2713.8   65.66  2727.2   65.63  2828.8   65.44
  2848.8   65.91  2918.8   64.88  2943.8   65.92  2968.8   65.85  2988.8   65.02
  3018.8   65.63  3118.8   65.95  3138.8   66.43  3468.8   65.82  3478.9    65.6
  3518.9    65.4  3558.9   66.12  3618.9   64.99  3863.9   65.46  3878.9   65.25
  3983.9   66.06  4038.9   64.64  4208.9   64.77  4233.9   65.31  4253.9   65.05
  4516.7   65.33  4536.7   65.36  4743.3   65.58  4753.3   65.59  4773.3   65.61
  4788.3   65.63  4791.4   65.63  4798.3   65.68  4808.3   65.75 4820.45   65.83
  4823.3   65.83  4838.3   65.85  4852.3   65.86  4858.3   65.83  4868.3   65.78
 4900.31   65.61  4900.4   65.61  4913.3   65.54 4913.75   65.54 4915.59   64.74
  4915.7    64.7 4915.81   64.65 4921.65   62.12 4939.95   59.58 4952.85   57.91
 4962.75   56.62 4980.35    55.3  4996.7   54.64  4997.5   53.27  5002.9   53.38
 5003.25   54.41 5005.25   55.73 5009.55   55.34 5024.55   57.72 5027.59    58.2
  5027.7   58.22 5029.85   58.56 5045.09   62.85  5045.2   62.88 5045.31   62.91
  5050.4   64.34  5065.3   65.86 5096.45   66.06 5127.55   66.06  5155.6   65.68
 5180.15   65.74  5259.4   65.37  5320.3   65.08  5329.6   65.04  5398.4   65.53
  5416.1   65.42  5448.4   65.23  5503.4   64.53    5560   64.77  5613.4      65
  5614.4   64.98  5734.9   65.04  5809.4   65.08  5844.4   65.46  6149.4   65.05
  6224.4   66.46  6259.4   66.36  6289.4   66.86  6402.4   66.67  6869.4   65.86
  6919.4    66.9  6994.4   67.07  7009.4   67.43  7064.4   67.16  7119.4    67.7
  7154.4   67.46  7184.4   67.02  7199.4   67.37  7244.4   65.72  7294.4   66.88
  7304.4    66.8  7309.4    66.9  7319.4   68.44  7324.4    69.7  7325.4   70.02
BR U #Mann= 7
  2198.8      .2  2727.2      .1 4913.75    .035  5050.4     .08    5560     .14
  5734.9     .08  6402.4      .2
BR U Banks=4913.75,5050.4
BR D #Sta/Elev= 110
  2198.8   69.04  2208.8   69.28  2228.8   66.46  2248.8   64.76  2283.8   66.31
  2323.8    65.2  2368.8   66.45  2713.8   65.63  2727.2    65.6  2828.8   65.41
  2848.8   65.88  2918.8   64.85  2943.8   65.89  2968.8   65.82  2988.8   64.99
  3018.8    65.6  3118.8   65.92  3138.8    66.4  3468.8   65.79  3478.9   65.57
  3518.9   65.37  3558.9   66.09  3618.9   64.96  3863.9   65.43  3878.9   65.22
  3983.9   66.03  4038.9   64.61  4208.9   64.74  4233.9   65.28  4253.9   65.02
  4516.7    65.3  4536.7   65.33  4743.3   65.55  4753.3   65.56  4773.3   65.58
  4788.3    65.6  4791.4    65.6  4798.3   65.65  4808.3   65.72 4820.45    65.8
  4823.3    65.8  4838.3   65.82  4852.3   65.83  4858.3    65.8  4868.3   65.75
 4900.31   65.58  4900.4   65.58  4913.3   65.51 4913.75   65.51 4915.59   64.71
  4915.7   64.67 4915.81   64.62 4921.65   62.09 4939.95   59.55 4952.85   57.88
 4962.75   56.59 4980.35   55.27  4996.7   54.61  4997.5   53.24  5002.9   53.35
 5003.25   54.38 5005.25    55.7 5009.55   55.31 5024.55   57.69 5027.59   58.17
  5027.7   58.19 5029.85   58.53 5045.09   62.82  5045.2   62.85 5045.31   62.88
  5050.4   64.31  5065.3   65.83 5096.45   66.03 5127.55   66.03  5155.6   65.65
 5180.15   65.71  5259.4   65.34  5320.3   65.05  5329.6   65.01  5398.4    65.5
  5416.1   65.39  5448.4    65.2  5503.4    64.5    5560   64.74  5613.4   64.97
  5614.4   64.95  5734.9   65.01  5809.4   65.05  5844.4   65.43  6149.4   65.02
  6224.4   66.43  6259.4   66.33  6289.4   66.83  6402.4   66.64  6869.4   65.83
  6919.4   66.87  6994.4   67.04  7009.4    67.4  7064.4   67.13  7119.4   67.67
  7154.4   67.43  7184.4   66.99  7199.4   67.34  7244.4   65.69  7294.4   66.85
  7304.4   66.77  7309.4   66.87  7319.4   68.41  7324.4   69.67  7325.4   69.99
BR D #Mann= 7
  2198.8      .2  2727.2      .1 4913.75    .035  5050.4     .08    5560     .14
  5734.9     .08  6402.4      .2
BR D Banks=4913.75,5050.4
BC Design=,, 0 ,, 0 ,,,,,,
BC HTab HWMax=70.03
BC Use User HTab Curves=0
BC User HTab FreeFlow(D)= 0

Type RM Length L Ch R = 1 ,109845.3,234.14,352.75,445.7
BEGIN DESCRIPTION:
Downstream Section of Bridge/Culvert/Weir
END DESCRIPTION:
XS GIS Cut Line= 6
      3078850.87     13793883.65      3079589.89     13792912.99
      3079769.85     13791818.73      3079308.19     13791615.22
      3078794.95     13791214.72      3078298.16     13789651.63
#Sta/Elev= 30
  2198.8   69.02  2208.8   69.26  2248.8   64.74  2283.8   66.29  2323.8   65.18
  2368.8   66.43  2727.2   65.58  3983.9   66.01  4038.9   64.59 4913.75   65.49
 4921.65   62.07 4962.75   56.57  4996.7   54.59  4997.5   53.22  5002.9   53.33
 5005.25   55.68 5029.85   58.51  5050.4   64.29  5065.3   65.81 5096.45   66.01
    5560   64.72  5734.9   64.99  6149.4      65  6402.4   66.62  6869.4   65.81
  7119.4   67.65  7199.4   67.32  7244.4   65.67  7309.4   66.85  7325.4   69.97
#Mann= 7 , 1 , 0
  2198.8      .2       0  2727.2      .1       0 4913.75    .035       0
  5050.4     .08       0    5560     .14       0  5734.9     .08       0
  6402.4      .2       0
#XS Ineff= 2 , 0
       0    4900   65.63    5060       0   65.16
Permanent Ineff=
       F       F
Bank Sta=4913.75,5050.4
XS Rating Curve= 0 ,0
Exp/Cntr=0.5,0.3

Type RM Length L Ch R = 1 ,109492.5,123.13,131.43,138.43
BEGIN DESCRIPTION:
Cross Section 111586.0 - Interpolated
END DESCRIPTION:
XS GIS Cut Line= 5
      3078756.79     13793995.03      3079595.74     13793037.28
      3079744.23     13791819.68      3079692.26     13791441.03
      3079239.37     13790037.82
#Sta/Elev= 30
  2334.9   68.83  2354.9   68.59  2374.9   65.82  2514.9    66.5  2554.9   65.32
  2724.9   65.86  2834.9   65.06  2874.9   65.95    2966    65.9  3608.1   65.75
  3818.1   64.48  4788.1   64.31  4914.8   65.54  4924.8   65.27  4944.8   62.79
  4964.8   57.99  4966.8   59.18  4980.2   55.67  4988.4   54.68  4988.9   53.42
  5005.6   52.58  5009.7   53.45  5011.5    55.4  5026.9   59.91  5044.8      63
  5054.8    64.1    5217   65.12    5287   64.51  6181.6   65.63  6691.4   66.89
#Mann= 5 , 1 , 0
  2334.9      .2       0    2966      .1       0  4944.8    .035       0
  5044.8     .08       0  6181.6      .2       0
Bank Sta=4944.8,5044.8
XS Rating Curve= 0 ,0
Exp/Cntr=0.5,0.3

Type RM Length L Ch R = 1 ,109361.1,48,48.03,47.98
BEGIN DESCRIPTION:
Upstream Section of Bridge/Culvert/Weir
END DESCRIPTION:
XS GIS Cut Line= 6
      3078825.99     13794014.21      3079726.67     13793163.55
      3079849.25     13791790.87      3079881.33     13790802.66
      3079700.66     13790332.92      3079358.91      13789967.6
#Sta/Elev= 30
  2241.7   68.62  2251.7   69.22  2296.7   65.52  2426.7   66.62  2471.7   65.42
  2536.7   66.52  2666.7   64.82  2711.7   65.82    2945   65.81  3231.7   65.22
  3311.7   66.52  3834.5   64.32  4661.7   64.43  4948.5   64.06  4980.2   55.43
  4988.4   54.44  4988.9   53.18  5005.6   52.34  5009.7   53.21  5011.5   55.16
  5040.7   64.43  5099.1   62.93  5215.9   63.81  5276.8   62.61  5636.4   64.42
  6082.2   63.91  6147.8   63.89  6408.3   66.42  6618.3   65.32    6851   67.32
#Mann= 7 , 1 , 0
  2241.7      .2       0    2945      .1       0  4661.7     .07       0
  4948.5    .035       0  5040.7      .1       0  6082.2     .08       0
  6147.8      .2       0
#XS Ineff= 2 , 0
       0    4940   64.31    5051       0   64.32
Permanent Ineff=
       F       F
Bank Sta=4948.5,5040.7
XS Rating Curve= 0 ,0
Exp/Cntr=0.5,0.3

Type RM Length L Ch R = 3 ,109337.1,,,
BEGIN DESCRIPTION:
ZAVALLA ROAD
Structure ID: C00-51
END DESCRIPTION:
Bridge Culvert--1,0,-1,-1, 0
Deck Dist Width WeirC Skew NumUp NumDn MinLoCord MaxHiCord MaxSubmerge Is_Ogee
10,28,2.6,0, 60, 60, , , 0.95, 0, 1,1,,
  2241.7  2251.7  2266.7  2276.7  2296.7  2336.7  2361.7  2381.7  2426.7  2471.7
  2536.7  2591.7  2666.7  2691.7  2711.7  2731.7  2751.7  2796.7  2841.7  3231.7
  3311.7  3834.5  3909.5  3924.5  3954.5  4029.5    4501    4526    4546  4664.1
  4733.2  4797.8  4859.1  4913.3  4948.5  4953.6  5036.6  5040.7  5099.1  5215.9
  5276.8  5364.7  5636.4  5866.8  6001.8  6091.8  6101.8  6286.8  6306.8  6361.8
  6386.8  6408.3  6468.3  6483.3  6523.3  6618.3  6638.3  6738.3  6758.3    6851
    68.6    69.2    68.2      67    65.5    66.5    66.4    65.8    66.6    65.4
    66.5    66.2    64.8    65.7    65.8    65.2    65.8    65.3      66    65.2
    66.5    64.3    64.6    64.2    64.8    64.2    64.4    63.8    64.3   64.41
   64.11   64.43   64.36   64.96   64.69   64.67   64.64   64.64   64.65   64.38
   64.17    63.7    64.4    64.5    63.8    63.9    63.5      65    65.6      66
    65.8    66.4    66.1    66.4    65.8    65.3    65.7    65.6    66.7    67.3
    68.6    69.2    68.2      67    65.5    66.5    66.4    65.8    66.6    65.4
    66.5    66.2    64.8    65.7    65.8    65.2    65.8    65.3      66    65.2
    66.5    64.3    64.6    64.2    64.8    64.2    64.4    63.8    64.3   64.41
   63.65   64.42   64.35   63.99   64.04   62.77   62.74   64.41   62.91   63.79
   62.59    63.7    64.4    64.5    63.8    63.9    63.5      65    65.6      66
    65.8    66.4    66.1    66.4    65.8    65.3    65.7    65.6    66.7    67.3
  2241.7  2251.7  2266.7  2276.7  2296.7  2336.7  2361.7  2381.7  2426.7  2471.7
  2536.7  2591.7  2666.7  2691.7  2711.7  2731.7  2751.7  2796.7  2841.7  3231.7
  3311.7  3834.5  3909.5  3924.5  3954.5  4029.5    4501    4526    4546  4664.1
  4733.2  4797.8  4859.1  4913.3  4948.5  4953.6  5036.6  5040.7  5099.1  5215.9
  5276.8  5364.7  5636.4  5866.8  6001.8  6091.8  6101.8  6286.8  6306.8  6361.8
  6386.8  6408.3  6468.3  6483.3  6523.3  6618.3  6638.3  6738.3  6758.3    6851
    68.6    69.2    68.2      67    65.5    66.5    66.4    65.8    66.6    65.4
    66.5    66.2    64.8    65.7    65.8    65.2    65.8    65.3      66    65.2
    66.5    64.3    64.6    64.2    64.8    64.2    64.4    63.8    64.3   64.41
   64.11   64.43   64.36   64.96   64.69   64.67   64.64   64.64   64.65   64.38
   64.17    63.7    64.4    64.5    63.8    63.9    63.5      65    65.6      66
    65.8    66.4    66.1    66.4    65.8    65.3    65.7    65.6    66.7    67.3
   68.43   69.03   68.03   66.83   65.33   66.33   66.23   65.63   66.43   65.23
   66.33   66.03   64.63   65.53   65.63   65.03   65.63   65.13   65.83   65.03
   66.33   64.13   64.43   64.03   64.63   64.03   64.23   63.63   64.13   64.24
   63.48   64.25   64.18   63.82   63.87    62.6   62.57   64.24   62.74   63.62
   62.42   63.53   64.23   64.33   63.63   63.73   63.33   64.83   65.43   65.83
   65.63   66.23   65.93   66.23   65.63   65.13   65.53   65.43   66.53   67.13
Pier Skew, UpSta & Num, DnSta & Num=  ,4980.2, 2 ,4980.2, 2 , 0 , 0 , 0 ,,
     1.4     1.4
   54.36   63.76
     1.4     1.4
   54.19   63.59
Pier Skew, UpSta & Num, DnSta & Num=  ,5010.9, 2 ,5010.9, 2 , 0 , 0 , 0 ,,
     1.4     1.4
   52.73   63.75
     1.4     1.4
   52.56   63.58
Abutment Skew #Up #Dn= , 2 , 2
  4949.5  4985.3
   63.69   55.05
  4949.5  4985.3
   63.52   54.88
Abutment Skew #Up #Dn= , 2 , 2
  5014.5 5040.69
   55.76   64.32
  5014.5 5040.69
   55.59   64.15
BR Coef= 1 , 1 , 0 ,1.25, 0 ,,,0.8,0,2,0,
WSPro=,,,, 1 ,,,, 0 ,,,, 0 ,,,,-1 ,-1 ,-1 , 0 , 0 , 0 , 0 , 0
BR U #Sta/Elev= 114
  2241.7    68.6  2251.7    69.2  2261.7    68.6  2266.7    68.2  2276.7      67
  2296.7    65.5  2336.7    66.5  2361.7    66.4  2381.7    65.8  2426.7    66.6
  2471.7    65.4  2536.7    66.5  2591.7    66.2  2666.7    64.8  2691.7    65.7
  2711.7    65.8  2731.7    65.2  2751.7    65.8  2796.7    65.3  2841.7      66
    2945   65.79  3231.7    65.2  3311.7    66.5  3519.5    65.7  3834.5    64.3
  3909.5    64.6  3924.5    64.2  3954.5    64.8  4029.5    64.2  4314.5    64.2
    4321    64.3    4501    64.4    4526    63.8    4546    64.3  4661.7   64.41
  4664.1   64.41  4732.1   63.66  4733.2   63.65    4793   64.36  4797.8   64.42
  4857.6   64.35  4859.1   64.35  4913.3   63.99  4917.5   63.96  4948.5   64.04
  4949.5   63.75 4949.61   63.72  4949.7   63.69 4949.89   63.64    4950   63.61
 4950.11   63.58  4953.6   62.57  4966.8   58.92  4980.2   55.41  4985.2   55.06
  4985.3   55.05  4988.4   54.42  4988.9   53.16  5005.6   52.32  5009.7   53.19
  5011.5   55.14  5014.4   55.73  5014.5   55.76  5026.9   59.65  5036.6   62.57
 5040.09   64.14  5040.2   64.19 5040.31   64.23 5040.49   64.32  5040.6   64.37
  5040.7   64.41  5098.4   62.93  5099.1   62.91  5156.7   63.37  5157.4   63.37
  5215.9   63.79  5219.2   63.72  5276.8   62.59  5278.5   62.61  5347.9   63.39
  5361.7   63.64  5364.7    63.7  5636.4    64.4  5651.4    64.2  5866.8    64.5
  5906.8    64.4  6001.8    63.8  6082.2   63.89  6091.8    63.9  6101.8    63.5
  6147.8   63.87  6286.8      65  6306.8    65.6  6361.8      66  6386.8    65.8
  6398.3      66  6408.3    66.4  6428.3    66.2  6443.3    66.4  6468.3    66.1
  6483.3    66.4  6523.3    65.8  6548.3    65.9  6573.3    65.4  6618.3    65.3
  6638.3    65.7  6673.3    65.5  6708.3    65.5  6738.3    65.6  6748.3      66
  6758.3    66.7  6778.3    66.9  6823.3      67    6851    67.3
BR U #Mann= 7
  2241.7      .2    2945      .1  4661.7     .07  4948.5    .035  5040.7      .1
  6082.2     .08  6147.8      .2
BR U Banks=4948.5,5040.7
BR D #Sta/Elev= 114
  2241.7   68.43  2251.7   69.03  2261.7   68.43  2266.7   68.03  2276.7   66.83
  2296.7   65.33  2336.7   66.33  2361.7   66.23  2381.7   65.63  2426.7   66.43
  2471.7   65.23  2536.7   66.33  2591.7   66.03  2666.7   64.63  2691.7   65.53
  2711.7   65.63  2731.7   65.03  2751.7   65.63  2796.7   65.13  2841.7   65.83
    2945   65.62  3231.7   65.03  3311.7   66.33  3519.5   65.53  3834.5   64.13
  3909.5   64.43  3924.5   64.03  3954.5   64.63  4029.5   64.03  4314.5   64.03
    4321   64.13    4501   64.23    4526   63.63    4546   64.13  4661.7   64.24
  4664.1   64.24  4732.1   63.49  4733.2   63.48    4793   64.19  4797.8   64.25
  4857.6   64.18  4859.1   64.18  4913.3   63.82  4917.5   63.79  4948.5   63.87
  4949.5   63.58 4949.61   63.55  4949.7   63.52 4949.89   63.47    4950   63.44
 4950.11   63.41  4953.6    62.4  4966.8   58.75  4980.2   55.24  4985.2   54.89
  4985.3   54.88  4988.4   54.25  4988.9   52.99  5005.6   52.15  5009.7   53.02
  5011.5   54.97  5014.4   55.56  5014.5   55.59  5026.9   59.48  5036.6    62.4
 5040.09   63.97  5040.2   64.02 5040.31   64.06 5040.49   64.15  5040.6    64.2
  5040.7   64.24  5098.4   62.76  5099.1   62.74  5156.7    63.2  5157.4    63.2
  5215.9   63.62  5219.2   63.55  5276.8   62.42  5278.5   62.44  5347.9   63.22
  5361.7   63.47  5364.7   63.53  5636.4   64.23  5651.4   64.03  5866.8   64.33
  5906.8   64.23  6001.8   63.63  6082.2   63.72  6091.8   63.73  6101.8   63.33
  6147.8    63.7  6286.8   64.83  6306.8   65.43  6361.8   65.83  6386.8   65.63
  6398.3   65.83  6408.3   66.23  6428.3   66.03  6443.3   66.23  6468.3   65.93
  6483.3   66.23  6523.3   65.63  6548.3   65.73  6573.3   65.23  6618.3   65.13
  6638.3   65.53  6673.3   65.33  6708.3   65.33  6738.3   65.43  6748.3   65.83
  6758.3   66.53  6778.3   66.73  6823.3   66.83    6851   67.13
BR D #Mann= 7
  2241.7      .2    2945      .1  4661.7     .07  4948.5    .035  5040.7      .1
  6082.2     .08  6147.8      .2
BR D Banks=4948.5,5040.7
BC Design=,, 0 ,, 0 ,,,,,,
BC HTab HWMax=69.22
BC Use User HTab Curves=0
BC User HTab FreeFlow(D)= 0

Type RM Length L Ch R = 1 ,109313.1,435.36,436.75,436.92
BEGIN DESCRIPTION:
Downstream Section of Bridge/Culvert/Weir
END DESCRIPTION:
XS GIS Cut Line= 6
      3078873.88     13794017.41      3079774.57     13793166.75
      3079897.15     13791794.07      3079929.23     13790805.86
      3079748.56     13790336.12      3079406.81      13789970.8
#Sta/Elev= 30
  2241.7   68.43  2251.7   69.03  2296.7   65.33  2426.7   66.43  2471.7   65.23
  2536.7   66.33  2666.7   64.63  2711.7   65.63    2945   65.62  3231.7   65.03
  3311.7   66.33  3834.5   64.13  4661.7   64.24  4948.5   63.87  4980.2   55.24
  4988.4   54.25  4988.9   52.99  5005.6   52.15  5009.7   53.02  5011.5   54.97
  5040.7   64.24  5099.1   62.74  5215.9   63.62  5276.8   62.42  5636.4   64.23
  6082.2   63.72  6147.8    63.7  6408.3   66.23  6618.3   65.13    6851   67.13
#Mann= 7 , 1 , 0
  2241.7      .2       0    2945      .1       0  4661.7     .07       0
  4948.5    .035       0  5040.7      .1       0  6082.2     .08       0
  6147.8      .2       0
#XS Ineff= 2 , 0
       0    4940   64.31    5051       0   64.32
Permanent Ineff=
       F       F
Bank Sta=4948.5,5040.7
XS Rating Curve= 0 ,0
Exp/Cntr=0.5,0.3

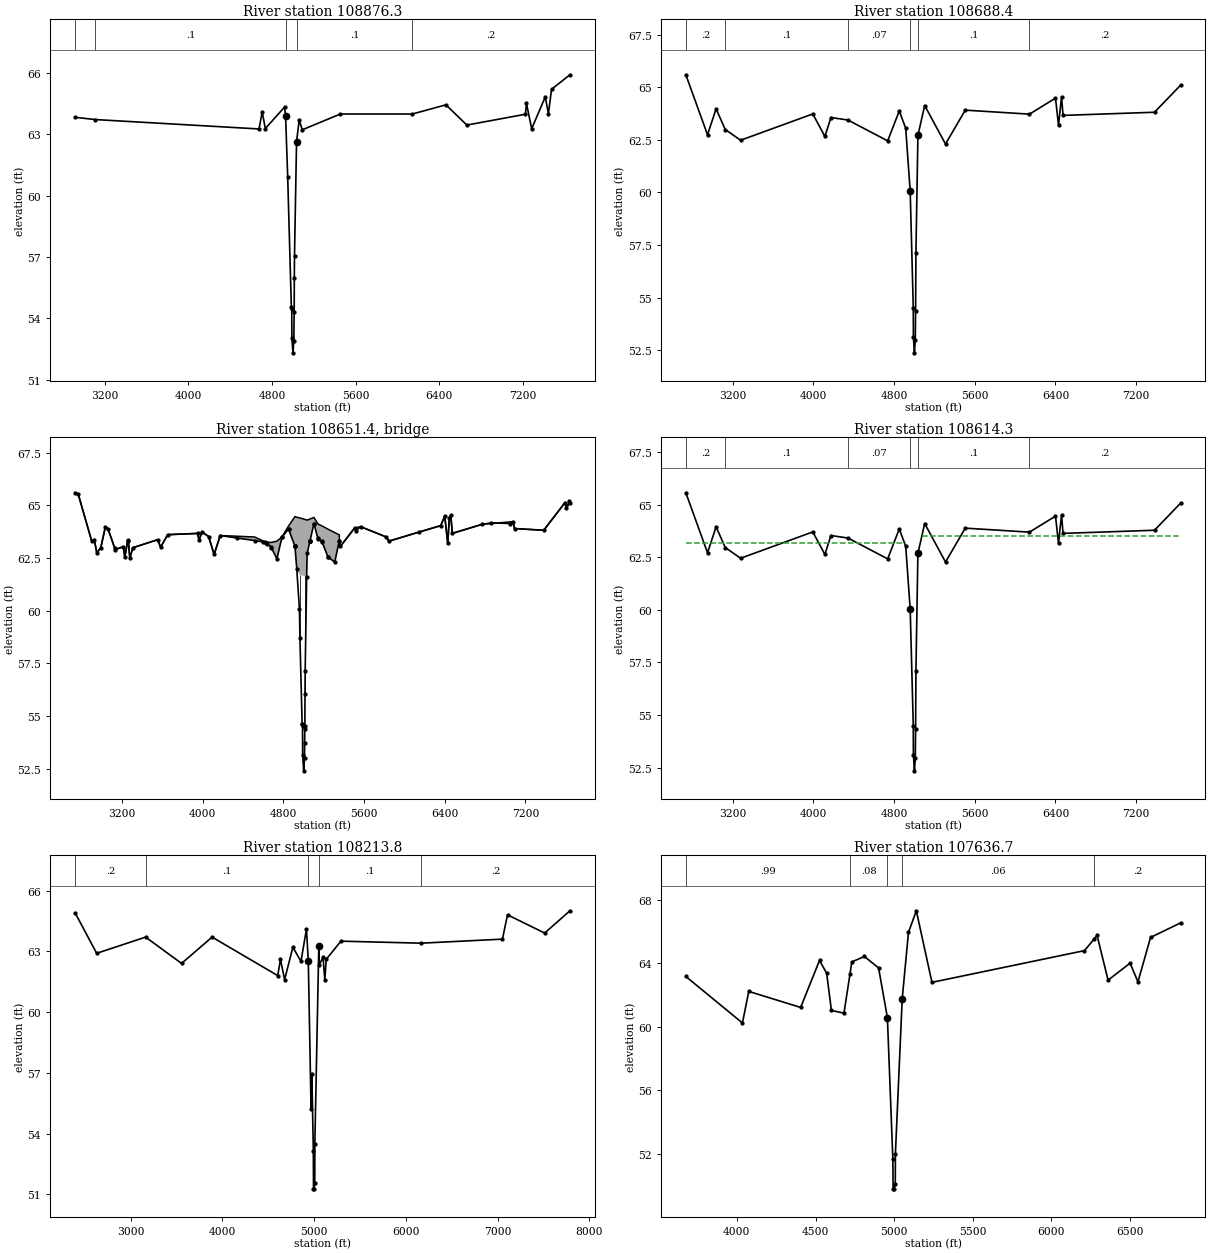
Type RM Length L Ch R = 1 ,108876.3,188.87,187.95,187.18
BEGIN DESCRIPTION:
Cross Section 110969.0 - Interpolated
END DESCRIPTION:
XS GIS Cut Line= 5
      3079962.18     13793693.55      3080244.46     13793075.73
      3080329.68     13791834.76      3080361.63     13791222.27
      3080281.74     13789027.94
#Sta/Elev= 30
  2917.6   63.84  3110.2   63.73  4676.9   63.27  4706.9   64.11  4736.9   63.29
  4920.7   64.34  4930.7   63.88  4950.7   60.94  4985.7   54.55  4989.6   54.46
  4990.7   53.07  5001.1   52.32  5009.5   52.91  5012.8   54.33  5014.1   55.99
  5015.9   57.07  5035.5   62.65  5060.7    63.7  5090.7   63.23  5454.1      64
  6141.5      64  6464.1   64.45  6664.1   63.46  7224.1   63.99  7234.1   64.52
  7284.1   63.28  7414.1   64.84  7444.1   64.01  7474.1   65.21  7649.9   65.92
#Mann= 5 , 1 , 0
  2917.6      .2       0  3110.2      .1       0  4930.7    .035       0
  5035.5      .1       0  6141.5      .2       0
Bank Sta=4930.7,5035.5
XS Rating Curve= 0 ,0
Exp/Cntr=0.5,0.3

Type RM Length L Ch R = 1 ,108688.4,73.99,74.04,74
BEGIN DESCRIPTION:
Upstream Section of Bridge/Culvert/Weir
END DESCRIPTION:
XS GIS Cut Line= 6
      3080038.18     13793801.72      3080313.98     13793560.39
      3080470.56     13792861.81      3080514.03     13792018.95
      3080591.01     13790175.89      3080480.35     13789044.84
#Sta/Elev= 30
    2734   65.59    2949   62.74    3034   63.97  3124.9   62.99    3277   62.48
  3993.1   63.73  4113.1   62.66  4173.1   63.56  4341.9   63.44  4735.4   62.45
  4850.8   63.87  4914.6   63.05  4959.1   60.06  4989.6   54.52  4990.7   53.13
  5001.1   52.38  5009.5   52.97  5012.7   54.39  5015.9   57.13  5035.5   62.71
  5102.7   64.13  5309.2    62.3    5505   63.91  6141.9   63.72    6400   64.48
    6430   63.19    6460   64.54    6475   63.66    7382   63.81  7641.5    65.1
#Mann= 6 , 1 , 0
    2734      .2       0  3124.9      .1       0  4341.9     .07       0
  4959.1    .035       0  5035.5      .1       0  6141.9      .2       0
#XS Ineff= 2 , 0
       0    4904   63.17    5074       0   63.51
Permanent Ineff=
       F       F
Bank Sta=4959.1,5035.5
XS Rating Curve= 0 ,0
Exp/Cntr=0.5,0.3

Type RM Length L Ch R = 3 ,108651.4,,,
BEGIN DESCRIPTION:
CARLSBAD ROAD
Structure ID: C00-50
END DESCRIPTION:
Bridge Culvert--1,0,-1,-1, 0
Deck Dist Width WeirC Skew NumUp NumDn MinLoCord MaxHiCord MaxSubmerge Is_Ogee
10,54,2.6,0, 60, 60, , , 0.95, 0, 1,1,,
    2734    2764    2899    2924    2949    2989    3034    3062    3132    3212
    3227    3257    3262    3277    3307    3552    3582  3653.1  3948.1  3963.1
  3993.1  4058.1  4113.1  4173.1  4515.3  4615.5    4676  4735.4  4785.5  4850.8
  4914.6  4932.3  4959.1  5030.3  5035.5  5102.7  5142.5  5180.7  5242.5  5309.2
  5354.3  5354.4  5364.4    5505    5565    5820    5845    6360    6400    6430
    6445    6460    6475    6770    7077    7092    7382    7592    7607  7641.5
    65.6   65.55    63.3   63.38   62.75   62.99   63.98   63.86    62.9   63.04
   62.54   63.36   63.31   62.49   62.99   63.37   63.02   63.61   63.67   63.36
   63.74   63.52   62.67   63.57    63.5   63.27   63.24    63.3    63.5   64.02
   64.47   64.44   64.41   64.31    64.3   64.43   64.12   64.03   63.87   63.71
    63.6   63.32   63.05   63.92   63.99    63.5    63.3   64.04   64.49    63.2
   64.38   64.55   63.67    64.1   64.23    63.9   63.82   65.13   64.88   65.11
    65.6   65.55    63.3   63.38   62.75   62.99   63.98   63.86    62.9   63.04
   62.54   63.36   63.31   62.49   62.99   63.37   63.02   63.61   63.67   63.36
   63.74   63.52   62.67   63.57   63.33   63.26   63.04   62.46   63.49   63.88
   63.06   61.99   61.71   61.61   62.72   64.14   63.42    63.3   62.54   62.31
   63.32   63.32   63.05   63.92   63.99    63.5    63.3   64.04   64.49    63.2
   64.38   64.55   63.67    64.1   64.23    63.9   63.82   65.13   64.88   65.11
    2734    2764    2899    2924    2949    2989    3034    3062    3132    3212
    3227    3257    3262    3277    3307    3552    3582  3653.1  3948.1  3963.1
  3993.1  4058.1  4113.1  4173.1  4515.3  4615.5    4676  4735.4  4785.5  4850.8
  4914.6  4932.3  4959.1  5030.3  5035.5  5102.7  5142.5  5180.7  5242.5  5309.2
  5354.3  5354.4  5364.4    5505    5565    5820    5845    6360    6400    6430
    6445    6460    6475    6770    7077    7092    7382    7592    7607  7641.5
    65.6   65.55    63.3   63.38   62.75   62.99   63.98   63.86    62.9   63.04
   62.54   63.36   63.31   62.49   62.99   63.37   63.02   63.61   63.67   63.36
   63.74   63.52   62.67   63.57    63.5   63.27   63.24    63.3    63.5   64.02
   64.47   64.44   64.41   64.31    64.3   64.43   64.12   64.03   63.87   63.71
    63.6   63.32   63.05   63.92   63.99    63.5    63.3   64.04   64.49    63.2
   64.38   64.55   63.67    64.1   64.23    63.9   63.82   65.13   64.88   65.11
   65.59   65.54   63.29   63.37   62.74   62.98   63.97   63.85   62.89   63.03
   62.53   63.35    63.3   62.48   62.98   63.36   63.01    63.6   63.66   63.35
   63.73   63.51   62.66   63.56   63.32   63.25   63.03   62.45   63.48   63.87
   63.05   61.98    61.7    61.6   62.71   64.13   63.41   63.29   62.53    62.3
   63.31   63.31   63.04   63.91   63.98   63.49   63.29   64.03   64.48   63.19
   64.37   64.54   63.66   64.09   64.22   63.89   63.81   65.12   64.87    65.1
Pier Skew, UpSta & Num, DnSta & Num=  ,4963.9, 2 ,4963.9, 2 , 0 , 0 , 0 ,,
     1.4     1.4
   57.58    62.7
     1.4     1.4
   57.57   62.69
Pier Skew, UpSta & Num, DnSta & Num=  ,5014.1, 2 ,5014.1, 2 , 0 , 0 , 0 ,,
     1.4     1.4
   54.23   62.63
     1.4     1.4
   54.22   62.62
Abutment Skew #Up #Dn= , 2 , 2
  4913.7  4985.7
   63.07   54.62
  4913.7  4985.7
   63.06   54.61
Abutment Skew #Up #Dn= , 2 , 2
  5012.8 5063.99
   54.52   63.32
  5012.8 5063.99
   54.51   63.31
BR Coef= 1 , 1 , 0 ,1.25, 0 ,,,0.8,0,2,0,
WSPro=,,,, 1 ,,,, 0 ,,,, 0 ,,,,-1 ,-1 ,-1 , 0 , 0 , 0 , 0 , 0
BR U #Sta/Elev= 99
    2734    65.6    2764   65.55    2899    63.3    2924   63.38    2949   62.75
    2989   62.99    3034   63.98    3062   63.86  3124.9      63    3132    62.9
    3212   63.04    3227   62.54    3257   63.36    3262   63.31    3277   62.49
    3307   62.99    3552   63.37    3582   63.02  3653.1   63.61  3948.1   63.67
  3963.1   63.36  3993.1   63.74  4058.1   63.52  4113.1   62.67  4173.1   63.57
  4341.9   63.45  4515.3   63.33  4593.1   63.27  4615.5   63.26  4630.3   63.21
  4640.3   63.17    4676   63.04  4681.2   62.99  4735.4   62.46  4785.5   63.49
    4786   63.49  4850.8   63.88  4852.2   63.86 4913.47   63.07 4913.58   63.07
 4913.69   63.07 4913.81   63.07  4913.9   63.07  4914.6   63.06  4932.3   61.99
  4959.1   60.07  4963.9   58.71  4985.6   54.62  4985.7   54.62  4989.6   54.53
  4990.7   53.14  5001.1   52.39  5009.5   52.98  5010.4   53.72  5012.7    54.4
  5012.8   54.52  5014.1   56.06  5015.9   57.14  5030.3    61.6  5035.5   62.72
 5063.46   63.31 5063.57   63.31 5063.68   63.32 5063.79   63.32  5063.9   63.32
  5102.7   64.14  5102.9   64.14  5141.3   63.44  5142.5   63.42  5180.7    63.3
    5184   63.26  5242.5   62.54  5243.3   62.54  5309.2   62.31  5354.3   63.32
  5354.4   63.32  5364.4   63.05    5505   63.92    5520    63.8    5565   63.99
    5820    63.5    5845    63.3  6141.9   63.73    6360   64.04    6400   64.49
    6430    63.2    6445   64.38    6460   64.55    6475   63.67    6770    64.1
    6862   64.17    7052   64.14    7077   64.23    7092    63.9    7382   63.82
    7592   65.13    7607   64.88    7637   65.19  7641.5   65.11
BR U #Mann= 6
    2734      .2  3124.9      .1  4341.9     .07  4959.1    .035  5035.5      .1
  6141.9      .2
BR U Banks=4959.1,5035.5
BR D #Sta/Elev= 99
    2734   65.59    2764   65.54    2899   63.29    2924   63.37    2949   62.74
    2989   62.98    3034   63.97    3062   63.85  3124.9   62.99    3132   62.89
    3212   63.03    3227   62.53    3257   63.35    3262    63.3    3277   62.48
    3307   62.98    3552   63.36    3582   63.01  3653.1    63.6  3948.1   63.66
  3963.1   63.35  3993.1   63.73  4058.1   63.51  4113.1   62.66  4173.1   63.56
  4341.9   63.44  4515.3   63.32  4593.1   63.26  4615.5   63.25  4630.3    63.2
  4640.3   63.16    4676   63.03  4681.2   62.98  4735.4   62.45  4785.5   63.48
    4786   63.48  4850.8   63.87  4852.2   63.85 4913.47   63.06 4913.58   63.06
 4913.69   63.06 4913.81   63.06  4913.9   63.06  4914.6   63.05  4932.3   61.98
  4959.1   60.06  4963.9    58.7  4985.6   54.61  4985.7   54.61  4989.6   54.52
  4990.7   53.13  5001.1   52.38  5009.5   52.97  5010.4   53.71  5012.7   54.39
  5012.8   54.51  5014.1   56.05  5015.9   57.13  5030.3   61.59  5035.5   62.71
 5063.46    63.3 5063.57    63.3 5063.68   63.31 5063.79   63.31  5063.9   63.31
  5102.7   64.13  5102.9   64.13  5141.3   63.43  5142.5   63.41  5180.7   63.29
    5184   63.25  5242.5   62.53  5243.3   62.53  5309.2    62.3  5354.3   63.31
  5354.4   63.31  5364.4   63.04    5505   63.91    5520   63.79    5565   63.98
    5820   63.49    5845   63.29  6141.9   63.72    6360   64.03    6400   64.48
    6430   63.19    6445   64.37    6460   64.54    6475   63.66    6770   64.09
    6862   64.16    7052   64.13    7077   64.22    7092   63.89    7382   63.81
    7592   65.12    7607   64.87    7637   65.18  7641.5    65.1
BR D #Mann= 6
    2734      .2  3124.9      .1  4341.9     .07  4959.1    .035  5035.5      .1
  6141.9      .2
BR D Banks=4959.1,5035.5
BC Design=,, 0 ,, 0 ,,,,,,
BC HTab HWMax=65.59
BC Use User HTab Curves=0
BC User HTab FreeFlow(D)= 0

Type RM Length L Ch R = 1 ,108614.3,400.61,400.54,395.72
BEGIN DESCRIPTION:
Downstream Section of Bridge/Culvert/Weir
END DESCRIPTION:
XS GIS Cut Line= 6
      3080112.07     13793805.81      3080387.86     13793564.49
      3080544.44     13792865.91      3080587.91     13792023.05
      3080664.89     13790179.99      3080554.24     13789048.94
#Sta/Elev= 30
    2734   65.56    2949   62.71    3034   63.94  3124.9   62.96    3277   62.45
  3993.1    63.7  4113.1   62.63  4173.1   63.53  4341.9   63.41  4735.4   62.42
  4850.8   63.84  4914.6   63.02  4959.1   60.03  4989.6   54.49  4990.7    53.1
  5001.1   52.35  5009.5   52.94  5012.7   54.36  5015.9    57.1  5035.5   62.68
  5102.7    64.1  5309.2   62.27    5505   63.88  6141.9   63.69    6400   64.45
    6430   63.16    6460   64.51    6475   63.63    7382   63.78  7641.5   65.07
#Mann= 6 , 1 , 0
    2734      .2       0  3124.9      .1       0  4341.9     .07       0
  4959.1    .035       0  5035.5      .1       0  6141.9      .2       0
#XS Ineff= 2 , 0
       0    4904   63.17    5074       0   63.51
Permanent Ineff=
       F       F
Bank Sta=4959.1,5035.5
XS Rating Curve= 0 ,0
Exp/Cntr=0.5,0.3

Type RM Length L Ch R = 1 ,108213.8,569.28,577.05,576.27
BEGIN DESCRIPTION:
Cross Section 110309.5-Interpolated
END DESCRIPTION:
XS GIS Cut Line= 6
      3080538.31     13794266.23      3080794.78     13793132.37
      3080997.26     13791850.02      3080997.26     13791715.04
      3080970.26     13791080.62      3080929.77     13788920.88
#Sta/Elev= 30
  2396.3    64.9  2631.3    62.9  3164.6    63.7  3556.3    62.4  3888.8    63.7
  4603.8    61.8  4633.8    62.6  4678.8    61.6  4768.8    63.2    4857    62.5
    4917    64.1    4937    62.5    4967    55.2  4975.4   56.96  4991.9   53.12
  4993.5   51.28  5000.4   51.27  5007.3   51.57  5008.1   53.49  5051.3   63.24
    5052    62.3    5097    62.7    5117    61.6    5132    62.6    5292    63.5
  6166.3    63.4    7052    63.6    7107    64.8    7512    63.9  7787.1      65
#Mann= 5 , 1 , 0
  2396.3      .2       0  3164.6      .1       0    4937    .035       0
  5051.3      .1       0  6166.3      .2       0
Bank Sta=4937,5051.3
XS Rating Curve= 0 ,0
Exp/Cntr=0.3,0.1

Type RM Length L Ch R = 1 ,107636.7,185.92,189.23,189.89
BEGIN DESCRIPTION:
Cross Section 109732.0 - Interpolated
END DESCRIPTION:
XS GIS Cut Line= 4
      3081719.77     13793128.99      3081538.69      13792292.8
      3081554.67     13791653.68      3081512.06     13790002.61
#Sta/Elev= 30
  3675.5   63.16  4035.5   60.23  4075.5   62.22  4405.5   61.21  4525.5   64.17
  4571.1   63.36  4601.1   61.02  4681.1   60.85  4719.3   63.32  4731.1   64.08
  4811.1   64.42  4901.1    63.7  4957.1   60.57  4991.9   51.63  4993.5   49.79
  5000.4   49.78  5007.3   50.08  5008.1      52  5051.3   61.75  5091.1   65.94
  5141.1    67.3  5240.4   62.79  6210.4   64.79    6274   65.55  6290.4   65.75
  6360.4   62.93  6500.4      64  6550.4   62.82  6630.4   65.62    6822   66.54
#Mann= 5 ,-1 , 0
  3675.5     .99       0  4719.3     .08       0  4957.1    .035       0
  5051.3     .06       0    6274      .2       0
Bank Sta=4957.1,5051.3
XS Rating Curve= 0 ,0
Exp/Cntr=0.5,0.3