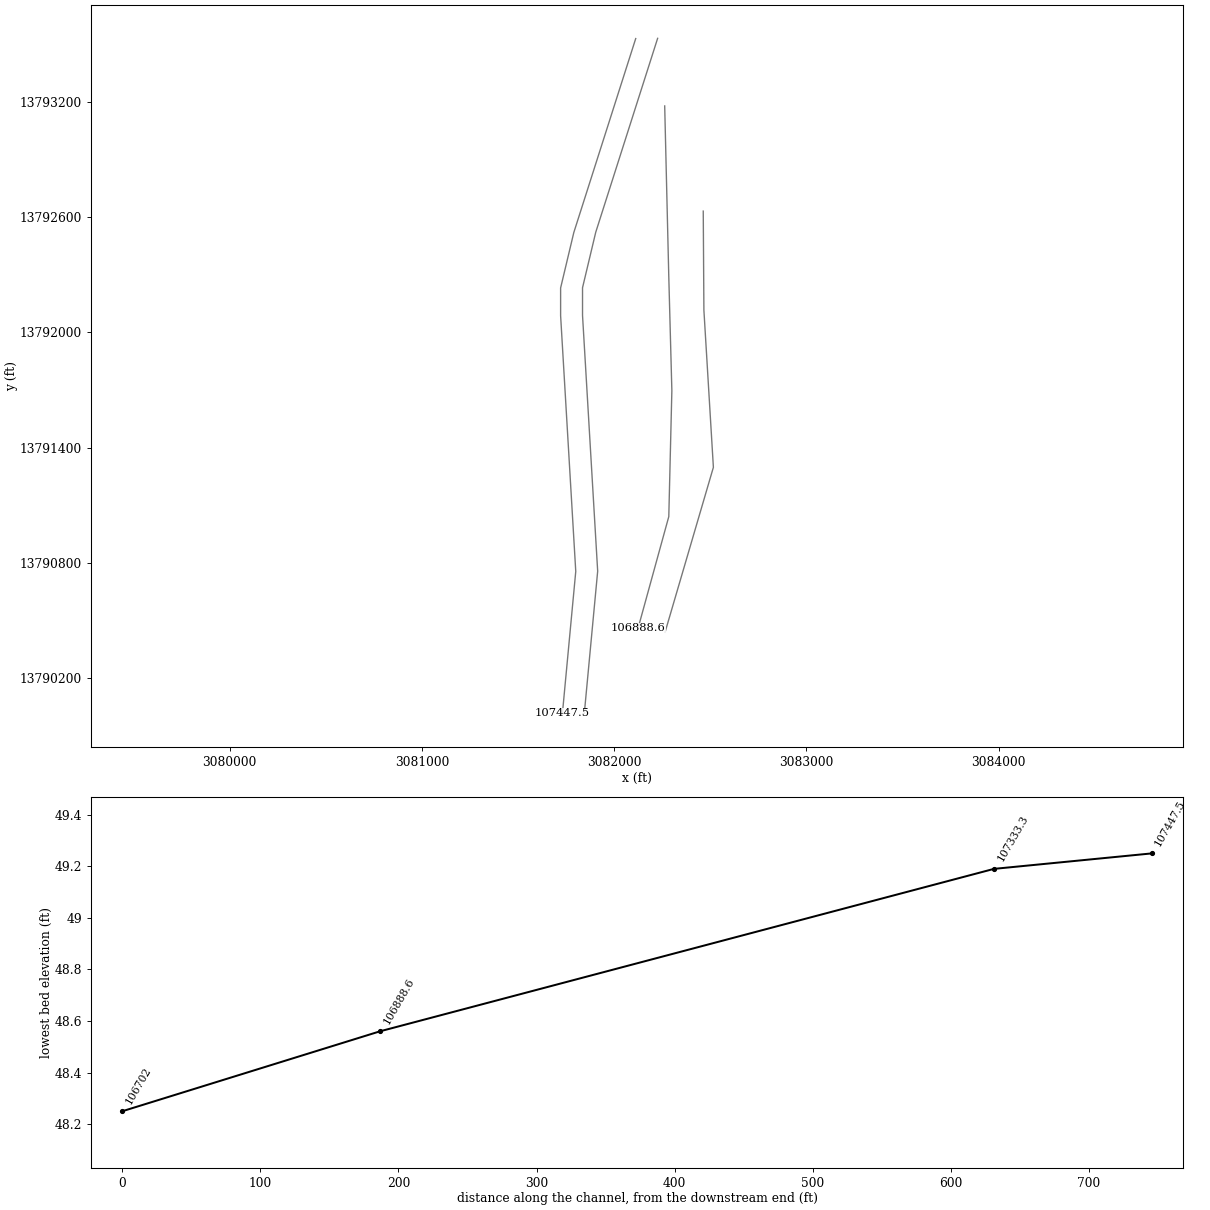
HEC-RAS study C100-00-00.prj: C100-00-00

--- C100-00-00.g01 (geometry) --- (continued)

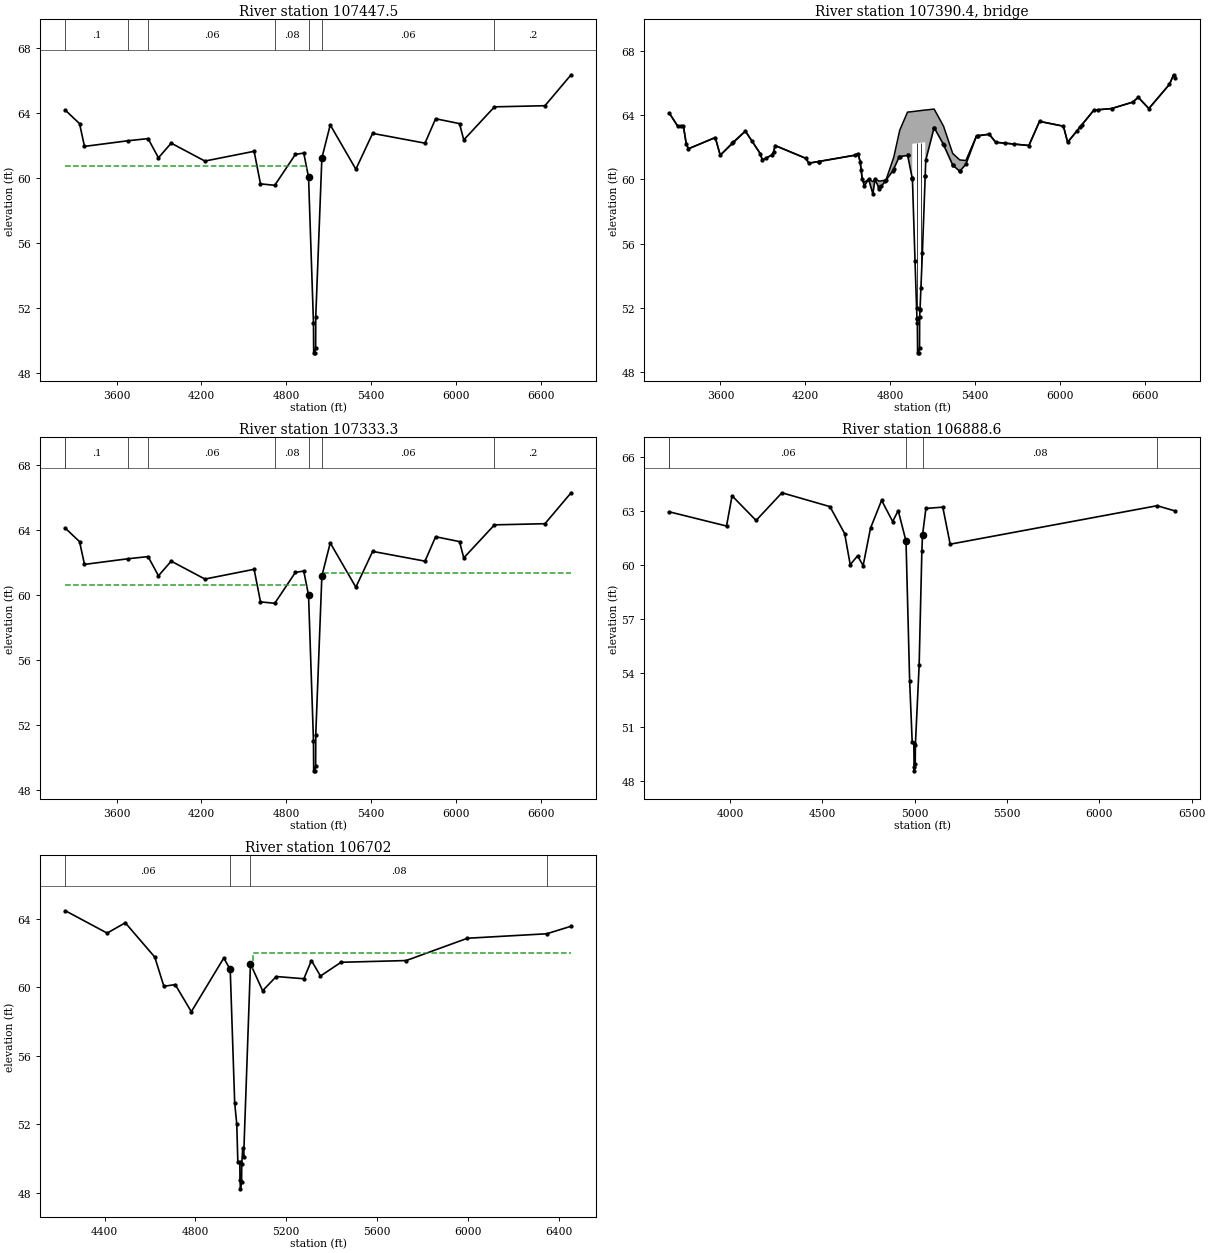
Type RM Length L Ch R = 1 ,107447.5,113.86,114.25,113.91
BEGIN DESCRIPTION:
Upstream Section of Bridge/Culvert/Weir
END DESCRIPTION:
XS GIS Cut Line= 6
       3082112.3     13793527.38      3081790.35     13792518.76
      3081721.67     13792230.32      3081721.67     13792086.11
      3081800.46     13790756.01      3081731.05     13790017.66
#Sta/Elev= 30
  3238.8   64.15  3338.8   63.33  3373.8   61.93  3683.3   62.28  3823.2   62.41
  3896.5   61.23  3986.5   62.13  4224.7   61.03  4572.5   61.63  4617.5   59.63
  4718.3   59.54  4864.2   61.44  4923.3   61.52  4957.1   60.04  4991.9    51.1
  4993.4   49.26  5000.4   49.25  5007.3   49.55  5008.1   51.47  5051.3   61.22
  5110.4   63.25  5291.5   60.53  5410.1   62.73  5780.1   62.13  5855.1   63.63
    6024   63.33    6054   62.33  6271.1   64.36  6627.8   64.43  6812.5   66.33
#Mann= 7 ,-1 , 0
  3238.8      .1       0  3683.3     .12       0  3823.2     .06       0
  4718.3     .08       0  4957.1    .035       0  5051.3     .06       0
  6271.1      .2       0
#XS Ineff= 2 , 0
       0    4945   60.75    5057       0   61.37
Permanent Ineff=
       F       F
Bank Sta=4957.1,5051.3
XS Rating Curve= 0 ,0
Exp/Cntr=0.5,0.3

Type RM Length L Ch R = 3 ,107390.4,,,
BEGIN DESCRIPTION:
HILLCROFT AVENUE
Structure ID: C00-49
END DESCRIPTION:
Bridge Culvert--1,0,-1,-1, 0
Deck Dist Width WeirC Skew NumUp NumDn MinLoCord MaxHiCord MaxSubmerge Is_Ogee
10,94,2.65,0, 54, 54, , , 0.95, 0, 1,1,,
  3238.8  3298.8  3338.8  3358.8  3373.8  3563.8  3598.8  3776.5  3881.5  3896.5
  3961.5  3976.5  3986.5  4204.7  4224.7  4552.5  4572.5  4587.5  4602.5  4617.5
  4647.5  4677.5  4692.5  4723.4  4769.9    4825  4864.2  4867.1  4922.3 4955.91
    4956 5047.19  5047.3  5051.3  5110.4  5177.1  5241.7  5291.5  5334.7  5410.1
  5500.1  5545.1  5780.1  5855.1    6024    6054    6239    6364    6514  6552.8
  6627.8  6772.8  6802.8  6812.5
   64.12    63.3    63.3    62.2    61.9    62.6    61.5      63    61.6    61.2
   61.51   61.71   62.11   61.31   61.01   61.51   61.61   61.11   60.01   59.82
   60.01   59.86   60.01   59.89   59.96   61.37   62.93   63.05   64.18   64.21
   64.21   64.31   64.31   64.31   64.37    63.3   61.61   61.21   61.17   62.71
   62.81   62.31   62.11   63.61   63.31   62.31    64.3    64.4    64.8    65.1
    64.4    65.9    66.5    66.3
   64.12    63.3    63.3    62.2    61.9    62.6    61.5      63    61.6    61.2
    61.5    61.7    62.1    61.3      61    61.5    61.6    61.1      60    59.6
      60    59.1      60   59.41   59.95   60.65   61.41   61.41   61.49   60.06
   62.21   62.31   60.23   61.19   63.22   62.15   60.89    60.5   60.94    62.7
    62.8    62.3    62.1    63.6    63.3    62.3    64.3    64.4    64.8    65.1
    64.4    65.9    66.5    66.3
  3238.8  3298.8  3338.8  3358.8  3373.8  3563.8  3598.8  3776.5  3881.5  3896.5
  3961.5  3976.5  3986.5  4204.7  4224.7  4552.5  4572.5  4587.5  4602.5  4617.5
  4647.5  4677.5  4692.5  4723.4  4769.9    4825  4864.2  4867.1  4922.3 4955.91
    4956 5047.19  5047.3  5051.3  5110.4  5177.1  5241.7  5291.5  5334.7  5410.1
  5500.1  5545.1  5780.1  5855.1    6024    6054    6239    6364    6514  6552.8
  6627.8  6772.8  6802.8  6812.5
   64.12    63.3    63.3    62.2    61.9    62.6    61.5      63    61.6    61.2
   61.51   61.71   62.11   61.31   61.01   61.51   61.61   61.11   60.01   59.82
   60.01   59.86   60.01   59.89   59.96   61.37   62.93   63.05   64.18   64.21
   64.21   64.31   64.31   64.31   64.37    63.3   61.61   61.21   61.17   62.71
   62.81   62.31   62.11   63.61   63.31   62.31    64.3    64.4    64.8    65.1
    64.4    65.9    66.5    66.3
    64.1   63.28   63.28   62.18   61.88   62.58   61.48   62.98   61.58   61.18
   61.48   61.68   62.08   61.28   60.98   61.48   61.58   61.08   59.98   59.58
   59.98   59.08   59.98   59.39   59.93   60.63   61.39   61.39   61.47   60.04
   62.19   62.29   60.21   61.17    63.2   62.13   60.87   60.48   60.92   62.68
   62.78   62.28   62.08   63.58   63.28   62.28   64.28   64.38   64.78   65.08
   64.38   65.88   66.48   66.28
Pier Skew, UpSta & Num, DnSta & Num=  ,4986.6, 2 ,4986.6, 2 , 0 , 0 , 0 ,,
     1.4     1.4
   50.81   63.24
     1.4     1.4
   50.79   63.22
Pier Skew, UpSta & Num, DnSta & Num=  ,5016.9, 2 ,5016.9, 2 , 0 , 0 , 0 ,,
     1.4     1.4
   52.08   63.28
     1.4     1.4
   52.06   63.26
Abutment Skew #Up #Dn= , 2 , 2
  4955.8  4989.1
   62.21   51.35
  4955.8  4989.1
   62.19   51.33
Abutment Skew #Up #Dn= , 2 , 2
  5010.7 5047.39
   51.93   62.31
  5010.7 5047.39
   51.91   62.29
BR Coef= 1 , 1 , 0 ,1.25, 0 ,,,0.8,0,2,0,
WSPro=,,,, 1 ,,,, 0 ,,,, 0 ,,,,-1 ,-1 ,-1 , 0 , 0 , 0 , 0 , 0
BR U #Sta/Elev= 92
  3238.8   64.12  3298.8    63.3  3318.8    63.3  3338.8    63.3  3358.8    62.2
  3373.8    61.9  3563.8    62.6  3598.8    61.5  3683.3   62.25  3688.8    62.3
  3776.5      63  3823.2   62.38  3881.5    61.6  3896.5    61.2  3919.8   61.31
  3961.5    61.5  3976.5    61.7  3986.5    62.1  4204.7    61.3  4224.7      61
  4294.8   61.11  4297.7   61.11  4552.5    61.5  4572.5    61.6  4587.5    61.1
  4594.2   60.61  4602.5      60  4617.5    59.6  4647.5      60  4677.5    59.1
  4692.5      60  4718.3   59.51  4723.4   59.41  4738.4   59.58  4766.4   59.91
  4769.9   59.95  4819.6   60.54    4825   60.65  4864.2   61.41  4867.1   61.41
  4922.3   61.49  4923.3   61.49 4955.91   60.06    4956   60.06  4957.1   60.01
  4975.4   54.91  4986.6   51.99    4989   51.36  4989.1   51.35  4991.9   51.07
  4993.4   49.23  5000.4   49.22  5007.3   49.52  5008.1   51.44  5010.6   51.91
  5010.7   51.93  5016.9   53.23  5027.5   55.45 5047.19    60.2  5047.3   60.23
  5051.3   61.19  5110.4   63.22  5111.5    63.2    5174   62.21  5177.1   62.15
  5241.7   60.89  5242.7   60.88  5291.5    60.5  5292.9   60.51  5334.7   60.94
  5410.1    62.7  5423.4   62.71  5500.1    62.8  5545.1    62.3  5608.4   62.25
  5674.4   62.19  5780.1    62.1  5855.1    63.6    6024    63.3    6054    62.3
  6119.4   63.01  6144.4   63.28  6155.6    63.4    6239    64.3  6271.1   64.33
    6364    64.4    6514    64.8  6552.8    65.1  6627.8    64.4  6772.8    65.9
  6802.8    66.5  6812.5    66.3
BR U #Mann= 8
  3238.8      .2  3238.8      .1  3683.3     .12  3823.2     .06  4718.3     .08
  4957.1    .035  5051.3     .06  6271.1      .2
BR U Banks=4957.1,5051.3
BR D #Sta/Elev= 92
  3238.8    64.1  3298.8   63.28  3318.8   63.28  3338.8   63.28  3358.8   62.18
  3373.8   61.88  3563.8   62.58  3598.8   61.48  3683.3   62.23  3688.8   62.28
  3776.5   62.98  3823.2   62.36  3881.5   61.58  3896.5   61.18  3919.8   61.29
  3961.5   61.48  3976.5   61.68  3986.5   62.08  4204.7   61.28  4224.7   60.98
  4294.8   61.09  4297.7   61.09  4552.5   61.48  4572.5   61.58  4587.5   61.08
  4594.2   60.59  4602.5   59.98  4617.5   59.58  4647.5   59.98  4677.5   59.08
  4692.5   59.98  4718.3   59.49  4723.4   59.39  4738.4   59.56  4766.4   59.89
  4769.9   59.93  4819.6   60.52    4825   60.63  4864.2   61.39  4867.1   61.39
  4922.3   61.47  4923.3   61.47 4955.91   60.04    4956   60.04  4957.1   59.99
  4975.4   54.89  4986.6   51.97    4989   51.34  4989.1   51.33  4991.9   51.05
  4993.4   49.21  5000.4    49.2  5007.3    49.5  5008.1   51.42  5010.6   51.89
  5010.7   51.91  5016.9   53.21  5027.5   55.43 5047.19   60.18  5047.3   60.21
  5051.3   61.17  5110.4    63.2  5111.5   63.18    5174   62.19  5177.1   62.13
  5241.7   60.87  5242.7   60.86  5291.5   60.48  5292.9   60.49  5334.7   60.92
  5410.1   62.68  5423.4   62.69  5500.1   62.78  5545.1   62.28  5608.4   62.23
  5674.4   62.17  5780.1   62.08  5855.1   63.58    6024   63.28    6054   62.28
  6119.4   62.99  6144.4   63.26  6155.6   63.38    6239   64.28  6271.1   64.31
    6364   64.38    6514   64.78  6552.8   65.08  6627.8   64.38  6772.8   65.88
  6802.8   66.48  6812.5   66.28
BR D #Mann= 8
  3238.8      .2  3238.8      .1  3683.3     .12  3823.2     .06  4718.3     .08
  4957.1    .035  5051.3     .06  6271.1      .2
BR D Banks=4957.1,5051.3
BC Design=,, 0 ,, 0 ,,,,,,
BC HTab HWMax=66.53
BC Use User HTab Curves=0
BC User HTab FreeFlow(D)= 0

Type RM Length L Ch R = 1 ,107333.3,446.43,444.62,442.52
BEGIN DESCRIPTION:
Downstream Section of Bridge/Culvert/Weir
END DESCRIPTION:
XS GIS Cut Line= 6
      3082226.29     13793528.64      3081904.35     13792520.02
      3081835.67     13792231.58      3081835.67     13792087.37
      3081914.46     13790757.27      3081845.04     13790018.92
#Sta/Elev= 30
  3238.8   64.09  3338.8   63.27  3373.8   61.87  3683.3   62.22  3823.2   62.35
  3896.5   61.17  3986.5   62.07  4224.7   60.97  4572.5   61.57  4617.5   59.57
  4718.3   59.48  4864.2   61.38  4923.3   61.46  4957.1   59.98  4991.9   51.04
  4993.4    49.2  5000.4   49.19  5007.3   49.49  5008.1   51.41  5051.3   61.16
  5110.4   63.19  5291.5   60.47  5410.1   62.67  5780.1   62.07  5855.1   63.57
    6024   63.27    6054   62.27  6271.1    64.3  6627.8   64.37  6812.5   66.27
#Mann= 8 , 1 , 0
  3238.8      .2       0  3238.8      .1       0  3683.3     .12       0
  3823.2     .06       0  4718.3     .08       0  4957.1    .035       0
  5051.3     .06       0  6271.1      .2       0
#XS Ineff= 2 , 0
       0    4945   60.59    5057       0   61.37
Permanent Ineff=
       F       F
Bank Sta=4957.1,5051.3
XS Rating Curve= 0 ,0
Exp/Cntr=0.5,0.3

Type RM Length L Ch R = 1 ,106888.6,184.28,186.63,187.7
BEGIN DESCRIPTION:
Cross Section 108986.0 - Interpolated
END DESCRIPTION:
XS GIS Cut Line= 5
      3082263.03     13793176.93      3082284.34     13792287.48
      3082300.31     13791696.29      3082284.34     13791041.18
      3082124.55     13790460.65
#Sta/Elev= 30
  3671.3   62.97  3981.3   62.18  4011.3   63.86  4141.3   62.49  4281.3   64.03
  4541.3   63.26    4621   61.76    4651   60.03    4691   60.52    4721   59.98
    4761   62.06    4821   63.61    4881   62.43    4911   63.04  4953.2   61.34
  4972.9   53.57  4986.8   50.14  4995.6   50.12  4996.9   48.77  4998.3   48.56
  5003.2   48.96    5004   50.01  5024.3   54.43  5039.1    60.8  5042.5   61.67
    5061   63.16  5152.4   63.23  5192.4   61.17    6313   63.31  6409.8   63.02
#Mann= 5 , 1 , 0
  3671.3      .2       0  3671.3     .06       0  4953.2    .035       0
  5042.5     .08       0    6313      .2       0
Bank Sta=4953.2,5042.5
XS Rating Curve= 0 ,0
Exp/Cntr=0.5,0.3

Type RM Length L Ch R = 1 ,106702  ,48,48,48
BEGIN DESCRIPTION:
Upstream Section of Bridge/Culvert/Weir
END DESCRIPTION:
XS GIS Cut Line= 4
      3082463.56     13792630.04      3082466.91     13792114.99
      3082516.29     13791297.49      3082264.86     13790439.62
#Sta/Elev= 30
    4227   64.45  4410.9   63.15  4490.9   63.75  4620.9   61.75  4660.9   60.05
  4710.9   60.15  4781.8   58.57  4924.9    61.7  4953.2   61.03  4972.9   53.26
  4982.1      52  4986.7   49.83  4995.6   49.81  4996.2   48.78  4998.3   48.25
  5003.2   48.65    5004    49.7  5008.4   50.63  5012.3   50.12  5042.4   61.36
    5096   59.79  5155.9   60.62  5277.7   60.49  5310.9   61.55  5350.9   60.65
  5441.5   61.45  5728.4   61.55  5998.4   62.85  6347.6   63.11    6455   63.55
#Mann= 4 , 1 , 0
    4227     .06       0  4953.2    .035       0  5042.4     .08       0
  6347.6      .2       0
#XS Ineff= 2 , 0
       0    4954      60    5053       0   61.99
Permanent Ineff=
       F       F
Bank Sta=4953.2,5042.4
XS Rating Curve= 0 ,0
Exp/Cntr=0.5,0.3