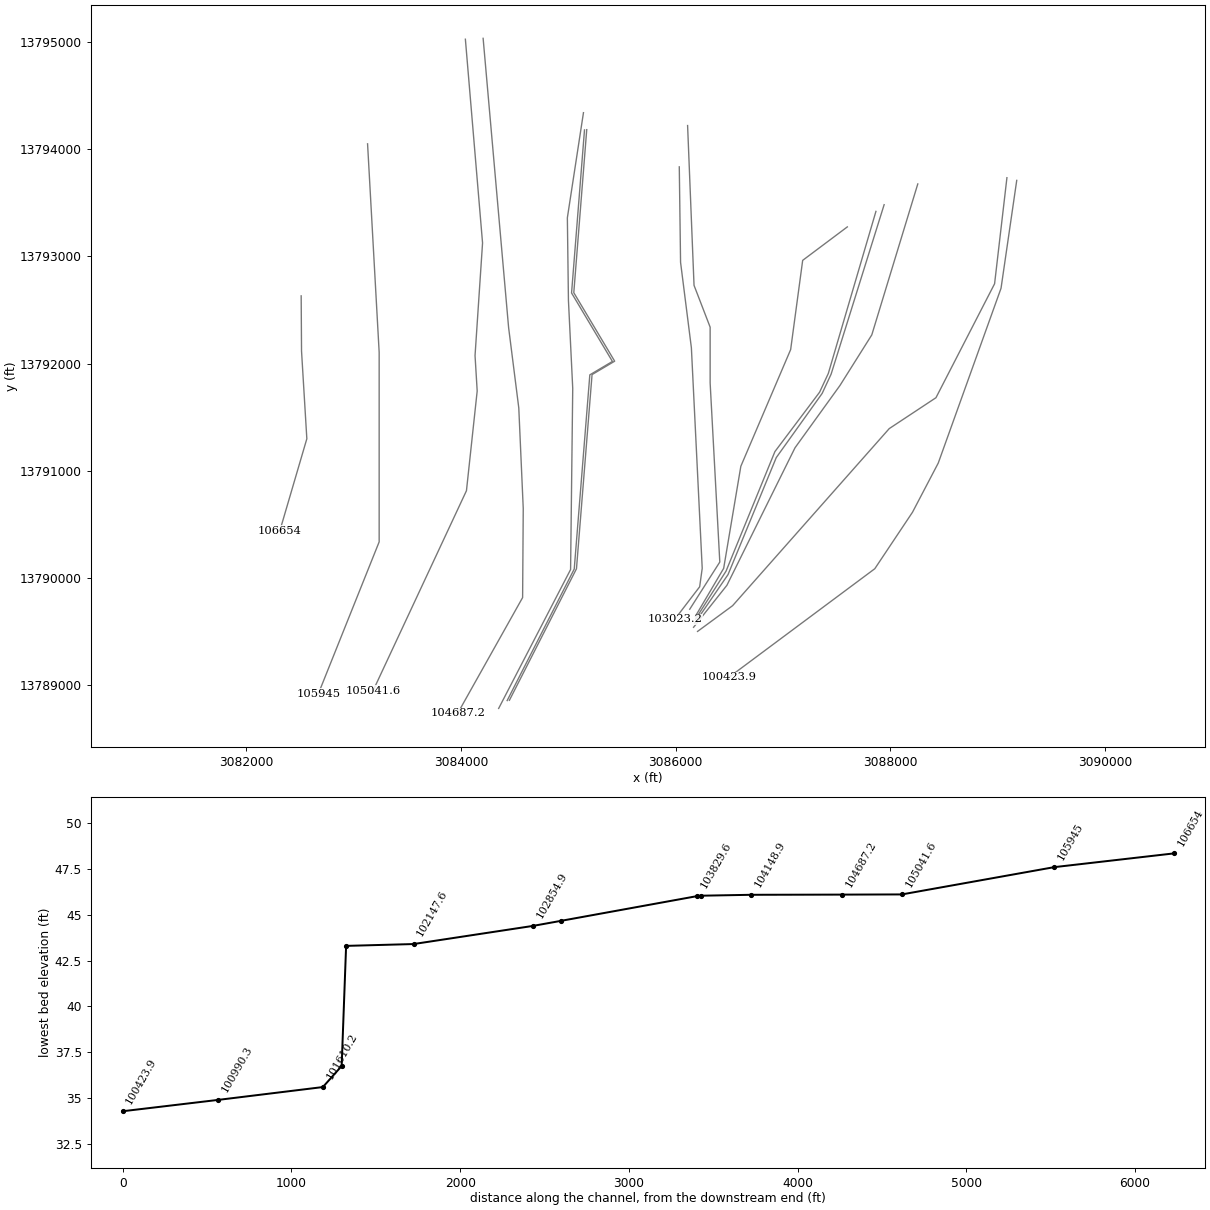
HEC-RAS study C100-00-00.prj: C100-00-00

--- C100-00-00.g01 (geometry) --- (continued)

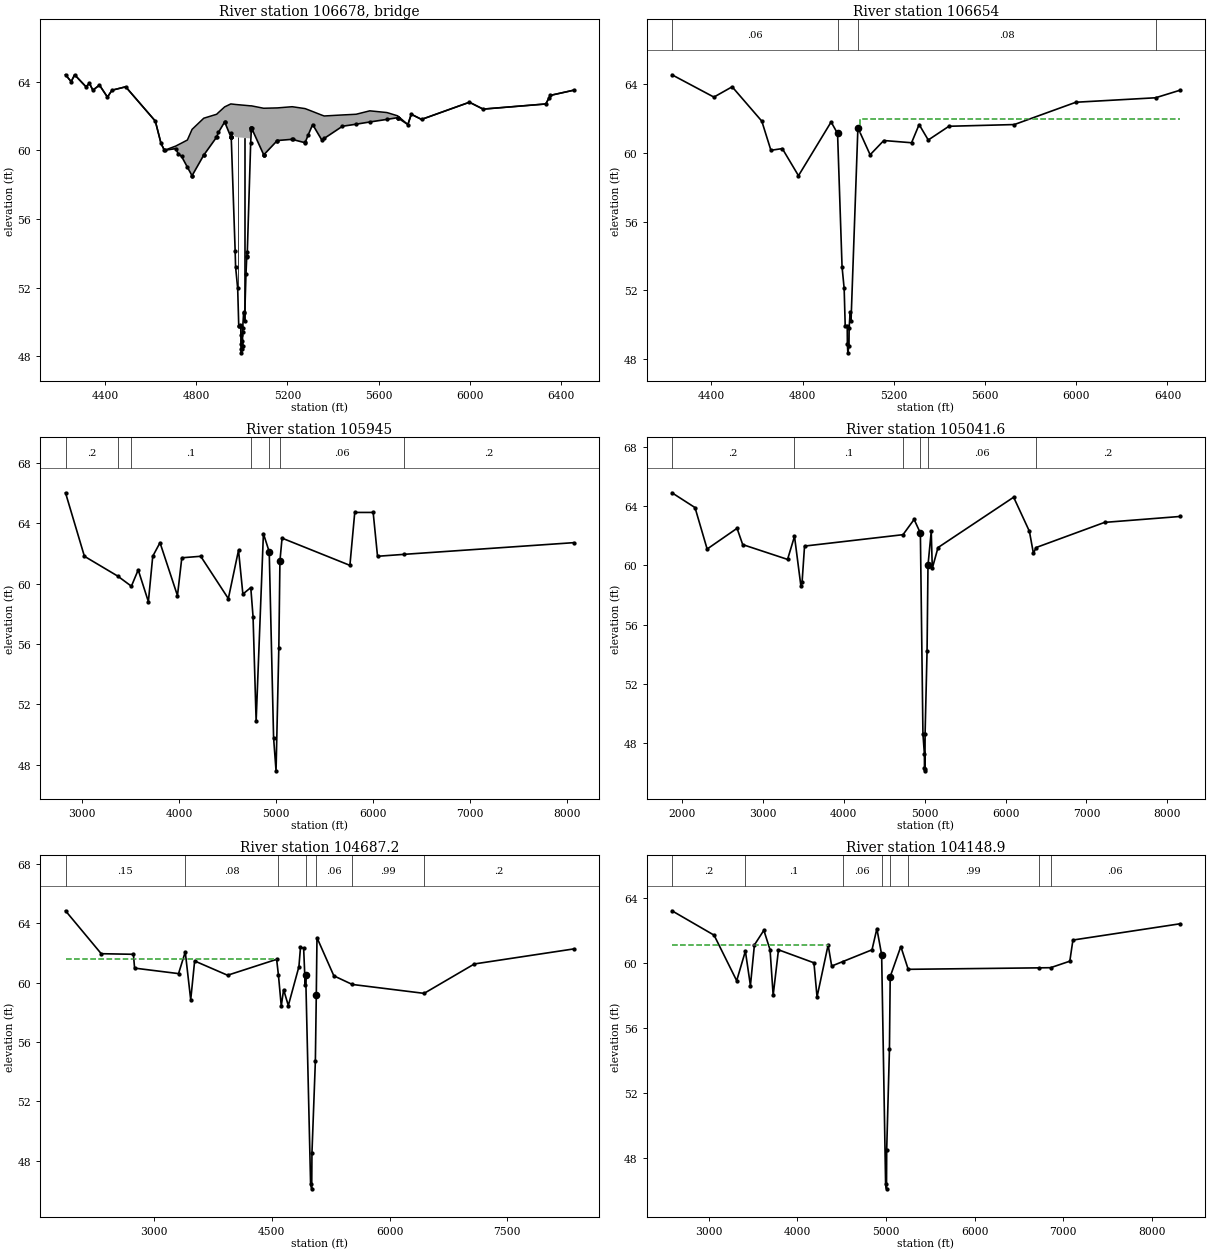
Type RM Length L Ch R = 3 ,106678  ,,,
BEGIN DESCRIPTION:
BLUE RIDGE ROAD
Structure ID: C00-48
END DESCRIPTION:
Bridge Culvert--1,0,-1,-1, 0
Deck Dist Width WeirC Skew NumUp NumDn MinLoCord MaxHiCord MaxSubmerge Is_Ogee
10,28,2.6,0, 48, 48, , , 0.95, 0, 1,1,,
    4227    4252    4267    4317    4332    4347  4375.9  4410.9  4430.9  4490.9
  4620.9  4645.9  4660.9  4710.9  4720.9  4735.7  4761.4    4782  4833.3  4889.8
  4897.6  4924.9  4951.5  4952.7  4953.2  4972.9  5039.1  5042.5    5096  5155.9
  5221.1  5277.7  5310.9  5350.9  5361.4  5441.5  5501.4  5561.4  5636.4  5683.4
  5728.4  5743.4  5788.4  5998.4  6058.4  6333.4  6353.4    6455
    64.4      64    64.4    63.7    63.9    63.5    63.8    63.1    63.5    63.7
    61.7    60.4      60   60.25   60.32   60.42    60.6   61.22   61.87    62.1
    62.2   62.53    62.7    62.7    62.7   62.67   62.59   62.59   62.45   62.47
   62.54   62.43   62.26   62.05      62   62.06    62.1    62.3    62.2   62.01
    61.5    62.1    61.8    62.8    62.4    62.7    63.2    63.5
    64.4      64    64.4    63.7    63.9    63.5    63.8    63.1    63.5    63.7
    61.7    60.4      60    60.1    59.8   59.65   59.02   58.52   59.72   60.78
   61.04   61.65    60.8    60.8   60.98   60.77   60.69   61.31   59.74   60.57
   60.64   60.44    61.5    60.6   60.69    61.4   61.52   61.65    61.8    61.9
    61.5    62.1    61.8    62.8    62.4    62.7    63.2    63.5
    4227    4252    4267    4317    4332    4347  4375.9  4410.9  4430.9  4490.9
  4620.9  4645.9  4660.9  4710.9  4720.9  4735.7  4761.4    4782  4833.3  4889.8
  4897.6  4924.9  4951.5  4952.7  4953.2  4972.9  5039.1  5042.5    5096  5155.9
  5221.1  5277.7  5310.9  5350.9  5361.4  5441.5  5501.4  5561.4  5636.4  5683.4
  5728.4  5743.4  5788.4  5998.4  6058.4  6333.4  6353.4    6455
   64.48   64.08   64.48   63.78   63.98   63.58   63.88   63.18   63.58   63.78
   61.78   60.48   60.08   60.25   60.32   60.42    60.6   61.22   61.87    62.1
    62.2   62.53    62.7    62.7    62.7   62.67   62.59   62.59   62.45   62.47
   62.54   62.43   62.26   62.05      62   62.06    62.1    62.3    62.2   62.01
   61.58   62.18   61.88   62.88   62.48   62.78   63.28   63.58
   64.48   64.08   64.48   63.78   63.98   63.58   63.88   63.18   63.58   63.78
   61.78   60.48   60.08   60.18   59.88   59.73    59.1    58.6    59.8   60.86
   61.12   61.73   60.88   60.88   61.06   60.85   60.77   61.39   59.82   60.65
   60.72   60.52   61.58   60.68   60.77   61.48    61.6   61.73   61.88   61.98
   61.58   62.18   61.88   62.88   62.48   62.78   63.28   63.58
Pier Skew, UpSta & Num, DnSta & Num=  ,4982.1, 2 ,4982.1, 2 , 0 , 0 , 0 ,,
     1.4     1.4
   50.62   61.76
     1.4     1.4
    50.7   61.84
Pier Skew, UpSta & Num, DnSta & Num=  ,5012.3, 2 ,5012.3, 2 , 0 , 0 , 0 ,,
     1.4     1.4
   49.18   61.73
     1.4     1.4
   49.26   61.81
Abutment Skew #Up #Dn= , 2 , 2
  4951.5  4986.8
    60.8   49.78
  4951.5  4986.8
   60.88   49.86
Abutment Skew #Up #Dn= , 2 , 2
  5021.9 5042.79
   53.82    61.3
  5021.9 5042.79
    53.9   61.38
BR Coef= 1 , 1 , 0 ,1.25, 0 ,,,0.8,0,2,0,
WSPro=,,,, 1 ,,,, 0 ,,,, 0 ,,,,-1 ,-1 ,-1 , 0 , 0 , 0 , 0 , 0
BR U #Sta/Elev= 91
    4227    64.4    4252      64    4267    64.4    4317    63.7    4332    63.9
    4347    63.5  4375.9    63.8  4410.9    63.1  4430.9    63.5  4490.9    63.7
  4620.9    61.7  4645.9    60.4  4660.9      60  4661.4      60  4710.9    60.1
  4720.9    59.8  4735.7   59.65  4761.4   59.02  4781.8   58.52    4782   58.52
  4833.3   59.72  4833.4   59.72  4888.8   60.75  4889.8   60.78  4897.6   61.04
  4924.9   61.65    4925   61.65  4951.5    60.8 4951.61   60.79  4951.7   60.79
  4951.9   60.79  4952.7   60.76  4953.2   60.98    4971   54.13  4972.9   53.21
  4982.1   51.95  4986.7   49.78  4986.8   49.78  4990.8   49.82  4995.6   49.76
  4996.1   49.24  4996.2   48.73  4996.9   48.41  4998.3    48.2  5000.8   48.43
  5002.2   48.87  5003.2    48.6  5003.7   49.44    5004   49.65  5008.4   50.58
  5009.5    50.5  5012.3   50.07  5018.4   52.77  5021.8   53.81  5021.9   53.82
  5024.3   54.07  5039.1   60.44    5042    61.2  5042.4   61.31  5042.5   61.31
 5042.59    61.3  5042.7    61.3  5095.8   59.75    5096   59.74  5097.6   59.75
  5155.9   60.57  5156.6   60.57  5221.1   60.64    5223   60.63  5277.7   60.44
  5278.6   60.47  5291.5    60.9  5310.9    61.5  5350.9    60.6  5361.4   60.69
  5441.5    61.4  5501.4   61.52  5561.4   61.65  5636.4    61.8  5683.4    61.9
  5686.4   61.87  5686.5   61.87  5728.4    61.5  5743.4    62.1  5788.4    61.8
  5998.4    62.8  6058.4    62.4  6333.4    62.7  6347.6   63.06  6353.4    63.2
    6455    63.5
BR U #Mann= 4
    4227     .06  4953.2    .035  5042.4     .08  6347.6      .2
BR U Banks=4953.2,5042.4
BR D #Sta/Elev= 91
    4227   64.48    4252   64.08    4267   64.48    4317   63.78    4332   63.98
    4347   63.58  4375.9   63.88  4410.9   63.18  4430.9   63.58  4490.9   63.78
  4620.9   61.78  4645.9   60.48  4660.9   60.08  4661.4   60.08  4710.9   60.18
  4720.9   59.88  4735.7   59.73  4761.4    59.1  4781.8    58.6    4782    58.6
  4833.3    59.8  4833.4    59.8  4888.8   60.83  4889.8   60.86  4897.6   61.12
  4924.9   61.73    4925   61.73  4951.5   60.88 4951.61   60.87  4951.7   60.87
  4951.9   60.87  4952.7   60.84  4953.2   61.06    4971   54.21  4972.9   53.29
  4982.1   52.03  4986.7   49.86  4986.8   49.86  4990.8    49.9  4995.6   49.84
  4996.1   49.32  4996.2   48.81  4996.9   48.49  4998.3   48.28  5000.8   48.51
  5002.2   48.95  5003.2   48.68  5003.7   49.52    5004   49.73  5008.4   50.66
  5009.5   50.58  5012.3   50.15  5018.4   52.85  5021.8   53.89  5021.9    53.9
  5024.3   54.15  5039.1   60.52    5042   61.28  5042.4   61.39  5042.5   61.39
 5042.59   61.38  5042.7   61.38  5095.8   59.83    5096   59.82  5097.6   59.83
  5155.9   60.65  5156.6   60.65  5221.1   60.72    5223   60.71  5277.7   60.52
  5278.6   60.55  5291.5   60.98  5310.9   61.58  5350.9   60.68  5361.4   60.77
  5441.5   61.48  5501.4    61.6  5561.4   61.73  5636.4   61.88  5683.4   61.98
  5686.4   61.95  5686.5   61.95  5728.4   61.58  5743.4   62.18  5788.4   61.88
  5998.4   62.88  6058.4   62.48  6333.4   62.78  6347.6   63.14  6353.4   63.28
    6455   63.58
BR D #Mann= 4
    4227     .06  4953.2    .035  5042.4     .08  6347.6      .2
BR D Banks=4953.2,5042.4
BC Design=,, 0 ,, 0 ,,,,,,
BC HTab HWMax=64.45
BC Use User HTab Curves=0
BC User HTab FreeFlow(D)= 0

Type RM Length L Ch R = 1 ,106654  ,712.21,708.99,705.82
BEGIN DESCRIPTION:
Downstream Section of Bridge/Culvert/Weir
END DESCRIPTION:
XS GIS Cut Line= 4
       3082511.5     13792632.33      3082514.85     13792117.29
      3082564.23     13791299.79       3082312.8     13790441.92
#Sta/Elev= 30
    4227   64.56  4410.9   63.26  4490.9   63.86  4620.9   61.86  4660.9   60.16
  4710.9   60.26  4781.8   58.68  4924.9   61.81  4953.2   61.14  4972.9   53.37
  4982.1   52.11  4986.7   49.94  4995.6   49.92  4996.2   48.89  4998.3   48.36
  5003.2   48.76    5004   49.81  5008.4   50.74  5012.3   50.23  5042.4   61.47
    5096    59.9  5155.9   60.73  5277.7    60.6  5310.9   61.66  5350.9   60.76
  5441.5   61.56  5728.4   61.66  5998.4   62.96  6347.6   63.22    6455   63.66
#Mann= 4 , 1 , 0
    4227     .06       0  4953.2    .035       0  5042.4     .08       0
  6347.6      .2       0
#XS Ineff= 2 , 0
       0    4954      60    5053       0   61.99
Permanent Ineff=
       F       F
Bank Sta=4953.2,5042.4
XS Rating Curve= 0 ,0
Exp/Cntr=0.5,0.3

Type RM Length L Ch R = 1 ,105945  ,899.08,903.42,905.93
BEGIN DESCRIPTION:
Cross Section 108043.1-Interpolated
END DESCRIPTION:
XS GIS Cut Line= 5
        3083130.     13794050.26      3083237.99     13792106.49
      3083237.99     13791904.02      3083237.99     13790338.21
      3082671.06     13788920.88
#Sta/Elev= 30
  2828.3      66  3023.3    61.8    3367   60.49  3508.1   59.82  3578.3    60.9
  3683.3    58.8  3728.3    61.8  3803.3    62.7  3983.3    59.2  4028.3    61.7
  4223.3    61.8  4508.3      59  4613.3    62.2  4658.3    59.3  4739.8   59.73
  4763.3    57.8  4795.1    50.9  4870.1    63.3  4930.1    62.1  4975.1    49.8
  5000.5   47.61  5029.1   55.71  5040.7    61.5  5062.5      63  5762.5    61.2
  5812.5    64.7  6002.5    64.7  6047.5    61.8  6325.6   61.93  8069.9    62.7
#Mann= 7 , 1 , 0
  2828.3      .2       0    3367     .06       0  3508.1      .1       0
  4739.8     .06       0  4930.1    .035       0  5040.7     .06       0
  6325.6      .2       0
Bank Sta=4930.1,5040.7
XS Rating Curve= 0 ,0
Exp/Cntr=0.3,0.1

Type RM Length L Ch R = 1 ,105041.6,350.36,354.39,358.32
BEGIN DESCRIPTION:
Cross Section  107139.5
END DESCRIPTION:
XS GIS Cut Line= 6
      3084041.23     13795025.71      3084201.25     13793125.53
      3084131.24     13792075.43      3084151.24      13791745.4
      3084051.23     13790815.31      3083181.15     13788950.14
#Sta/Elev= 30
  1873.6    64.9  2158.6    63.9  2308.6    61.1  2678.6    62.5  2748.6    61.4
  3303.6    60.4  3389.3   61.96  3468.6    58.6  3483.6    58.9  3513.6    61.3
  4731.6   62.07    4869    63.1  4946.5   62.18  4978.2   48.62  4996.2   47.25
  4997.1   46.29  5000.5   46.12  5002.8   46.23  5004.8   48.64  5029.1   54.22
  5040.7   60.01  5080.8   62.29    5094    59.8  5164.7    61.2  6100.1    64.6
  6295.1    62.3  6345.1    60.8  6377.2    61.2  7225.1    62.9  8158.3    63.3
#Mann= 6 , 1 , 0
  1873.6      .2       0  3389.3      .1       0  4731.6     .06       0
  4946.5    .035       0  5040.7     .06       0  6377.2      .2       0
Bank Sta=4946.5,5040.7
XS Rating Curve= 0 ,0
Exp/Cntr=0.3,0.1

Type RM Length L Ch R = 1 ,104687.2,542.98,538.32,533.64
BEGIN DESCRIPTION:
Cross Section 106784.0-Interpolated
END DESCRIPTION:
XS GIS Cut Line= 6
 3084206.560108713795033.8866269 3084443.880108713792337.3266269
 3084538.810108713791586.8066269 3084580.340108713790649.3866269
 3084574.410108713789818.7666269 3083969.240108713788738.9566269
#Sta/Elev= 30
  1871.8   64.83  2326.8   61.94  2736.8    61.9  2751.8   60.97  3311.8    60.6
  3397.2   62.06  3466.8   58.84  3516.8   61.45  3936.2   60.49  4561.2   61.56
  4583.9   60.52  4620.2   58.42  4650.2   59.52  4710.2   58.45  4845.2   61.07
  4865.2   62.37  4905.2   62.31  4925.2   59.83  4931.4   60.51 4993.84   46.43
 5008.12   46.11  5011.2   48.52  5054.6    54.7  5066.5   59.16  5075.2   63.02
  5290.2   60.45  5524.8   59.87  6439.8   59.27    7080   61.25  8343.5   62.26
#Mann= 7 , 1 , 0
  1871.8     .15       0  3397.2     .08       0  4583.9     .06       0
  4931.4    .035       0  5066.5     .06       0  5524.8     .99       0
  6439.8      .2       0
#XS Ineff= 2 , 0
       0    4553    61.6               0
Permanent Ineff=
       F       F
Bank Sta=4931.4,5066.5
XS Rating Curve= 0 ,0
Exp/Cntr=0.3,0.1

Type RM Length L Ch R = 1 ,104148.9,381.37,298.28,187.27
BEGIN DESCRIPTION:
Cross Section  106247.1
END DESCRIPTION:
XS GIS Cut Line= 6
      3085141.33     13794340.65      3084991.32     13793360.55
      3085001.32     13792590.48      3085041.32      13791770.4
      3085021.32     13790080.24      3084351.26     13788785.12
#Sta/Elev= 30
  2585.7    63.2  3060.7    61.7  3315.7    58.9  3413.8   60.72  3470.7    58.6
  3515.7    61.1  3622.2      62  3692.2    60.8  3727.2      58  3787.2    60.8
  4187.2      60  4222.2    57.9  4347.3    61.1  4387.3    59.8  4510.2   60.07
  4842.3    60.8  4897.3    62.1    4951    60.5  4995.6   46.42  5005.8    46.1
    5008   48.51    5039   54.69  5047.5   59.15  5167.3      61  5250.7    59.6
  6720.7   59.69  6856.9    59.7  7073.7    60.1  7108.7    61.4  8316.9    62.4
#Mann= 8 , 1 , 0
  2585.7      .2       0  3413.8      .1       0  4510.2     .06       0
    4951    .035       0  5047.5     .06       0  5250.7     .99       0
  6720.7     .06       0  6856.9     .06       0
#XS Ineff= 2 , 0
       0    4344    61.1               0
Permanent Ineff=
       F       F
Bank Sta=4951,5047.5
XS Rating Curve= 0 ,0
Exp/Cntr=0.5,0.3

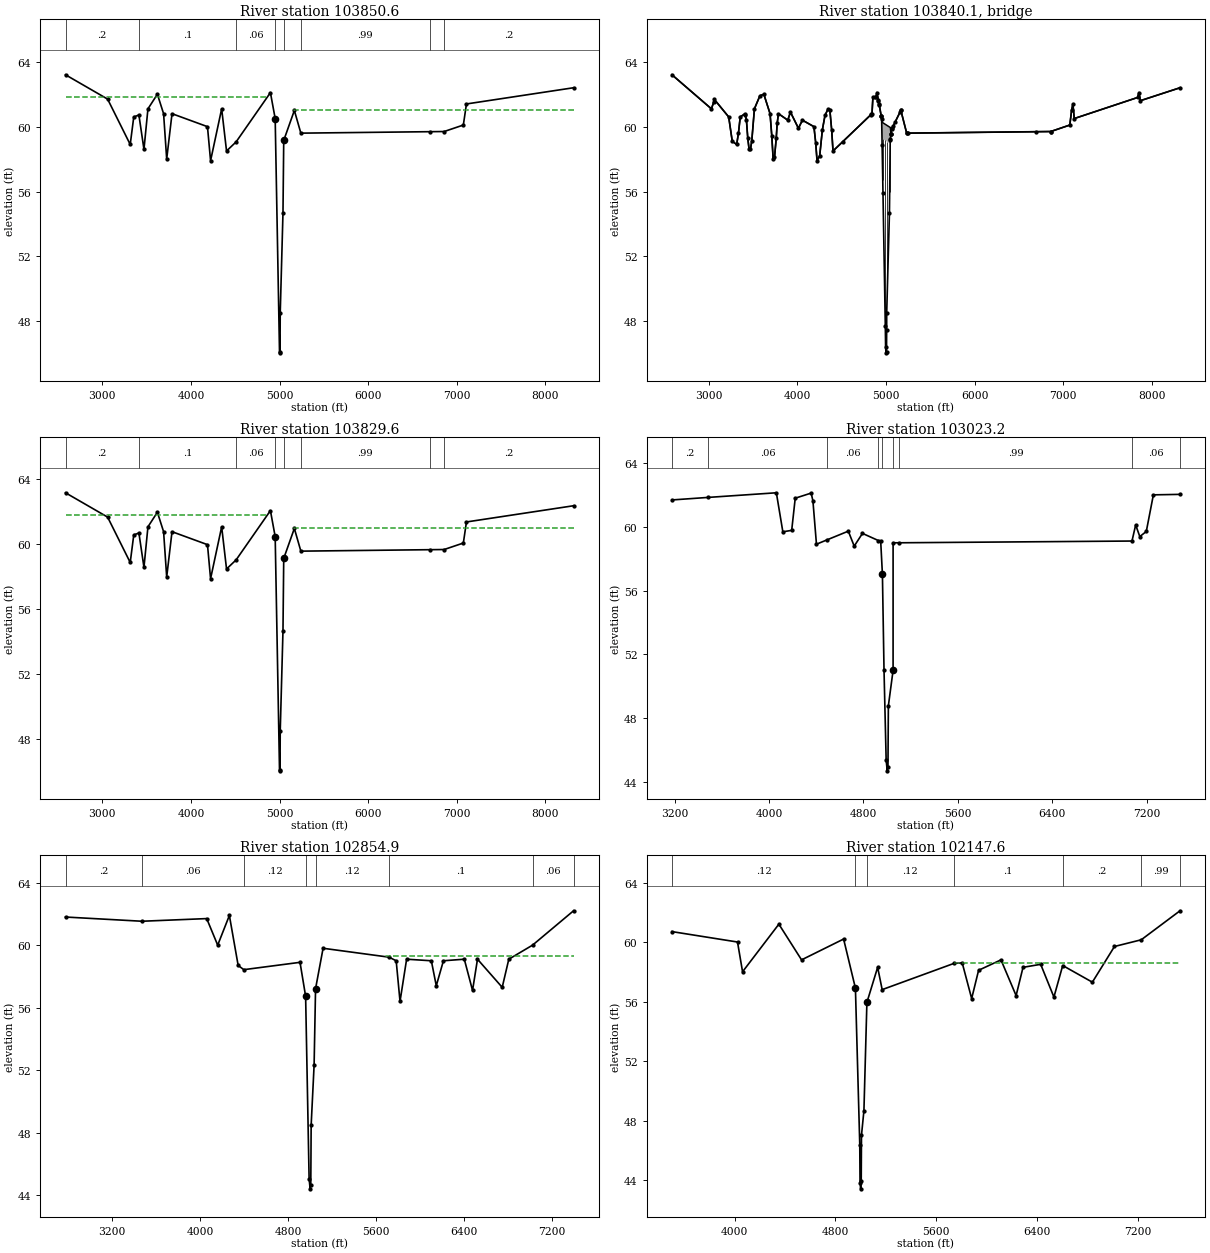
Type RM Length L Ch R = 1 ,103850.6,21.11,21.04,18.26
BEGIN DESCRIPTION:
Upstream Section of Bridge/Culvert/Weir
END DESCRIPTION:
XS GIS Cut Line= 6
      3085151.01     13794179.92       3085030.4     13792659.38
      3085411.19     13792020.69      3085200.55     13791895.76
      3085055.33     13790084.87      3084430.48     13788858.33
#Sta/Elev= 30
  2585.7    63.2  3060.7    61.7  3315.7    58.9  3355.7    60.6  3413.8   60.72
  3470.7    58.6  3515.7    61.1  3622.2      62  3692.2    60.8  3727.2      58
  3787.2    60.8  4187.2      60  4222.2    57.9  4347.3    61.1  4402.3    58.5
  4510.2   59.06  4897.3    62.1    4951    60.5    5000   46.05  5005.8    46.1
    5008   48.51    5039   54.69  5047.5   59.15  5167.3      61  5240.7    59.6
  6695.7   59.69  6856.9    59.7  7073.7    60.1  7108.7    61.4  8316.9    62.4
#Mann= 8 ,-1 , 0
  2585.7      .2       0  3413.8      .1       0  4510.2     .06       0
    4951    .035       0  5047.5     .06       0  5240.7     .99       0
  6695.7     .06       0  6856.9      .2       0
#XS Ineff= 2 , 0
       0    4852    61.8    5167       0      61
Permanent Ineff=
       F       F
Bank Sta=4951,5047.5
XS Rating Curve= 0 ,0
Exp/Cntr=0.5,0.3

Type RM Length L Ch R = 3 ,103840.1,,,
BEGIN DESCRIPTION:
12" DIA. PIPE
END DESCRIPTION:
Bridge Culvert--1,0,-1,-1, 0
Deck Dist Width WeirC Skew NumUp NumDn MinLoCord MaxHiCord MaxSubmerge Is_Ogee
10,1,2.6,0, 60, 60, , , 0.95, 0, 1,1,,
  2585.7  3030.7  3055.7  3060.7  3225.7  3265.7  3315.7  3335.7  3355.7  3410.7
  3425.7  3440.7  3455.7  3470.7  3485.7  3515.7  3577.2  3622.2  3692.2  3712.2
  3727.2  3742.2  3762.2  3772.2  3787.2  3892.2  3922.2  4012.2  4057.2  4187.2
  4207.2  4222.2  4252.2  4282.2  4312.2  4347.3  4367.3  4387.3  4402.3  4842.3
  4852.3  4887.3  4897.3    4951 4956.47    5039 5049.07 5056.36  5062.9  5167.3
  5233.4  6858.7  7073.7  7093.7  7108.7  7123.7  7838.7  7853.7  7868.7  8316.9
    63.2    61.1    61.5    61.7    60.6    59.1    58.9    59.6    60.6    60.8
    60.4    59.3    58.6    58.6    59.1    61.1    61.9      62    60.8    59.4
      58    58.1    59.3    60.2    60.8    60.4    60.9    59.9    60.4      60
      59    57.9    58.2    59.8    60.7    61.1      61    59.8    58.5   60.81
   61.81   61.81   62.11   60.51   60.27   59.98   59.95   59.55   59.84      61
    59.6    59.7    60.1      61    61.4    60.5    61.8    62.1    61.6    62.4
    63.2    61.1    61.5    61.7    60.6    59.1    58.9    59.6    60.6    60.8
    60.4    59.3    58.6    58.6    59.1    61.1    61.9      62    60.8    59.4
      58    58.1    59.3    60.2    60.8    60.4    60.9    59.9    60.4      60
      59    57.9    58.2    59.8    60.7    61.1      61    59.8    58.5    60.8
    61.8    61.8    62.1    60.5   59.27   58.98   59.22   59.54   59.83      61
    59.6    59.7    60.1      61    61.4    60.5    61.8    62.1    61.6    62.4
  2585.7  3030.7  3055.7  3060.7  3225.7  3265.7  3315.7  3335.7  3355.7  3410.7
  3425.7  3440.7  3455.7  3470.7  3485.7  3515.7  3577.2  3622.2  3692.2  3712.2
  3727.2  3742.2  3762.2  3772.2  3787.2  3892.2  3922.2  4012.2  4057.2  4187.2
  4207.2  4222.2  4252.2  4282.2  4312.2  4347.3  4367.3  4387.3  4402.3  4842.3
  4852.3  4887.3  4897.3    4951 4956.47    5039 5049.07 5056.36  5062.9  5167.3
  5233.4  6858.7  7073.7  7093.7  7108.7  7123.7  7838.7  7853.7  7868.7  8316.9
    63.2    61.1    61.5    61.7    60.6    59.1    58.9    59.6    60.6    60.8
    60.4    59.3    58.6    58.6    59.1    61.1    61.9      62    60.8    59.4
      58    58.1    59.3    60.2    60.8    60.4    60.9    59.9    60.4      60
      59    57.9    58.2    59.8    60.7    61.1      61    59.8    58.5   60.81
   61.81   61.81   62.11   60.51   60.27   59.98   59.95   59.55   59.84      61
    59.6    59.7    60.1      61    61.4    60.5    61.8    62.1    61.6    62.4
    63.2    61.1    61.5    61.7    60.6    59.1    58.9    59.6    60.6    60.8
    60.4    59.3    58.6    58.6    59.1    61.1    61.9      62    60.8    59.4
      58    58.1    59.3    60.2    60.8    60.4    60.9    59.9    60.4      60
      59    57.9    58.2    59.8    60.7    61.1      61    59.8    58.5    60.8
    61.8    61.8    62.1    60.5   59.27   58.98   59.22   59.54   59.83      61
    59.6    59.7    60.1      61    61.4    60.5    61.8    62.1    61.6    62.4
Pier Skew, UpSta & Num, DnSta & Num=  ,4963.4, 2 ,4963.4, 2 , 0 , 0 , 0 ,,
       1       1
   55.59   60.25
       1       1
   55.59   60.25
Pier Skew, UpSta & Num, DnSta & Num=  ,4989, 2 ,4989, 2 , 0 , 0 , 0 ,,
       1       1
   47.61   60.16
       1       1
   47.61   60.16
Pier Skew, UpSta & Num, DnSta & Num=  ,5015.3, 2 ,5015.3, 2 , 0 , 0 , 0 ,,
       1       1
   48.86   60.07
       1       1
   48.86   60.07
Pier Skew, UpSta & Num, DnSta & Num=  ,5041.4, 2 ,5041.4, 2 , 0 , 0 , 0 ,,
       1       1
   54.67   60.04
       1       1
   54.67   60.04
BR Coef= 1 , 1 , 0 ,1.25, 0 ,,,0.8,0,2,0,
WSPro=,,,, 1 ,,,, 0 ,,,, 0 ,,,,-1 ,-1 ,-1 , 0 , 0 , 0 , 0 , 0
BR U #Sta/Elev= 91
  2585.7    63.2  3030.7    61.1  3055.7    61.5  3060.7    61.7  3225.7    60.6
  3265.7    59.1  3315.7    58.9  3335.7    59.6  3355.7    60.6  3410.7    60.8
  3413.8   60.72  3425.7    60.4  3440.7    59.3  3455.7    58.6  3470.7    58.6
  3485.7    59.1  3515.7    61.1  3577.2    61.9  3622.2      62  3692.2    60.8
  3712.2    59.4  3727.2      58  3742.2    58.1  3762.2    59.3  3772.2    60.2
  3787.2    60.8  3892.2    60.4  3922.2    60.9  4012.2    59.9  4057.2    60.4
  4187.2      60  4207.2      59  4222.2    57.9  4252.2    58.2  4282.2    59.8
  4312.2    60.7  4347.3    61.1  4367.3      61  4387.3    59.8  4402.3    58.5
  4510.2   59.06  4831.1   60.74  4836.1   60.77  4842.3    60.8  4852.3    61.8
  4871.1    61.8  4887.3    61.8  4897.3    62.1  4911.1   61.64  4912.3    61.6
  4924.2   61.38  4926.1   61.32 4945.77   60.67 4945.88   60.67 4946.07   60.66
    4951    60.5 4956.47   58.84  4966.2   55.88  4992.4    47.7  4995.6   46.42
    5000   46.05  5005.8    46.1  5007.7   47.48    5008   48.51    5039   54.69
  5047.5   59.15 5049.07   59.22 5056.36   59.54 5056.47   59.55 5056.57   59.55
  5062.9   59.83  5071.1   59.92  5081.1   60.03  5101.1   60.26  5159.7   60.91
  5167.3      61  5168.4      61  5233.4    59.6  5240.7    59.6  5243.4    59.6
  6695.7   59.69  6856.9    59.7  6858.7    59.7  7073.7    60.1  7093.7      61
  7108.7    61.4  7123.7    60.5  7838.7    61.8  7853.7    62.1  7868.7    61.6
  8316.9    62.4
BR U #Mann= 8
  2585.7      .2  3413.8      .1  4510.2     .06    4951    .035  5047.5     .06
  5240.7     .99  6695.7     .06  6856.9      .2
BR U Banks=4951,5047.5
BR D #Sta/Elev= 91
  2585.7    63.2  3030.7    61.1  3055.7    61.5  3060.7    61.7  3225.7    60.6
  3265.7    59.1  3315.7    58.9  3335.7    59.6  3355.7    60.6  3410.7    60.8
  3413.8   60.72  3425.7    60.4  3440.7    59.3  3455.7    58.6  3470.7    58.6
  3485.7    59.1  3515.7    61.1  3577.2    61.9  3622.2      62  3692.2    60.8
  3712.2    59.4  3727.2      58  3742.2    58.1  3762.2    59.3  3772.2    60.2
  3787.2    60.8  3892.2    60.4  3922.2    60.9  4012.2    59.9  4057.2    60.4
  4187.2      60  4207.2      59  4222.2    57.9  4252.2    58.2  4282.2    59.8
  4312.2    60.7  4347.3    61.1  4367.3      61  4387.3    59.8  4402.3    58.5
  4510.2   59.06  4831.1   60.74  4836.1   60.77  4842.3    60.8  4852.3    61.8
  4871.1    61.8  4887.3    61.8  4897.3    62.1  4911.1   61.64  4912.3    61.6
  4924.2   61.38  4926.1   61.32 4945.77   60.67 4945.88   60.67 4946.07   60.66
    4951    60.5 4956.47   58.84  4966.2   55.88  4992.4    47.7  4995.6   46.42
    5000   46.05  5005.8    46.1  5007.7   47.48    5008   48.51    5039   54.69
  5047.5   59.15 5049.07   59.22 5056.36   59.54 5056.47   59.55 5056.57   59.55
  5062.9   59.83  5071.1   59.92  5081.1   60.03  5101.1   60.26  5159.7   60.91
  5167.3      61  5168.4      61  5233.4    59.6  5240.7    59.6  5243.4    59.6
  6695.7   59.69  6856.9    59.7  6858.7    59.7  7073.7    60.1  7093.7      61
  7108.7    61.4  7123.7    60.5  7838.7    61.8  7853.7    62.1  7868.7    61.6
  8316.9    62.4
BR D #Mann= 8
  2585.7      .2  3413.8      .1  4510.2     .06    4951    .035  5047.5     .06
  5240.7     .99  6695.7     .06  6856.9      .2
BR D Banks=4951,5047.5
BC Design=,, 0 ,, 0 ,,,,,,
BC HTab HWMax=63.2
BC Use User HTab Curves=0
BC User HTab FreeFlow(D)= 0

Type RM Length L Ch R = 1 ,103829.6,721.17,806.41,917.84
BEGIN DESCRIPTION:
Downstream Section of Bridge/Culvert/Weir
END DESCRIPTION:
XS GIS Cut Line= 6
      3085171.86     13794182.44      3085051.24      13792661.9
      3085432.03     13792023.21      3085221.39     13791898.28
      3085076.17     13790087.39      3084451.33     13788860.85
#Sta/Elev= 30
  2585.7   63.18  3060.7   61.68  3315.7   58.88  3355.7   60.58  3413.8    60.7
  3470.7   58.58  3515.7   61.08  3622.2   61.98  3692.2   60.78  3727.2   57.98
  3787.2   60.78  4187.2   59.98  4222.2   57.88  4347.3   61.08  4402.3   58.48
  4510.2   59.04  4897.3   62.08    4951   60.48    5000   46.03  5005.8   46.08
    5008   48.49    5039   54.67  5047.5   59.13  5167.3   60.98  5240.7   59.58
  6695.7   59.67  6856.9   59.68  7073.7   60.08  7108.7   61.38  8316.9   62.38
#Mann= 8 ,-1 , 0
  2585.7      .2       0  3413.8      .1       0  4510.2     .06       0
    4951    .035       0  5047.5     .06       0  5240.7     .99       0
  6695.7     .06       0  6856.9      .2       0
#XS Ineff= 2 , 0
       0    4852    61.8    5167       0      61
Permanent Ineff=
       F       F
Bank Sta=4951,5047.5
XS Rating Curve= 0 ,0
Exp/Cntr=0.5,0.3

Type RM Length L Ch R = 1 ,103023.2,170.46,168.29,164.96
BEGIN DESCRIPTION:
Cross Section 105123.0-Interpolated
END DESCRIPTION:
XS GIS Cut Line= 6
      3086034.03     13793835.42       3086045.9     13792945.47
      3086146.76     13792147.48      3086247.62     13790091.68
      3086223.89     13789919.63       3085992.5     13789617.04
#Sta/Elev= 30
  3176.6   61.69  3484.9   61.85  4061.6   62.14  4116.6   59.69  4191.6   59.78
  4221.6    61.8  4356.6   62.12  4371.6   61.63  4401.6   58.91  4486.7   59.17
  4671.6   59.73  4721.6   58.79  4791.6   59.59  4926.6   59.14    4946   59.13
  4960.8   57.01  4974.3   51.01  4992.5   45.34  5001.8   44.68  5007.8   44.94
  5011.2   48.76  5051.2   50.99  5051.3      59  5099.6      59  7076.6   59.11
  7107.9   60.12  7142.9   59.39  7197.9   59.71  7257.9   62.01  7483.8   62.04
#Mann= 9 , 1 , 0
  3176.6      .2       0  3484.9     .06       0  4486.7     .06       0
  4926.6     .06       0  4960.8    .035       0  5051.2     .06       0
  5099.6     .99       0  7076.6     .06       0  7483.8      .2       0
Bank Sta=4960.8,5051.2
XS Rating Curve= 0 ,0
Exp/Cntr=0.3,0.1

Type RM Length L Ch R = 1 ,102854.9,722.39,707.25,687.15
BEGIN DESCRIPTION:
Cross Section  104954.7
END DESCRIPTION:
XS GIS Cut Line= 6
      3086111.43     13794220.63      3086171.43     13792730.49
      3086321.44     13792340.46      3086321.44     13791820.41
      3086411.45     13790150.25      3086131.43     13789710.21
#Sta/Elev= 30
  2775.6    61.8  3471.6   61.53  4060.6    61.7  4160.6      60  4266.9    61.9
  4346.9    58.7  4398.4   58.43  4909.8    58.9  4960.8   56.73  4992.5   45.06
  5001.8    44.4  5007.8   44.66  5011.2   48.48    5038   52.32  5051.2   57.21
  5119.8    59.8  5720.1   59.23  5784.9      59  5819.9    56.4  5879.9    59.1
  6104.9      59  6149.9    57.4  6214.9      59  6404.9    59.1  6479.9    57.1
  6524.9    59.1  6749.9    57.3  6809.9    59.1    7026      60  7399.1    62.2
#Mann= 8 , 1 , 0
  2775.6      .2       0  3471.6     .06       0  4398.4     .12       0
  4960.8    .035       0  5051.2     .12       0  5720.1      .1       0
    7026     .06       0  7399.1      .2       0
#XS Ineff= 2 , 0
       0                    5695       0    59.3
Permanent Ineff=
       F       F
Bank Sta=4960.8,5051.2
XS Rating Curve= 0 ,0
Exp/Cntr=0.3,0.1

Type RM Length L Ch R = 1 ,102147.6,402.78,399.62,395.18
BEGIN DESCRIPTION:
Cross Section  104247.4
END DESCRIPTION:
XS GIS Cut Line= 6
      3087599.57     13793275.55      3087183.53     13792963.52
      3087071.52     13792131.44      3086607.47     13791043.33
      3086447.46     13790091.24      3086183.43      13789643.2
#Sta/Elev= 30
  3503.4    60.7  4023.4      60  4063.4      58  4351.5    61.2  4531.5    58.8
  4865.1    60.2  4958.8    56.9  4993.3   46.37  4995.4   43.83  5000.5   43.41
  5004.9   43.96  5006.9   47.01  5026.3   48.67  5049.9   55.94  5135.1    58.3
    5171    56.8  5739.6   58.56    5806    58.6    5881    56.2    5936    58.1
  6113.6    58.8  6233.6    56.4  6288.6    58.3  6428.6    58.5  6533.6    56.3
  6603.4   58.42  6838.6    57.3    7014    59.7  7226.4   60.15    7534    62.1
#Mann= 7 ,-1 , 0
  3503.4     .12       0  4958.8    .035       0  5049.9     .12       0
  5739.6      .1       0  6603.4      .2       0  7226.4     .99       0
    7534      .2       0
#XS Ineff= 2 , 0
       0                    5740       0    58.6
Permanent Ineff=
       F       F
Bank Sta=4958.8,5049.9
XS Rating Curve= 0 ,0
Exp/Cntr=0.3,0.1

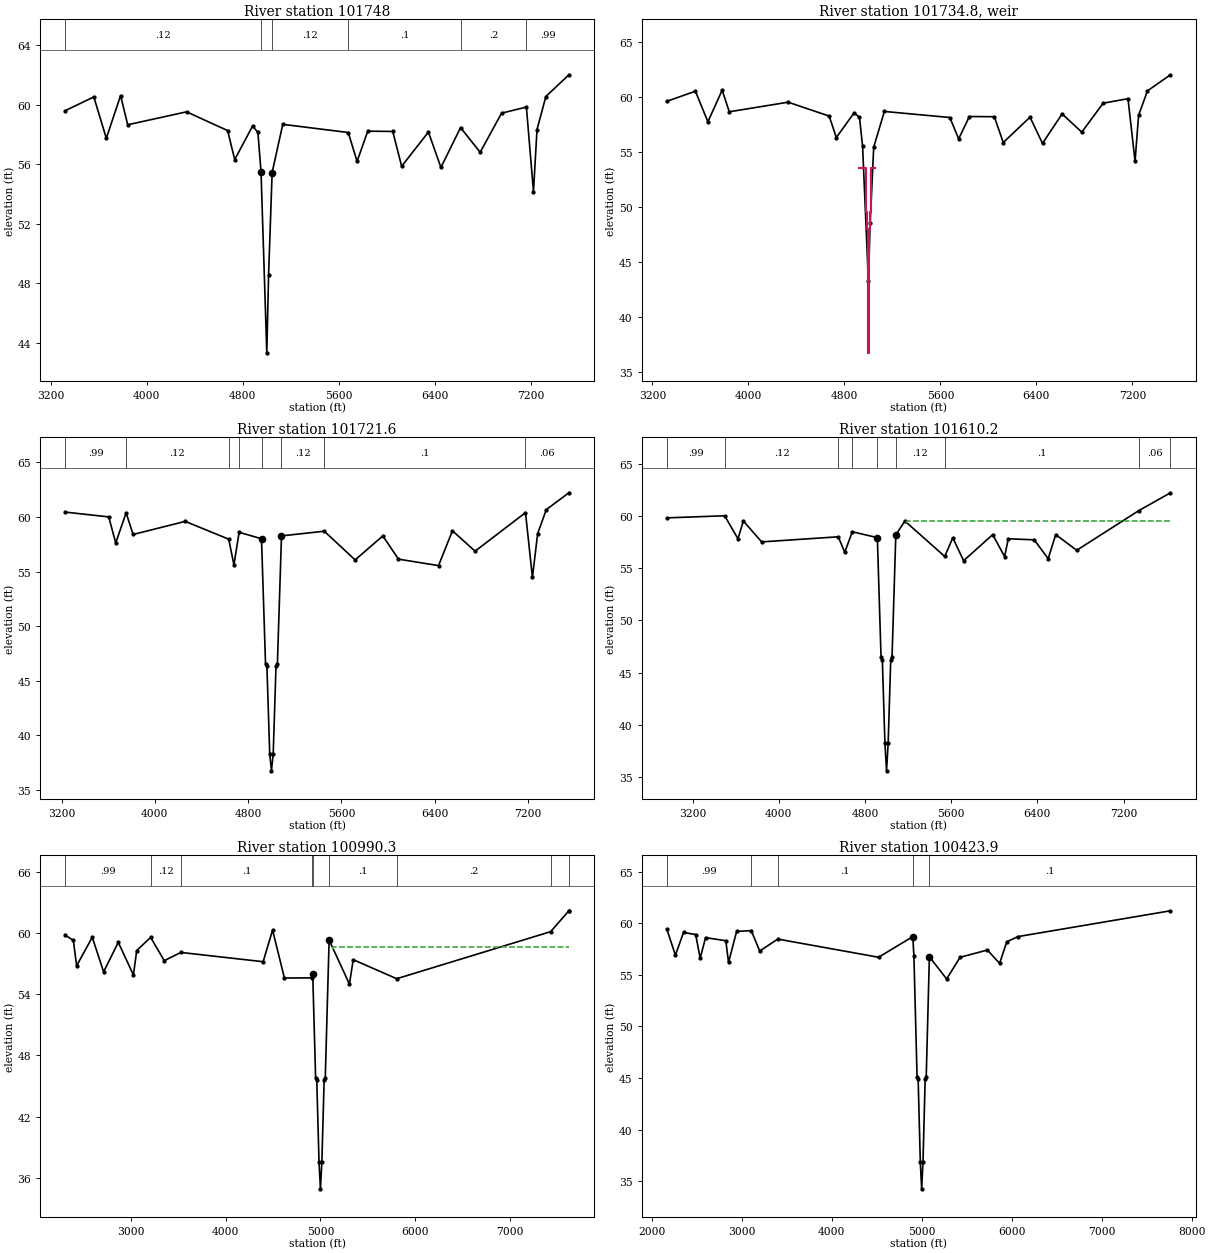
Type RM Length L Ch R = 1 ,101748  ,26.35,26.38,26.41
XS GIS Cut Line= 6
 3087865.9309082  13793420.06427 3087422.353698713791908.6220703
 3087341.148925813791734.0316772 3086924.889099113791180.1196899
 3086469.662719713790065.4996948 3086184.468505913789617.4697266
#Sta/Elev= 30
 3321.13   59.59 3558.89   60.51 3662.92   57.73  3781.8    60.6 3841.24   58.64
 4331.63   59.51 4673.41   58.25 4732.86    56.3 4881.46   58.55 4925.94   58.13
 4951.91   55.49    5000   43.31 5014.81   48.52 5044.43   55.43  5133.1   58.67
 5678.56   58.12 5752.27   56.18 5841.21   58.21 6049.31   58.19 6123.63   55.85
 6346.59   58.15 6450.64   55.77 6614.15   58.45 6777.65   56.79 6956.02   59.42
 7162.79   59.83  7221.8   54.15  7251.3   58.32 7325.07   60.54 7516.85      62
#Mann= 6 ,-1 , 0
 3321.13     .12       0 4951.91    .035       0 5044.43     .12       0
 5678.56      .1       0 6614.15      .2       0 7162.79     .99       0
Bank Sta=4951.91,5044.43
XS Rating Curve= 0 ,0
Exp/Cntr=0.3,0.1

Type RM Length L Ch R = 5 ,101734.8,,,
BEGIN DESCRIPTION:
Drop Strucuture
END DESCRIPTION:
IW Pilot Flow=0
#Inline Weir SE= 15
    4925    53.5    4976    53.5    4976    49.5  4990.5    49.5  4990.5      48
    4997      48    4997   36.75    5000   36.75    5003   36.75    5003      48
  5009.5      48  5009.5    49.5    5024    49.5    5024    53.5    5059    53.5
IW Dist,WD,Coef,Skew,MaxSub,Min_El,Is_Ogee,SpillHt,DesHd
13.1,0.1,3.3,0,0.98,, 0 ,,,0,0,

Type RM Length L Ch R = 1 ,101721.6,119.17,111.41,101.82
XS GIS Cut Line= 6
 3087942.367675813793482.4713135 3087448.559326213791902.5856934
 3087365.148925813791722.9324951 3086937.403503413791124.0889282
  3086488.27087413790033.3380737 3086176.944091813789578.9337158
#Sta/Elev= 30
 3231.56   60.45 3604.37   60.01 3664.02   57.63 3753.49   60.38 3813.14    58.4
 4260.51    59.6 4633.31   57.97 4678.05   55.62 4722.78    58.6 4914.69   58.01
    4949   46.57    4961   46.33    4985   38.33    5000   36.75    5015   38.33
    5039   46.33    5051   46.57  5086.1   58.27 5452.85    58.7 5717.78   56.07
  5955.2   58.27 6089.58   56.14 6433.01   55.55 6552.46   58.74 6746.57   56.87
 7179.05    60.4  7238.6   54.46 7283.27   58.49  7357.7   60.68 7551.23   62.22
#Mann= 8 ,-1 , 0
 3231.56     .99       0 3753.49     .12       0 4633.31      .1       0
 4722.78     .12       0 4914.69    .045       0  5086.1     .12       0
 5452.85      .1       0 7179.05     .06       0
Bank Sta=4914.69,5086.1
XS Rating Curve= 0 ,0
Exp/Cntr=0.3,0.1

Type RM Length L Ch R = 1 ,101610.2,653.73,619.92,610.16
BEGIN DESCRIPTION:
Cross Section 103703.0-Interpolated
USACE Sims Bayou Rectification
Reach 8b Croquet to South Post Oak
File No. HSC 409-37
END DESCRIPTION:
XS GIS Cut Line= 6
      3088255.91      13793676.1      3087827.44     13792268.47
      3087530.47     13791796.03      3087112.02      13791215.6
       3086477.6     13789933.25      3086167.14      13789541.8
#Sta/Elev= 30
  2960.7    59.8  3497.2      60  3620.7    57.8  3670.7    59.5  3840.7    57.5
  4551.7   57.99  4612.1    56.5    4682   58.47 4914.69   57.91    4949   46.47
    4961   46.23    4985   38.23    5000    35.6    5015   38.23    5039   46.23
    5051   46.47  5086.1   58.17  5170.1    59.5  5540.5   56.11  5615.1    57.9
  5715.7    55.7  5985.7    58.2  6095.7    56.1  6130.7    57.8  6370.7    57.7
  6500.7    55.9  6570.7    58.2  6765.7    56.7  7343.3    60.5    7636    62.2
#Mann= 9 ,-1 , 0
  2960.7     .99       0  3497.2     .12       0  4551.7      .1       0
    4682     .12       0 4914.69    .045       0  5086.1     .12       0
  5540.5      .1       0  7343.3     .06       0    7636      .2       0
#XS Ineff= 2 , 0
       0                    5190       0    59.5
Permanent Ineff=
       F       F
Bank Sta=4914.69,5086.1
XS Rating Curve= 0 ,0
Exp/Cntr=0.3,0.1

Type RM Length L Ch R = 1 ,100990.3,527.81,566.38,584.34
BEGIN DESCRIPTION:
Cross Section  103084.9
USACE Sims Bayou Rectification
Reach 8b Croquet to South Post Oak
File No. HSC 409-37
END DESCRIPTION:
XS GIS Cut Line= 6
      3089086.38     13793734.23      3088971.44      13792745.3
      3088425.24     13791682.59        3087990.     13791394.57
      3086530.66     13789743.21      3086204.23     13789503.19
#Sta/Elev= 30
  2303.9    59.8  2388.9    59.3  2423.9    56.8  2588.9    59.6  2708.9    56.2
  2863.9    59.1  3023.9    55.9  3058.9    58.3  3206.1   59.59  3349.5    57.3
  3524.7   58.11  4394.5    57.2  4494.3    60.3  4619.3    55.6  4913.3   55.61
 4918.38   55.99    4949   45.78    4961   45.54    4985   37.54    5000    34.9
    5015   37.54    5039   45.54    5051   45.78 5091.67   59.33  5306.3      55
  5346.3    57.4  5806.1   55.53  7432.4   60.15  7625.1    62.2  7625.2    62.2
#Mann= 9 ,-1 , 0
  2303.9     .99       0  3206.1     .12       0  3524.7      .1       0
  4913.3     .12       0 4918.38    .035       0 5091.67      .1       0
  5806.1      .2       0  7432.4     .99       0  7625.1      .2       0
#XS Ineff= 2 , 0
       0                  5137.5       0    58.6
Permanent Ineff=
       F       F
Bank Sta=4918.38,5091.67
XS Rating Curve= 0 ,0
Exp/Cntr=0.3,0.1

Type RM Length L Ch R = 1 ,100423.9,158.86,176.52,197.76
BEGIN DESCRIPTION:
Cross Section 102517.0 - Interpolated
USACE Sims Bayou Rectification
Reach 8b Croquet to South Post Oak
File No. HSC 409-37
END DESCRIPTION:
XS GIS Cut Line= 6
      3089177.73     13793709.32      3089031.48     13792703.25
      3088446.57     13791073.14       3088206.9      13790615.1
      3087855.38     13790087.82      3086497.24     13789075.87
#Sta/Elev= 30
  2169.2    59.4  2264.2    56.9  2354.2    59.1  2489.2    58.9  2539.2    56.6
  2599.2    58.6  2824.2    58.3  2854.2    56.2  2944.2    59.2  3106.7   59.28
  3200.8    57.3  3401.2   58.46  4521.6    56.7  4901.6    58.7    4914   56.82
    4949   45.15    4961   44.91    4985   36.91    5000   34.28    5015   36.91
    5039   44.91    5051   45.15 5085.78   56.75  5277.4    54.6  5427.4    56.7
  5731.1    57.4  5866.1    56.1  5946.1    58.2  6069.8    58.7  7764.6    61.2
#Mann= 5 ,-1 , 0
  2169.2     .99       0  3106.7     .12       0  3401.2      .1       0
  4901.6    .035       0 5085.78      .1       0
Bank Sta=4901.6,5085.78
XS Rating Curve= 0 ,0
Exp/Cntr=0.5,0.3