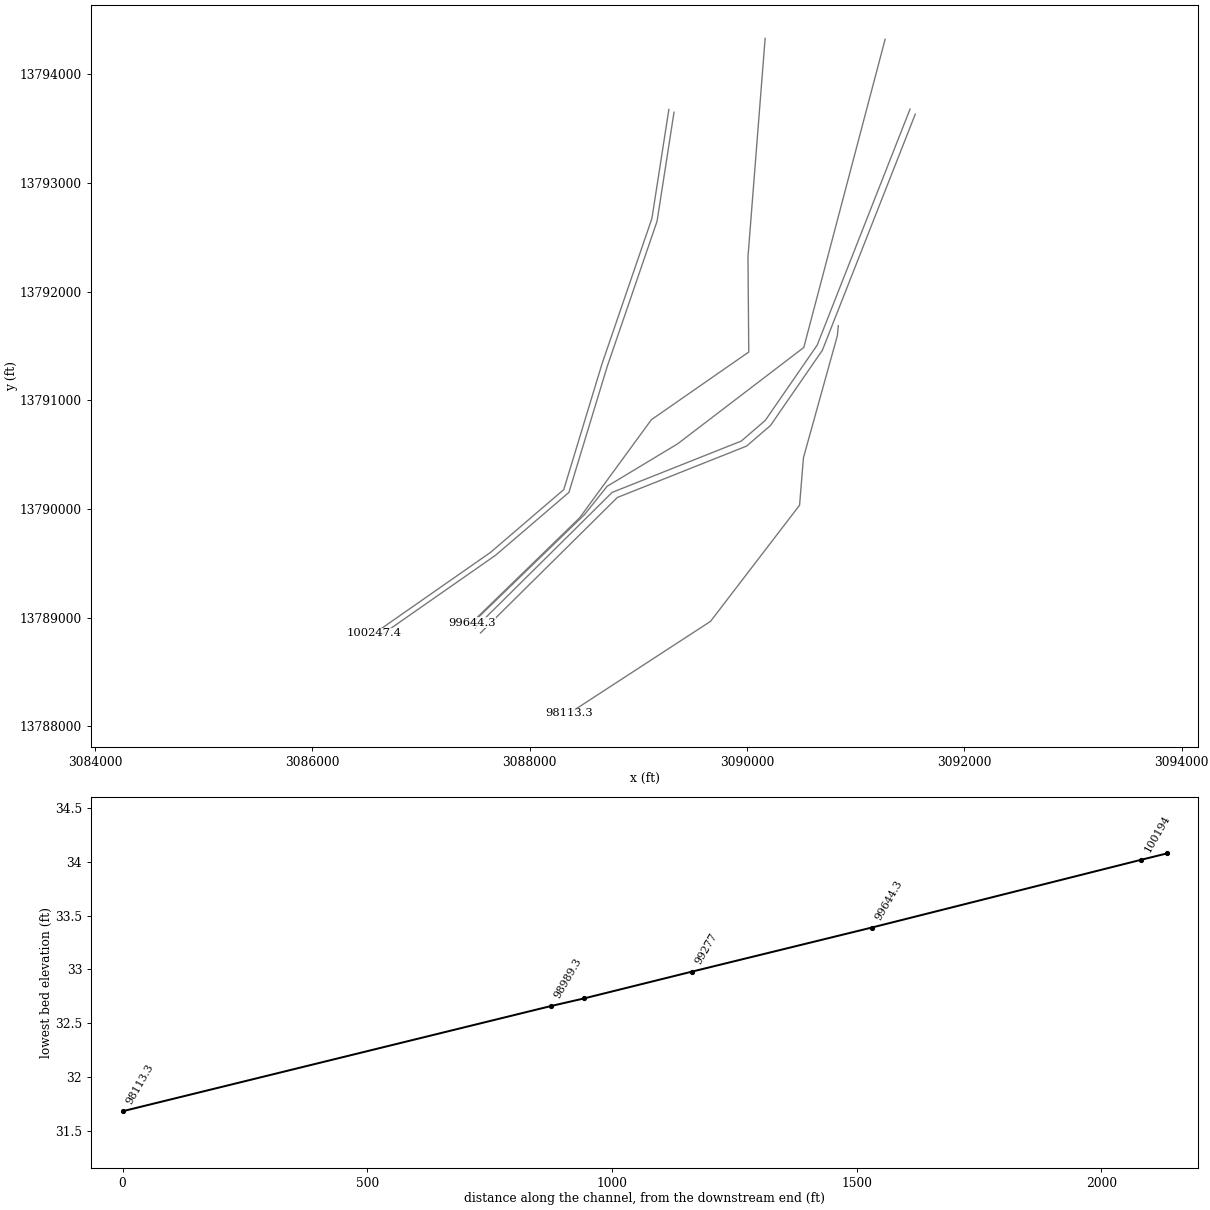
HEC-RAS study C100-00-00.prj: C100-00-00

--- C100-00-00.g01 (geometry) --- (continued)

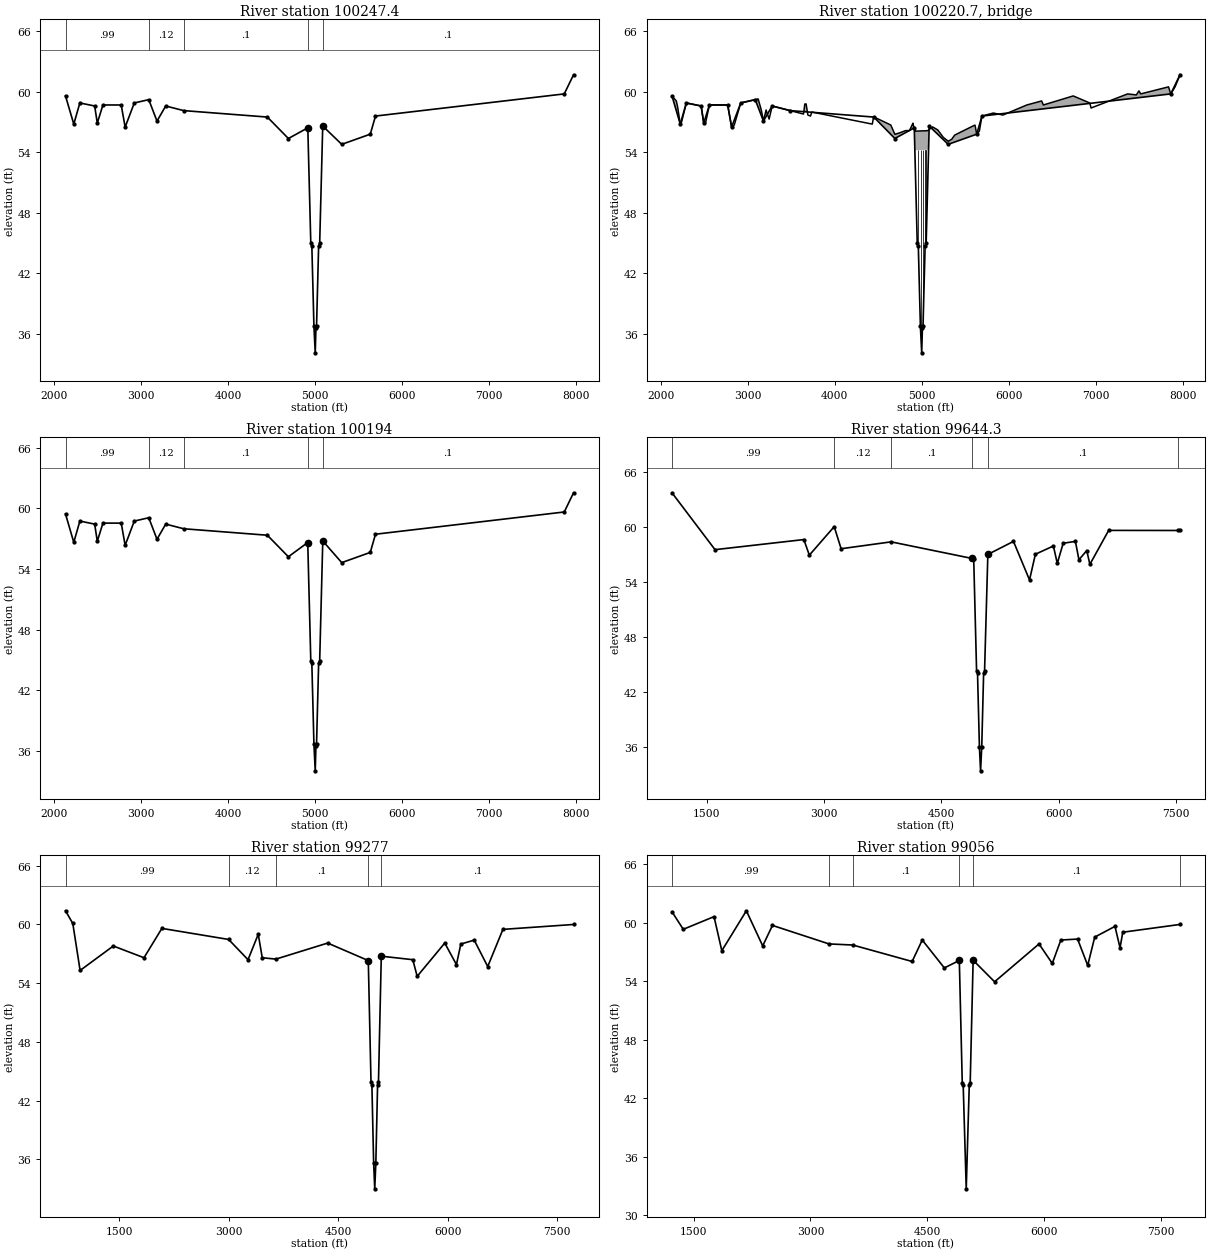
Type RM Length L Ch R = 1 ,100247.4,53.56,53.43,53.35
BEGIN DESCRIPTION:
Upstream Section of Bridge/Culvert/Weir
USACE Sims Bayou Rectification
Reach 8b Croquet to South Post Oak
File No. HSC 409-37
END DESCRIPTION:
XS GIS Cut Line= 6
      3089280.03     13793678.13      3089124.03     13792674.72
       3088664.2     13791334.75      3088312.69      13790178.8
       3087638.2     13789600.66      3086569.47     13788855.03
#Sta/Elev= 30
  2131.5    59.6  2226.5    56.8  2296.5    58.9  2466.5    58.6  2496.5    56.9
  2561.5    58.7  2771.5    58.7  2816.5    56.5  2921.5    58.9  3087.7   59.23
  3182.4    57.1  3282.4    58.6  3489.7   58.14  4449.9    57.5  4691.6   55.37
 4914.58   56.43    4949   44.95    4961   44.71    4985   36.71    5000   34.08
 5008.11   36.58    5015   36.71    5039   44.71    5051   44.95 5085.98   56.61
  5304.3   54.79  5632.1    55.8  5692.1    57.6  7860.3    59.8    7967    61.7
#Mann= 5 ,-1 , 0
  2131.5     .99       0  3087.7     .12       0  3489.7      .1       0
 4914.58    .035       0 5085.98      .1       0
#XS Ineff= 2 , 0
       0 4914.58   55.79 5085.98       0    56.3
Permanent Ineff=
       F       F
Bank Sta=4914.58,5085.98
XS Rating Curve= 0 ,0
Exp/Cntr=0.5,0.3

Type RM Length L Ch R = 3 ,100220.7,,,
BEGIN DESCRIPTION:
CROOKED WOOD LANE croquet lane
Structure ID: C00-45
END DESCRIPTION:
Bridge Culvert--1,0,-1,-1, 0
Deck Dist Width WeirC Skew NumUp NumDn MinLoCord MaxHiCord MaxSubmerge Is_Ogee
10,34,2.6,0, 103, 103, , , 0.95, 0, 1,1,,
  2131.5  2181.5  2196.5  2226.5  2241.5  2296.5  2466.5  2496.5  2516.5  2561.5
  2771.5  2816.5  2846.5  2921.5  3087.7  3121.5  3157.4  3182.4  3212.4  3247.4
  3282.4  3489.7  3642.4  3657.4  3672.4  3692.4  3722.4  3737.4  4432.4  4447.4
  4449.9  4499.5  4644.9  4691.6  4750.7  4752.1  4809.8  4813.2  4859.7  4859.9
  4899.4  4900.5  4926.1 4926.21  4926.3 4926.69  4926.8 4926.91  4927.5  4954.2
  4960.1  4977.8  4977.9  4987.8  4989.2  4995.7  5003.6  5009.6  5010.8  5012.5
  5012.6  5016.3  5020.4  5043.9 5064.29  5064.4 5064.51 5064.59  5064.7  5064.8
  5070.4  5124.1    5125  5182.9  5183.7  5244.9  5248.2  5304.3  5304.9  5344.2
  5378.8  5432.5  5590.7  5612.1  5632.1  5662.1  5692.1  5822.5  5932.5  6207.5
  6377.5  6397.5  6740.3  6930.3  6945.3  7365.3  7465.3  7495.3  7515.3  7835.3
  7860.3  7910.3    7967
    59.6    59.1    58.5    56.8      57    58.9    58.6    56.9    56.9    58.7
    58.7    56.5    56.7    58.9   59.23    59.3    58.2    57.1    58.2    57.3
    58.6   58.14    57.8    58.8    58.8    57.7    57.6      58    56.8    57.5
    57.5   57.31   56.71   55.79   55.94   55.95   56.14   56.15   56.16   56.16
   56.89   56.79    56.1    56.1    56.1    56.1    56.1    56.1    56.1   56.11
   56.11   56.12   56.12   56.12   56.12   56.13   56.13   56.13   56.13   56.13
   56.13   56.13   56.13   56.14   56.15   56.15   56.15   56.15   56.15   56.15
   56.15   56.52   56.52   56.23   56.23   55.52   55.48    55.1    55.1   55.29
   55.71   55.94   56.62    56.7    55.8    56.1    57.6    57.9    57.7    58.7
    59.1    58.7    59.6    58.9    58.4    59.8    59.7    60.1    59.8    60.5
    59.8    60.5    61.7
                                                                                
                                                                                
                                                                                
                                                                                
           54.21   54.21   54.21   54.21   54.21   54.21   54.21   54.21   54.21
   54.21   54.22   54.22   54.22   54.22   54.23   54.23   54.23   54.23   54.23
   54.23   54.23   54.23   54.24   54.25   54.25   54.25   54.25   54.25   54.25
   54.25   54.25
                                                                                
                                                                                
                        
  2131.5  2181.5  2196.5  2226.5  2241.5  2296.5  2466.5  2496.5  2516.5  2561.5
  2771.5  2816.5  2846.5  2921.5  3087.7  3121.5  3157.4  3182.4  3212.4  3247.4
  3282.4  3489.7  3642.4  3657.4  3672.4  3692.4  3722.4  3737.4  4432.4  4447.4
  4449.9  4499.5  4644.9  4691.6  4750.7  4752.1  4809.8  4813.2  4859.7  4859.9
  4899.4  4900.5  4926.1 4926.21  4926.3 4926.69  4926.8 4926.91  4927.5  4954.2
  4960.1  4977.8  4977.9  4987.8  4989.2  4995.7  5003.6  5009.6  5010.8  5012.5
  5012.6  5016.3  5020.4  5043.9 5064.29  5064.4 5064.51 5064.59  5064.7  5064.8
  5070.4  5124.1    5125  5182.9  5183.7  5244.9  5248.2  5304.3  5304.9  5344.2
  5378.8  5432.5  5590.7  5612.1  5632.1  5662.1  5692.1  5822.5  5932.5  6207.5
  6377.5  6397.5  6740.3  6930.3  6945.3  7365.3  7465.3  7495.3  7515.3  7835.3
  7860.3  7910.3    7967
    59.6    59.1    58.5    56.8      57    58.9    58.6    56.9    56.9    58.7
    58.7    56.5    56.7    58.9   59.23    59.3    58.2    57.1    58.2    57.3
    58.6   58.14    57.8    58.8    58.8    57.7    57.6      58    56.8    57.5
    57.5   57.31   56.71   55.79   55.94   55.95   56.14   56.15   56.16   56.16
   56.89   56.79    56.1    56.1    56.1    56.1    56.1    56.1    56.1   56.11
   56.11   56.12   56.12   56.12   56.12   56.13   56.13   56.13   56.13   56.13
   56.13   56.13   56.13   56.14   56.15   56.15   56.15   56.15   56.15   56.15
   56.15   56.52   56.52   56.23   56.23   55.52   55.48    55.1    55.1   55.29
   55.71   55.94   56.62    56.7    55.8    56.1    57.6    57.9    57.7    58.7
    59.1    58.7    59.6    58.9    58.4    59.8    59.7    60.1    59.8    60.5
    59.8    60.5    61.7
                                                                                
                                                                                
                                                                                
                                                                                
           54.21   54.21   54.21   54.21   54.21   54.21   54.21   54.21   54.21
   54.21   54.22   54.22   54.22   54.22   54.23   54.23   54.23   54.23   54.23
   54.23   54.23   54.23   54.24   54.25   54.25   54.25   54.25   54.25   54.25
   54.25   54.25
                                                                                
                                                                                
                        
Pier Skew, UpSta & Num, DnSta & Num=  ,4960.1, 2 ,4960.1, 2 , 0 , 0 , 0 ,,
       1       1
    48.2   55.21
       1       1
   48.03   55.04
Pier Skew, UpSta & Num, DnSta & Num=  ,4987.8, 2 ,4987.8, 2 , 0 , 0 , 0 ,,
       1       1
   44.23   55.22
       1       1
   44.06   55.05
Pier Skew, UpSta & Num, DnSta & Num=  ,5016.3, 2 ,5016.3, 2 , 0 , 0 , 0 ,,
       1       1
   42.76   55.23
       1       1
   42.59   55.06
Pier Skew, UpSta & Num, DnSta & Num=  ,5043.9, 2 ,5043.9, 2 , 0 , 0 , 0 ,,
       1       1
   49.97   55.24
       1       1
    49.8   55.07
BR Coef= 1 , 1 , 0 ,1.25, 0 ,,,0.8,0,2,0,
WSPro=,,,, 1 ,,,, 0 ,,,, 0 ,,,,-1 ,-1 ,-1 , 0 , 0 , 0 , 0 , 0
BC Design=,, 0 ,, 0 ,,,,,,
BC HTab HWMax=61.7
BC Use User HTab Curves=0
BC User HTab FreeFlow(D)= 0

Type RM Length L Ch R = 1 ,100194  ,611.73,549.69,508.17
BEGIN DESCRIPTION:
Downstream Section of Bridge/Culvert/Weir
USACE Sims Bayou Rectification
Reach 8b Croquet to South Post Oak
File No. HSC 409-37
END DESCRIPTION:
XS GIS Cut Line= 6
      3089327.47     13793652.34      3089171.47     13792648.92
      3088711.64     13791308.95      3088360.13       13790153.
      3087685.64     13789574.86      3086616.91     13788829.23
#Sta/Elev= 30
  2131.5   59.43  2226.5   56.63  2296.5   58.73  2466.5   58.43  2496.5   56.73
  2561.5   58.53  2771.5   58.53  2816.5   56.33  2921.5   58.73  3087.7   59.06
  3182.4   56.93  3282.4   58.43  3489.7   57.97  4449.9   57.33  4691.6    55.2
 4913.85   56.61    4949   44.89    4961   44.65    4985   36.65    5000   34.02
 5008.11   36.52    5015   36.65    5039   44.65    5051   44.89 5086.59   56.76
  5304.3   54.62  5632.1   55.63  5692.1   57.43  7860.3   59.63    7967   61.53
#Mann= 5 ,-1 , 0
  2131.5     .99       0  3087.7     .12       0  3489.7      .1       0
 4913.85    .035       0 5086.59      .1       0
#XS Ineff= 2 , 0
       0 4913.85   55.79 5086.59       0    56.3
Permanent Ineff=
       F       F
Bank Sta=4913.85,5086.59
XS Rating Curve= 0 ,0
Exp/Cntr=0.5,0.3

Type RM Length L Ch R = 1 ,99644.3 ,361.25,367.24,358.78
BEGIN DESCRIPTION:
Cross Section 101740.3
USACE Sims Bayou Rectification
Reach 8b Croquet to South Post Oak
File No. HSC 409-37
END DESCRIPTION:
XS GIS Cut Line= 6
      3090165.98     13794332.17       3090008.2     13792322.44
      3090015.29     13791445.08      3089118.86     13790821.79
      3088460.15     13789920.66      3087466.18     13788954.32
#Sta/Elev= 30
  1057.2    63.7  1607.2    57.5  2742.2    58.6  2812.2    56.9  3130.1   60.01
  3218.1    57.6  3857.1   58.35 4892.21   56.54 4912.46   56.45    4949   44.27
    4961   44.03    4985   36.03    5000   33.39    5015   36.03    5039   44.03
    5051   44.27 5093.01   56.98  5420.3    58.4  5625.3    54.2  5700.3      57
  5930.3    57.9  5980.3      56  6055.3    58.2  6211.6    58.4  6256.6    56.4
  6356.6    57.4  6396.6    55.9  6636.6    59.6  7528.2   59.59  7548.1    59.6
#Mann= 6 ,-1 , 0
  1057.2     .99       0  3130.1     .12       0  3857.1      .1       0
 4892.21    .035       0 5093.01      .1       0  7528.2      .2       0
Bank Sta=4892.21,5093.01
XS Rating Curve= 0 ,0
Exp/Cntr=0.3,0.1

Type RM Length L Ch R = 1 ,99277   ,251.23,221.08,197.58
BEGIN DESCRIPTION:
Cross Section 101357.0 - Interpolated
USACE Sims Bayou Rectification
Reach 8b Croquet to South Post Oak
File No. HSC 409-37
END DESCRIPTION:
XS GIS Cut Line= 6
       3091270.5     13794323.86      3090521.76     13791486.89
      3089360.32     13790599.79      3088711.21     13790208.66
      3088503.02     13789948.28      3087446.34     13788925.68
#Sta/Elev= 30
   764.4    61.4   864.4    60.1   964.4    55.3  1419.4    57.8  1839.4    56.6
  2084.4    59.6  2998.6   58.47  3264.4    56.4  3404.4      59  3459.4    56.6
  3646.2   56.46  4355.3    58.1 4911.64   56.31    4949   43.86    4961   43.62
    4985   35.62    5000   32.98    5015   35.62    5039   43.62    5051   43.86
 5089.69   56.76  5521.3    56.4  5581.3    54.7  5959.1    58.1  6119.1    55.9
  6179.1      58  6362.5    58.4  6547.5    55.7  6755.7    59.5  7723.1      60
#Mann= 5 ,-1 , 0
   764.4     .99       0  2998.6     .12       0  3646.2      .1       0
 4911.64    .035       0 5089.69      .1       0
Bank Sta=4911.64,5089.69
XS Rating Curve= 0 ,0
Exp/Cntr=0.5,0.3

Type RM Length L Ch R = 1 ,99056   ,68.21,66.69,66.34
BEGIN DESCRIPTION:
Upstream Section of Bridge/Culvert/Weir
USACE Sims Bayou Rectification
Reach 8b Croquet to South Post Oak
File No. HSC 409-37
END DESCRIPTION:
XS GIS Cut Line= 6
      3091499.85     13793681.18      3090644.92     13791508.21
       3090167.2     13790815.52       3089947.1     13790625.74
        3088758.     13790153.07      3087498.41     13788906.09
#Sta/Elev= 30
  1222.3   61.14  1367.3   59.34  1762.3   60.64  1862.3   57.14  2177.3   61.24
  2387.3   57.64  2512.3   59.74    3239   57.84    3543   57.73  4305.4   56.04
  4435.4   58.24  4719.2   55.38 4911.37   56.15    4949   43.61    4961   43.37
    5000   32.73    5039   43.37    5051   43.61 5088.69   56.17  5364.1   53.96
  5934.6   57.84  6104.6   55.84  6214.6   58.24  6429.6   58.34  6559.6   55.64
  6649.6   58.54  6909.6   59.64  6974.6   57.44  7009.6   59.04  7744.6   59.84
#Mann= 6 ,-1 , 0
  1222.3     .99       0    3239     .12       0    3543      .1       0
 4911.37    .035       0 5088.69      .1       0  7744.6      .2       0
#XS Ineff= 2 , 0
       0 4911.37    55.8 5088.69       0   55.46
Permanent Ineff=
       F       F
Bank Sta=4911.37,5088.69
XS Rating Curve= 0 ,0
Exp/Cntr=0.5,0.3

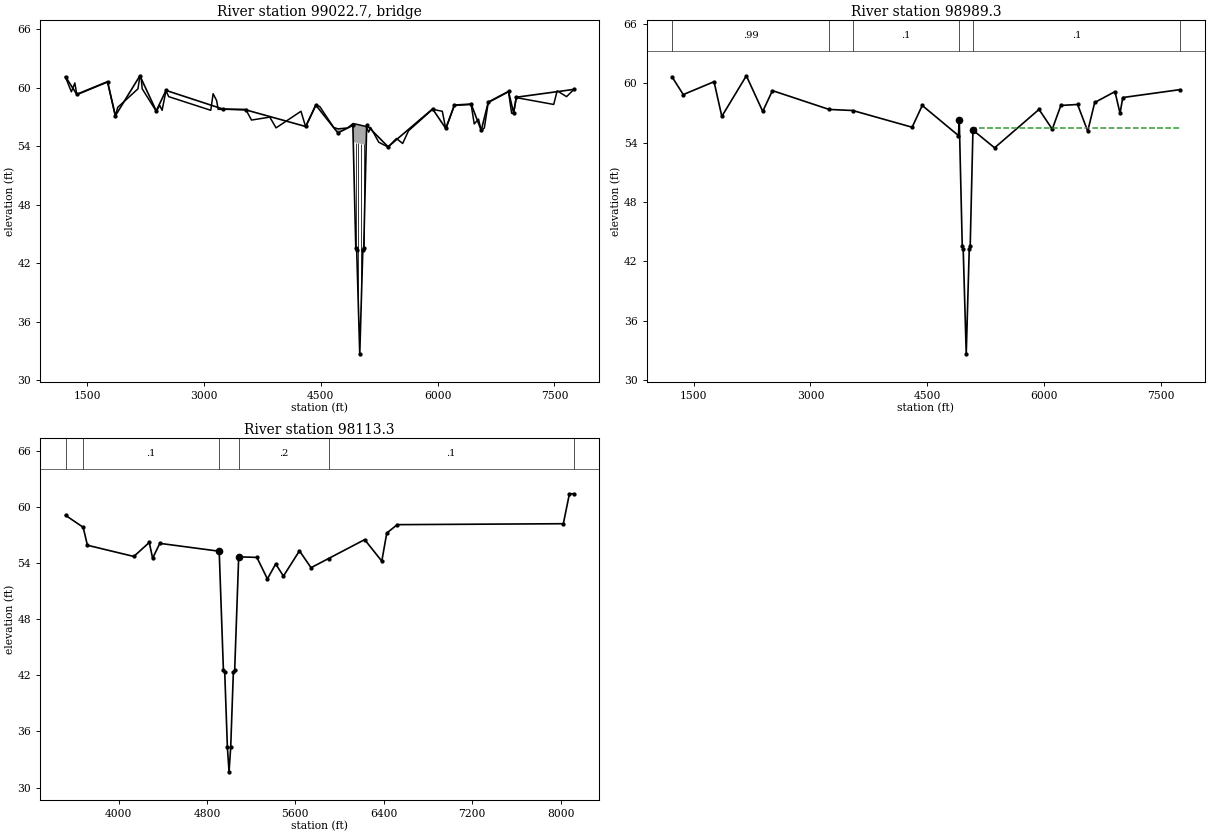
Type RM Length L Ch R = 3 ,99022.7 ,,,
BEGIN DESCRIPTION:
HEATHER BROOK DRIVE
Structure ID: C00-43
END DESCRIPTION:
Bridge Culvert--1,0,-1,-1, 0
Deck Dist Width WeirC Skew NumUp NumDn MinLoCord MaxHiCord MaxSubmerge Is_Ogee
10,47,2.6,0, 60, 60, , , 0.95, 0, 1,1,,
  1222.3  1297.3  1342.3  1367.3  1762.3  1862.3  1892.3  2152.3  2177.3  2192.3
  2207.3  2387.3  2432.3  2462.3  2512.3  2547.3  3087.3  3117.3  3162.3  3182.3
  3535.4  3610.4  3845.4  3925.4  4245.4  4305.4  4435.4  4485.3    4665  4719.2
  4842.5  4915.3 4919.49 5081.79  5081.9  5114.5  5139.2  5243.6  5364.1  5470.7
  5550.7  5625.7  5934.6  6059.6  6104.6  6214.6  6429.6  6469.6  6524.6  6559.6
  6599.6  6649.6  6909.6  6949.6  6974.6  7009.6  7489.6  7534.6  7654.6  7744.6
    61.1    59.6    60.5    59.3    60.6    57.1      58    59.9    61.2    61.1
    59.9    57.6    58.2    57.7    59.7    59.1    57.7    59.4    58.7    57.8
    57.8    56.7      57    55.9    57.6      56    58.2    58.1   55.95    55.8
   55.89   56.35   56.34   56.04   56.04   55.46   55.94   54.43   53.93   54.81
    54.3    55.6    57.8    57.6    55.8    58.2    58.3    56.3    56.8    55.6
    55.9    58.5    59.6    57.4    57.4      59    58.3    59.7    59.1    59.8
    61.1    59.6    60.5    59.3    60.6    57.1      58    59.9    61.2    61.1
    59.9    57.6    58.2    57.7    59.7    59.1    57.7    59.4    58.7    57.8
    57.8    56.7      57    55.9    57.6      56    58.2    58.1   55.94   55.34
   55.83   54.98   54.44   54.14   50.51   55.45   55.93   54.42   53.92    54.8
    54.3    55.6    57.8    57.6    55.8    58.2    58.3    56.3    56.8    55.6
    55.9    58.5    59.6    57.4    57.4      59    58.3    59.7    59.1    59.8
  1222.3  1297.3  1342.3  1367.3  1762.3  1862.3  1892.3  2152.3  2177.3  2192.3
  2207.3  2387.3  2432.3  2462.3  2512.3  2547.3  3087.3  3117.3  3162.3  3182.3
  3535.4  3610.4  3845.4  3925.4  4245.4  4305.4  4435.4  4485.3    4665  4719.2
  4842.5  4915.3 4919.49 5081.79  5081.9  5114.5  5139.2  5243.6  5364.1  5470.7
  5550.7  5625.7  5934.6  6059.6  6104.6  6214.6  6429.6  6469.6  6524.6  6559.6
  6599.6  6649.6  6909.6  6949.6  6974.6  7009.6  7489.6  7534.6  7654.6  7744.6
    61.1    59.6    60.5    59.3    60.6    57.1      58    59.9    61.2    61.1
    59.9    57.6    58.2    57.7    59.7    59.1    57.7    59.4    58.7    57.8
    57.8    56.7      57    55.9    57.6      56    58.2    58.1   55.95    55.8
   55.89   56.35   56.34   56.04   56.04   55.46   55.94   54.43   53.93   54.81
    54.3    55.6    57.8    57.6    55.8    58.2    58.3    56.3    56.8    55.6
    55.9    58.5    59.6    57.4    57.4      59    58.3    59.7    59.1    59.8
   60.69   59.19   60.09   58.89   60.19   56.69   57.59   59.49   60.79   60.69
   59.49   57.19   57.79   57.29   59.29   58.69   57.29   58.99   58.29   57.39
   57.39   56.29   56.59   55.49   57.19   55.59   57.79   57.69   55.53   54.93
   55.42   54.57   54.03   53.73    50.1   55.04   55.52   54.01   53.51   54.39
   53.89   55.19   57.39   57.19   55.39   57.79   57.89   55.89   56.39   55.19
   55.49   58.09   59.19   56.99   56.99   58.59   57.89   59.29   58.69   59.39
Pier Skew, UpSta & Num, DnSta & Num=  ,4949.1, 2 ,4949.1, 2 , 0 , 0 , 0 ,,
     1.4     1.4
   46.16   55.39
     1.4     1.4
   45.75   54.98
Pier Skew, UpSta & Num, DnSta & Num=  ,4982.1, 2 ,4982.1, 2 , 0 , 0 , 0 ,,
     1.4     1.4
   40.37   55.33
     1.4     1.4
   39.96   54.92
Pier Skew, UpSta & Num, DnSta & Num=  ,5016.7, 2 ,5016.7, 2 , 0 , 0 , 0 ,,
     1.4     1.4
   42.77   55.26
     1.4     1.4
   42.36   54.85
Pier Skew, UpSta & Num, DnSta & Num=  ,5049.9, 2 ,5049.9, 2 , 0 , 0 , 0 ,,
     1.4     1.4
   46.63    55.2
     1.4     1.4
   46.22   54.79
BR Coef= 1 , 1 , 0 ,1.25, 0 ,,,0.8,0,2,0,
WSPro=,,,, 1 ,,,, 0 ,,,, 0 ,,,,-1 ,-1 ,-1 , 0 , 0 , 0 , 0 , 0
BC Design=,, 0 ,, 0 ,,,,,,
BC HTab HWMax=61.24
BC Use User HTab Curves=0
BC User HTab FreeFlow(D)= 0

Type RM Length L Ch R = 1 ,98989.3 ,767.81,875.98,972.41
BEGIN DESCRIPTION:
Downstream Section of Bridge/Culvert/Weir
USACE Sims Bayou Rectification
Reach 8b Croquet to South Post Oak
File No. HSC 409-37
END DESCRIPTION:
XS GIS Cut Line= 6
      3091547.97     13793634.56      3090693.04     13791461.59
      3090215.32      13790768.9      3089995.22     13790579.12
      3088806.12     13790106.45      3087546.53     13788859.46
#Sta/Elev= 30
  1222.3   60.66  1367.3   58.86  1762.3   60.16  1862.3   56.66  2177.3   60.76
  2387.3   57.16  2512.3   59.26    3239   57.36    3543   57.25  4305.4   55.56
  4435.4   57.76  4899.7   54.72 4910.78   56.27    4949   43.53    4961   43.29
    5000   32.66    5039   43.29    5051   43.53 5086.21   55.27  5364.1   53.48
  5934.6   57.36  6104.6   55.36  6214.6   57.76  6429.6   57.86  6559.6   55.16
  6649.6   58.06  6909.6   59.16  6974.6   56.96  7009.6   58.56  7744.6   59.36
#Mann= 6 ,-1 , 0
  1222.3     .99       0    3239     .12       0    3543      .1       0
 4910.78    .035       0 5086.21      .1       0  7744.6      .2       0
#XS Ineff= 2 , 0
       0 4910.78      55 5086.21       0   55.46
Permanent Ineff=
       F       F
Bank Sta=4910.78,5086.21
XS Rating Curve= 0 ,0
Exp/Cntr=0.5,0.3

Type RM Length L Ch R = 1 ,98113.3 ,822.91,801.4,781.44
BEGIN DESCRIPTION:
Cross Section 100195.2
USACE Sims Bayou Rectification
Reach 8b Croquet to South Post Oak
File No. HSC 409-37
END DESCRIPTION:
XS GIS Cut Line= 6
       3090839.5     13791687.51      3090830.56     13791594.79
      3090518.64     13790471.92        3090483.     13790035.24
      3089663.12     13788965.83      3088362.01     13788119.22
#Sta/Elev= 30
  3520.4    59.1  3680.2   57.82  3718.5    55.9  4138.5    54.7  4278.5    56.2
  4308.5    54.5  4373.5    56.1  4910.9   55.26    4949   42.56    4961   42.32
    4985   34.32    5000   31.68    5015   34.32    5039   42.32    5051   42.56
 5087.28   54.66    5252    54.6    5347    52.3    5422    53.9    5492    52.6
    5637    55.3    5742    53.5  5900.4   54.48    6227    56.5    6382    54.2
    6427    57.2    6522    58.1  8024.6    58.2  8079.6    61.4  8116.9    61.4
#Mann= 6 ,-1 , 0
  3520.4     .12       0  3680.2      .1       0  4910.9    .035       0
 5087.28      .2       0  5900.4      .1       0  8116.9      .2       0
Bank Sta=4910.9,5087.28
XS Rating Curve= 0 ,0
Exp/Cntr=0.3,0.1