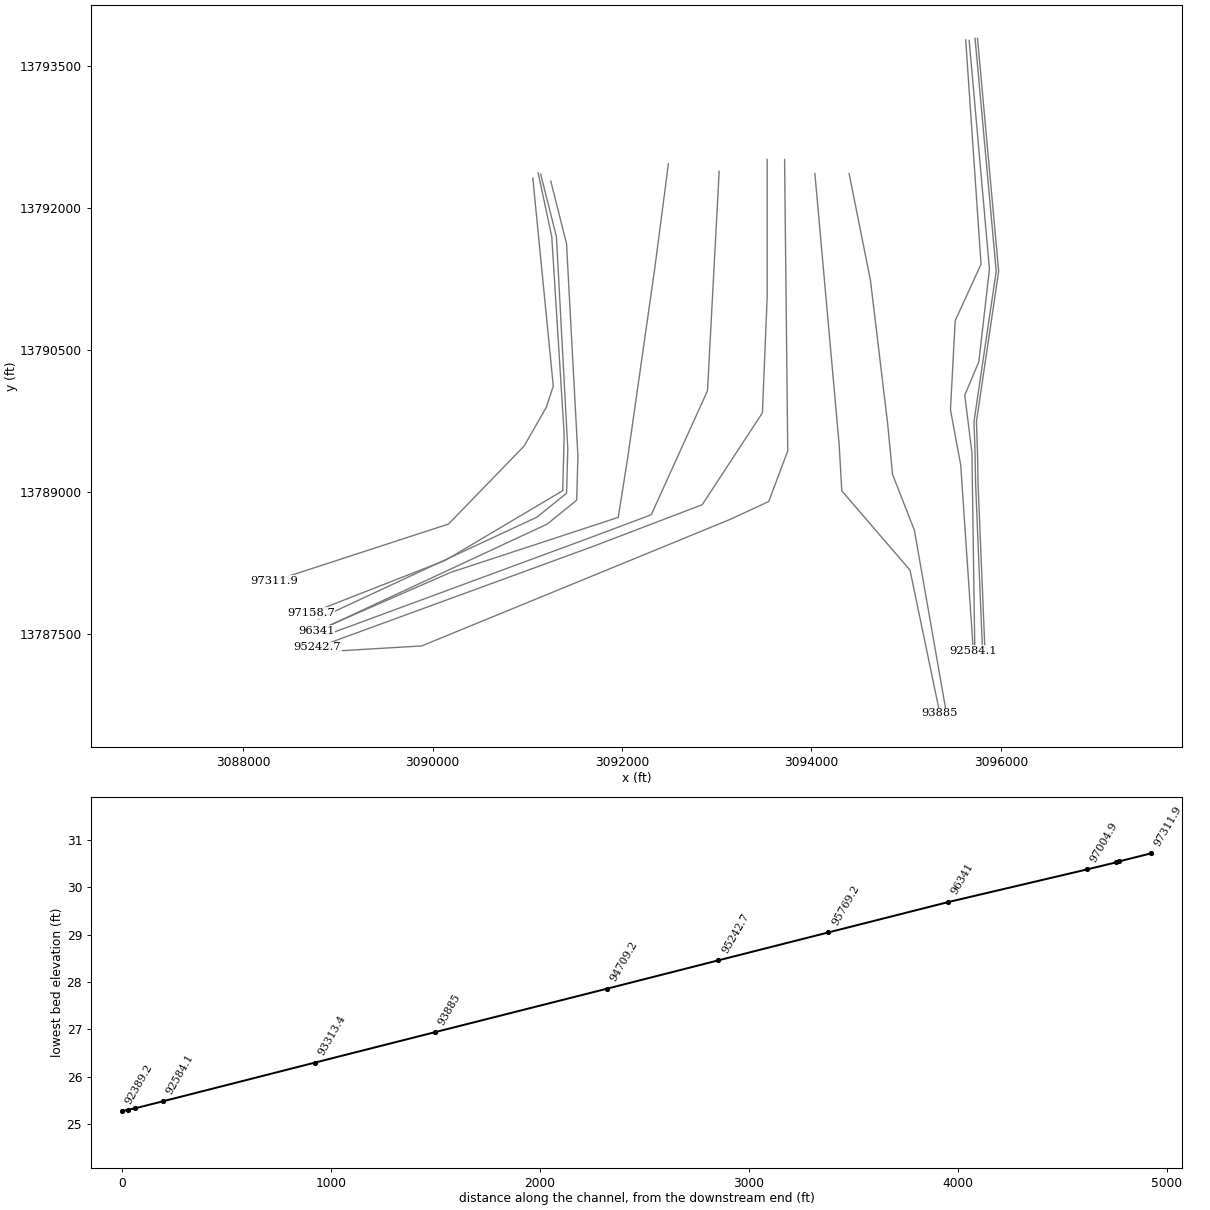
HEC-RAS study C100-00-00.prj: C100-00-00

--- C100-00-00.g01 (geometry) --- (continued)

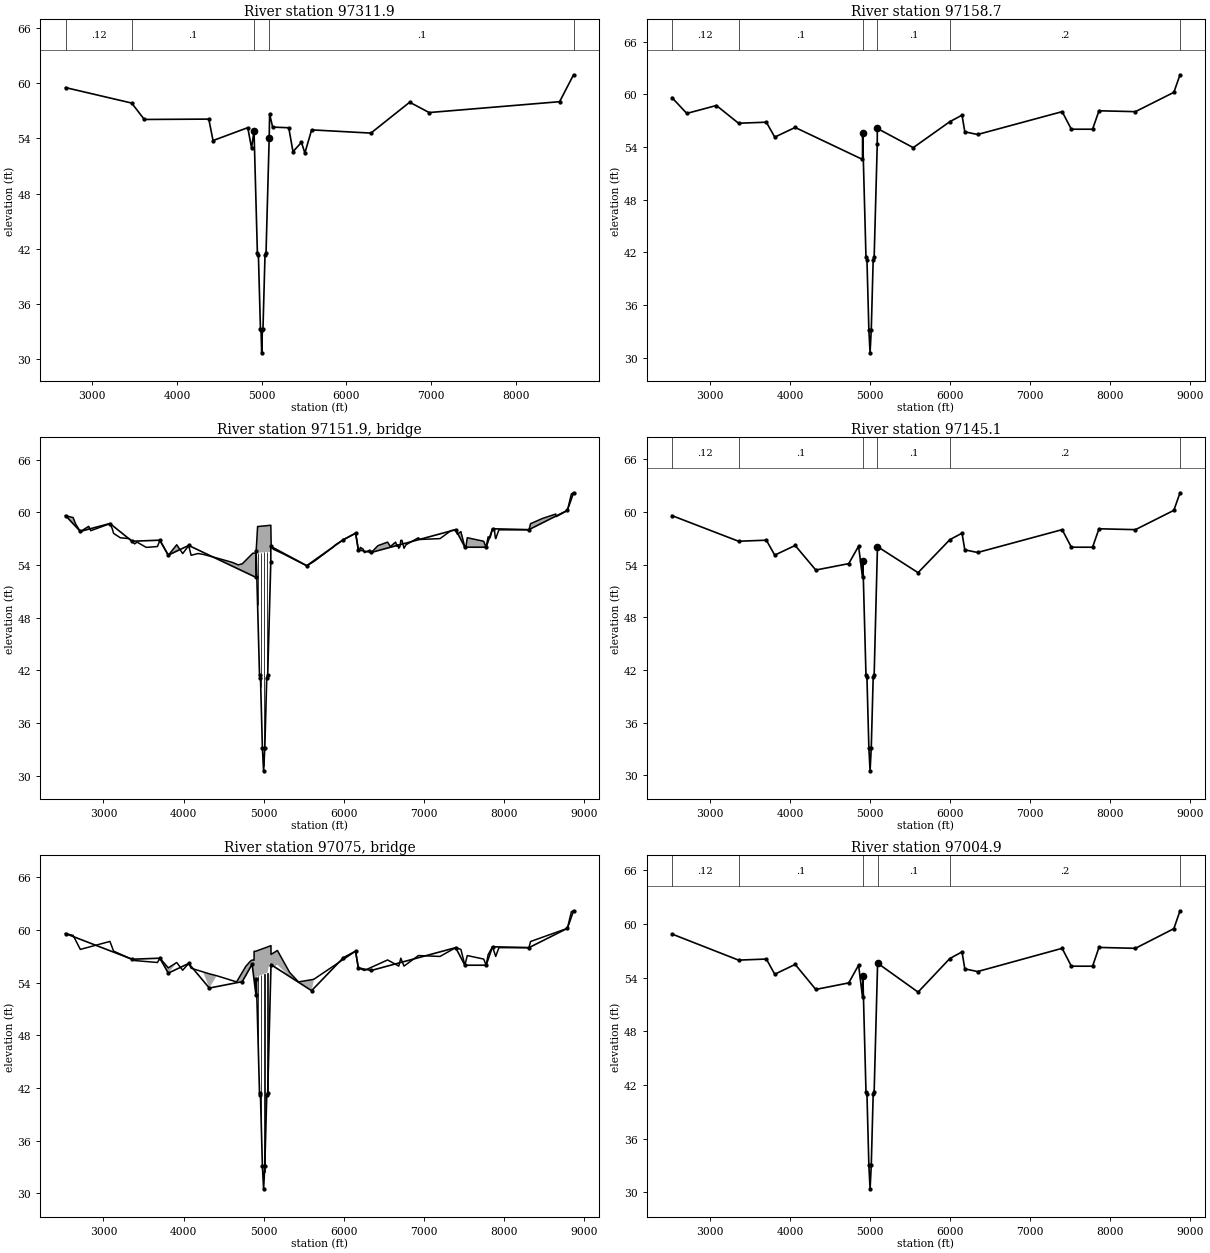
Type RM Length L Ch R = 1 ,97311.9 ,149.4,153.19,193.73
BEGIN DESCRIPTION:
Cross Section 99391.0 - Interpolated
USACE Sims Bayou Rectification
Reach 8b Croquet to South Post Oak
File No. HSC 409-37
END DESCRIPTION:
XS GIS Cut Line= 6
      3091057.99     13792314.11      3091274.37     13790117.12
      3091199.47     13789892.42      3090966.45     13789484.65
      3090167.55     13788660.77       3088328.4     13788061.59
#Sta/Elev= 30
  2684.2   59.51  3465.2   57.83  3614.2   56.05  4375.5   56.09  4425.5   53.76
  4835.5   55.16  4880.4   52.95 4909.25   54.84    4949   41.59    4961   41.35
    4985   33.35 4991.89   33.22    5000   30.72 5008.11   33.22    5015   33.35
    5039   41.35    5051   41.59 5088.45   54.07  5093.4   56.64  5129.3   55.22
  5319.3   55.15  5369.3   52.55  5469.3   53.57  5509.3    52.4  5589.3   54.92
  6288.9   54.57  6746.5   57.92  6976.5    56.8  8516.5   57.98  8680.8    60.9
#Mann= 5 ,-1 , 0
  2684.2     .12       0  3465.2      .1       0 4909.25    .035       0
 5088.45      .1       0  8680.8      .2       0
Bank Sta=4909.25,5088.45
XS Rating Curve= 0 ,0
Exp/Cntr=0.5,0.3

Type RM Length L Ch R = 1 ,97158.7 ,15.91,13.56,16.74
BEGIN DESCRIPTION:
Upstream Section of Bridge/Culvert/Weir
USACE Sims Bayou Rectification
Reach 8b Croquet to South Post Oak
File No. HSC 409-37
END DESCRIPTION:
XS GIS Cut Line= 6
      3091114.39     13792369.65      3091258.21      13791695.5
      3091389.58     13789602.59      3091374.06     13789013.07
      3090135.33     13788277.85      3088713.22     13787720.92
#Sta/Elev= 30
  2526.3   59.62  2711.3   57.82  3081.3   58.72  3357.4    56.7  3704.7   56.82
  3809.7   55.12  4064.7   56.22 4905.48   52.58  4906.9   55.56    4949   41.42
    4961   41.18    4985   33.18    5000   30.55    5015   33.18    5039   41.18
    5051   41.42 5089.71   54.33 5090.36   56.11  5539.3   53.92  5996.3   56.88
  6148.1   57.62  6183.1   55.72  6343.1   55.42  7398.5   58.02  7513.5   56.02
  7778.5   56.02  7858.5   58.12  8313.5   58.02  8793.5   60.22  8870.4   62.22
#Mann= 6 ,-1 , 0
  2526.3     .12       0  3357.4      .1       0  4906.9    .035       0
 5089.71      .1       0  5996.3      .2       0  8870.4      .2       0
#XS Ineff= 2 , 0
       0  4906.9   54.03 5089.71       0    53.9
Permanent Ineff=
       F       F
Bank Sta=4906.9,5090.36
XS Rating Curve= 0 ,0
Exp/Cntr=0.5,0.3

Type RM Length L Ch R = 3 ,97151.9 ,,,
BEGIN DESCRIPTION:
PIPELINE U/S POST OAK  Skew Factor 38 Degrees
END DESCRIPTION:
Bridge Culvert--1,0,-1,-1, 0
Deck Dist Width WeirC Skew NumUp NumDn MinLoCord MaxHiCord MaxSubmerge Is_Ogee
10,3,2.6,0, 115, 115, , , 0.95, 0, 1,1,,
  2526.3  2621.3  2651.3  2711.3  2816.3  2841.3  3081.3  3111.3  3126.3  3209.7
  3319.7  3357.4  3389.7  3419.7  3534.7  3674.7  3704.7  3809.7  3914.7  3989.7
  4064.7  4094.7  4182.1  4247.1  4412.1  4607.1 4683.26  4733.5 4865.76 4870.16
 4893.86 4893.95 4905.48 4906.89  4906.9    4925 4932.11 4941.82 4964.26 4972.16
 4975.64  4987.8 4989.38 5002.97 5003.68 5010.24 5010.79 5012.21 5013.87 5040.42
 5043.34 5048.87 5073.75 5074.91 5075.02 5090.36 5094.96 5123.37 5235.39  5539.3
  5629.3  5864.3  5898.1  5996.3  6003.1  6148.1  6163.1  6183.1  6198.1  6208.1
  6243.1  6258.1  6328.1  6343.1  6428.1  6548.1  6583.1  6648.1  6668.1  6678.1
  6688.1  6703.1  6713.1  6728.1  6753.1  6778.1  6933.1  6948.1  7203.1  7338.5
  7398.5  7418.5  7463.5  7513.5  7528.5  7543.5  7748.5  7778.5  7803.5  7828.5
  7858.5  7878.5  7883.5  7893.5  7898.5  7938.5  8093.5  8313.5  8333.5  8483.5
  8648.5  8653.5  8793.5  8843.5  8870.4
    59.6    59.4    58.7    57.8    58.4    57.9    58.7    58.1    57.6    57.1
      57   56.68    56.4    56.6      56    56.1    56.8    55.1    56.3    55.3
    56.2    55.1    55.3    55.2    54.8    54.3   54.01   54.13   55.34   55.34
   55.34   55.34   55.34   55.56   55.56   58.38   58.38   58.39   58.41   58.42
   58.42   58.43   58.43   58.44   58.45   58.45   58.45   58.45   58.45   58.48
   58.48   58.48   58.51   58.51   58.51   58.52   56.06   55.78   55.31    53.9
    54.4      56    56.3   56.86    56.9    57.6    56.9    55.7    55.7      56
    55.8    55.4    55.7    55.4    56.2    56.6    56.1    56.6    56.1    56.3
    55.9    56.1    56.8    56.8    55.9    56.3    57.1    56.9      57    57.9
      58    57.5    57.8      56    56.2    57.1    56.7      56    57.2    57.1
    58.1      58    57.9    57.1      57      58      58      58    58.7    59.3
    59.8    59.5    60.2    62.1    62.2
                                                                                
                                                                                
                                                                                
                              50   55.38   55.38   55.38   55.39   55.41   55.42
   55.42   55.43   55.43   55.44   55.45   55.45   55.45   55.45   55.45   55.48
   55.48   55.48   55.48   55.48   55.48   55.48
                                                                                
                                                                                
                                                                                
                                                                                
                                                                                
                                        
  2526.3  2621.3  2651.3  2711.3  2816.3  2841.3  3081.3  3111.3  3126.3  3209.7
  3319.7  3357.4  3389.7  3419.7  3534.7  3674.7  3704.7  3809.7  3914.7  3989.7
  4064.7  4094.7  4182.1  4247.1  4412.1  4607.1 4683.26  4733.5 4865.76 4870.16
 4893.86 4893.95 4905.48 4909.77 4909.78    4925 4932.11 4941.82 4964.26 4972.16
 4975.64  4987.8 4989.38 5002.97 5003.68 5010.24 5010.79 5012.21 5013.87 5040.42
 5043.34 5048.87 5073.75 5074.91 5075.02 5090.36 5094.96 5123.37 5235.39  5539.3
  5629.3  5864.3  5898.1  5996.3  6003.1  6148.1  6163.1  6183.1  6198.1  6208.1
  6243.1  6258.1  6328.1  6343.1  6428.1  6548.1  6583.1  6648.1  6668.1  6678.1
  6688.1  6703.1  6713.1  6728.1  6753.1  6778.1  6933.1  6948.1  7203.1  7338.5
  7398.5  7418.5  7463.5  7513.5  7528.5  7543.5  7748.5  7778.5  7803.5  7828.5
  7858.5  7878.5  7883.5  7893.5  7898.5  7938.5  8093.5  8313.5  8333.5  8483.5
  8648.5  8653.5  8793.5  8843.5  8870.4
    59.6    59.4    58.7    57.8    58.4    57.9    58.7    58.1    57.6    57.1
      57   56.68    56.4    56.6      56    56.1    56.8    55.1    56.3    55.3
    56.2    55.1    55.3    55.2    54.8    54.3   54.01   54.13   55.34   58.33
   58.35   58.35   58.36   58.37   58.37   58.38   58.38   58.39   58.41   58.42
   58.42   58.43   58.43   58.44   58.45   58.45   58.45   58.45   58.45   58.48
   58.48   58.48   58.51   58.51   58.51   58.52   56.06   55.78   55.31    53.9
    54.4      56    56.3   56.86    56.9    57.6    56.9    55.7    55.7      56
    55.8    55.4    55.7    55.4    56.2    56.6    56.1    56.6    56.1    56.3
    55.9    56.1    56.8    56.8    55.9    56.3    57.1    56.9      57    57.9
      58    57.5    57.8      56    56.2    57.1    56.7      56    57.2    57.1
    58.1      58    57.9    57.1      57      58      58      58    58.7    59.3
    59.8    59.5    60.2    62.1    62.2
                                                                                
                                                                                
                                                                                
                              51   55.38   55.38   55.38   55.39   55.41   55.42
   55.42   55.43   55.43   55.44   55.45   55.45   55.45   55.45   55.45   55.48
   55.48   55.48   55.48   55.48   55.48   55.48   55.48
                                                                                
                                                                                
                                                                                
                                                                                
                                                                                
                                        
Pier Skew, UpSta & Num, DnSta & Num=  ,4925, 2 ,4925, 2 , 0 , 0 , 0 ,,
     1.4     1.4
   45.67   56.38
     1.4     1.4
   45.67   56.38
Pier Skew, UpSta & Num, DnSta & Num=  ,4964.3, 2 ,4964.3, 2 , 0 , 0 , 0 ,,
     1.4     1.4
    39.7   56.41
     1.4     1.4
    39.7   56.41
Pier Skew, UpSta & Num, DnSta & Num=  ,5003, 2 ,5003, 2 , 0 , 0 , 0 ,,
     1.4     1.4
   34.16   56.45
     1.4     1.4
   34.16   56.45
Pier Skew, UpSta & Num, DnSta & Num=  ,5043.3, 2 ,5043.3, 2 , 0 , 0 , 0 ,,
     1.4     1.4
   45.57   56.48
     1.4     1.4
   45.57   56.48
BR Coef= 1 , 1 , 0 ,1.25, 0 ,,,0.8,0,2,0,
WSPro=,,,, 1 ,,,, 0 ,,,, 0 ,,,,-1 ,-1 ,-1 , 0 , 0 , 0 , 0 , 0
BC Design=,, 0 ,, 0 ,,,,,,
BC HTab HWMax=62.22
BC Use User HTab Curves=0
BC User HTab FreeFlow(D)= 0

Type RM Length L Ch R = 1 ,97145.1 ,133.3,140.27,137.86
BEGIN DESCRIPTION:
Upstream Section of Bridge/Culvert/Weir
USACE Sims Bayou Rectification
Reach 8b Croquet to South Post Oak
File No. HSC 409-37
END DESCRIPTION:
XS GIS Cut Line= 6
      3091141.31     13792356.05      3091307.29     13791696.07
      3091427.71     13789452.94      3091414.58     13788986.47
      3091101.42     13788733.53      3088792.45     13787658.45
#Sta/Elev= 30
  2526.3    59.6  3357.4   56.68  3704.7    56.8  3809.7    55.1  4064.7    56.2
  4322.1    53.4 4733.53   54.13 4856.69   56.12 4905.52   52.56 4909.78   54.48
    4949   41.41    4961   41.17    4985   33.17    5000   30.53    5015   33.17
    5039   41.17    5051   41.41 5092.29   56.07  5599.3    53.1  5996.3   56.86
  6148.1    57.6  6183.1    55.7  6343.1    55.4  7398.5      58  7513.5      56
  7778.5      56  7858.5    58.1  8313.5      58  8793.5    60.2  8870.4    62.2
#Mann= 6 ,-1 , 0
  2526.3     .12       0  3357.4      .1       0 4909.78    .035       0
 5092.29      .1       0  5996.3      .2       0  8870.4      .2       0
#XS Ineff= 2 , 0
       0 4909.78   54.09 5092.29       0    54.1
Permanent Ineff=
       F       F
Bank Sta=4909.78,5092.29
XS Rating Curve= 0 ,0
Exp/Cntr=0.5,0.3

Type RM Length L Ch R = 3 ,97075   ,,,
BEGIN DESCRIPTION:
POST OAK ROAD Skew Factor 38 Degrees
Structure ID: C00-42
END DESCRIPTION:
Bridge Culvert--1,0,-1,-1, 0
Deck Dist Width WeirC Skew NumUp NumDn MinLoCord MaxHiCord MaxSubmerge Is_Ogee
10,110,2.6,0, 60, 60, , , 0.95, 0, 1,1,,
  2526.3  2621.3  2711.3  3081.3  3126.3  3389.7  3674.7  3704.7  3809.7  3914.7
  3989.7  4064.7  4094.7  4247.1  4322.1  4412.1  4662.5 4777.93 4832.92 4846.58
 4856.69 4880.99  4881.1 4905.52 4910.09 4910.18  5048.9 5073.79 5092.29 5092.51
 5129.88  5172.2 5325.09    5436  5599.3  5629.3  6148.1  6183.1  6258.1  6548.1
  6688.1  6713.1  6753.1  6933.1  7203.1  7398.5  7463.5  7513.5  7543.5  7748.5
  7778.5  7803.5  7858.5  7898.5  7938.5  8313.5  8333.5  8793.5  8843.5  8870.4
    59.6    59.4    57.8   58.71   57.61   56.53   56.31   56.81    55.7   56.31
   55.43   56.21   55.66   55.23   55.02   54.81    54.1   55.87   56.44   56.53
   56.59   56.58   57.58    57.6   57.62   57.62   58.08   58.17   58.23   57.23
   57.44   57.68   55.18    54.1   54.35   54.41    57.6    55.7    55.4    56.6
    55.9    56.8    55.9    57.1      57      58    57.8      56    57.1    56.7
      56    57.2    58.1      57      58      58    58.7    60.2    62.1    62.2
   59.57   59.37   57.77   58.67   57.57   56.37   56.07   56.77   55.07   56.27
   55.27   56.17   55.07   55.17   53.37   54.77   54.06   54.39   55.54   55.07
   56.09   54.32   54.31   52.53   51.16   54.69   55.15   56.22   56.04   56.04
   55.39   56.05   53.86   53.87   53.07   54.37   57.57   55.67   55.37   56.57
   55.87   56.77   55.87   57.07   56.97   57.97   57.77   55.97   57.07   56.67
   55.97   57.17   58.07   56.97   57.97   57.97   58.67   60.17   62.07   62.17
  2526.3  2621.3  2711.3  3081.3  3126.3  3389.7  3674.7  3704.7  3809.7  3914.7
  3989.7  4064.7  4094.7  4247.1  4322.1  4412.1  4662.5 4777.93 4832.92 4846.58
 4856.69 4880.99  4881.1 4905.52 4910.09 4910.18  5048.9 5073.79 5092.29 5092.51
 5129.88  5172.2 5325.09    5436  5599.3  5629.3  6148.1  6183.1  6258.1  6548.1
  6688.1  6713.1  6753.1  6933.1  7203.1  7398.5  7463.5  7513.5  7543.5  7748.5
  7778.5  7803.5  7858.5  7898.5  7938.5  8313.5  8333.5  8793.5  8843.5  8870.4
    59.6    59.4    57.8   58.71   57.61   56.53   56.31   56.81    55.7   56.31
   55.43   56.21   55.66   55.23   55.02   54.81    54.1   55.87   56.44   56.53
   56.59   56.58   57.58    57.6   57.62   57.62   58.08   58.17   58.23   57.23
   57.44   57.68   55.18    54.1   54.35   54.41    57.6    55.7    55.4    56.6
    55.9    56.8    55.9    57.1      57      58    57.8      56    57.1    56.7
      56    57.2    58.1      57      58      58    58.7    60.2    62.1    62.2
   58.92   58.72   57.12   58.02   56.92   55.72   55.42   56.12   54.42   55.62
   54.62   55.52   54.42   54.52   52.72   54.12   53.41   53.74   54.89   54.42
   55.44   53.67   53.66   51.88   50.51   54.04    54.5   55.57   55.39   55.39
   54.74    55.4   53.21   53.22   52.42   53.72   56.92   55.02   54.72   55.92
   55.22   56.12   55.22   56.42   56.32   57.32   57.12   55.32   56.42   56.02
   55.32   56.52   57.42   56.32   57.32   57.32   58.02   59.52   61.42   61.52
Pier Skew, UpSta & Num, DnSta & Num=  ,4932.1, 2 ,4932.1, 2 , 0 , 0 , 0 ,,
       2       2
   44.91   55.76
       2       2
   44.26   55.11
Pier Skew, UpSta & Num, DnSta & Num=  ,4972.2, 2 ,4972.2, 2 , 0 , 0 , 0 ,,
       2       2
   39.14    55.9
       2       2
   38.49   55.25
Pier Skew, UpSta & Num, DnSta & Num=  ,5010.8, 2 ,5010.8, 2 , 0 , 0 , 0 ,,
       2       2
   34.68   56.03
       2       2
   34.03   55.38
Pier Skew, UpSta & Num, DnSta & Num=  ,5048.9, 2 ,5048.9, 2 , 0 , 0 , 0 ,,
       2       2
   45.84   56.19
       2       2
   45.19   55.54
BR Coef= 1 , 1 , 0 ,1.25, 0 ,,,0.8,0,1.2,0,
WSPro=,,,, 1 ,,,, 0 ,,,, 0 ,,,,-1 ,-1 ,-1 , 0 , 0 , 0 , 0 , 0
BC Design=,, 0 ,, 0 ,,,,,,
BC HTab HWMax=62.2
BC Use User HTab Curves=0
BC User HTab FreeFlow(D)= 0

Type RM Length L Ch R = 1 ,97004.9 ,675.69,663.91,634.06
BEGIN DESCRIPTION:
Downstream Section of Bridge/Culvert/Weir
USACE Sims Bayou Rectification
Reach 8b Croquet to South Post Oak
File No. HSC 409-37
END DESCRIPTION:
XS GIS Cut Line= 6
      3091248.11     13792281.94      3091414.09     13791621.95
      3091534.51     13789378.82      3091521.38     13788912.35
      3091208.22     13788659.41      3088899.25     13787584.34
#Sta/Elev= 30
  2526.3   58.89  3357.4   55.97  3704.7   56.09  3809.7   54.39  4064.7   55.49
  4322.1   52.69 4733.53   53.42 4856.69   55.41 4905.52   51.85 4910.22   54.19
    4949   41.26    4961   41.02    4985   33.02    5000   30.38    5015   33.02
    5039   41.02    5051   41.26 5094.12   55.63  5599.3   52.39  5996.3   56.15
  6148.1   56.89  6183.1   54.99  6343.1   54.69  7398.5   57.29  7513.5   55.29
  7778.5   55.29  7858.5   57.39  8313.5   57.29  8793.5   59.49  8870.4   61.49
#Mann= 6 ,-1 , 0
  2526.3     .12       0  3357.4      .1       0 4910.22    .035       0
 5094.12      .1       0  5996.3      .2       0  8870.4      .2       0
#XS Ineff= 2 , 0
       0 4910.22    53.6 5094.12       0    53.6
Permanent Ineff=
       F       F
Bank Sta=4910.22,5094.12
XS Rating Curve= 0 ,0
Exp/Cntr=0.5,0.3

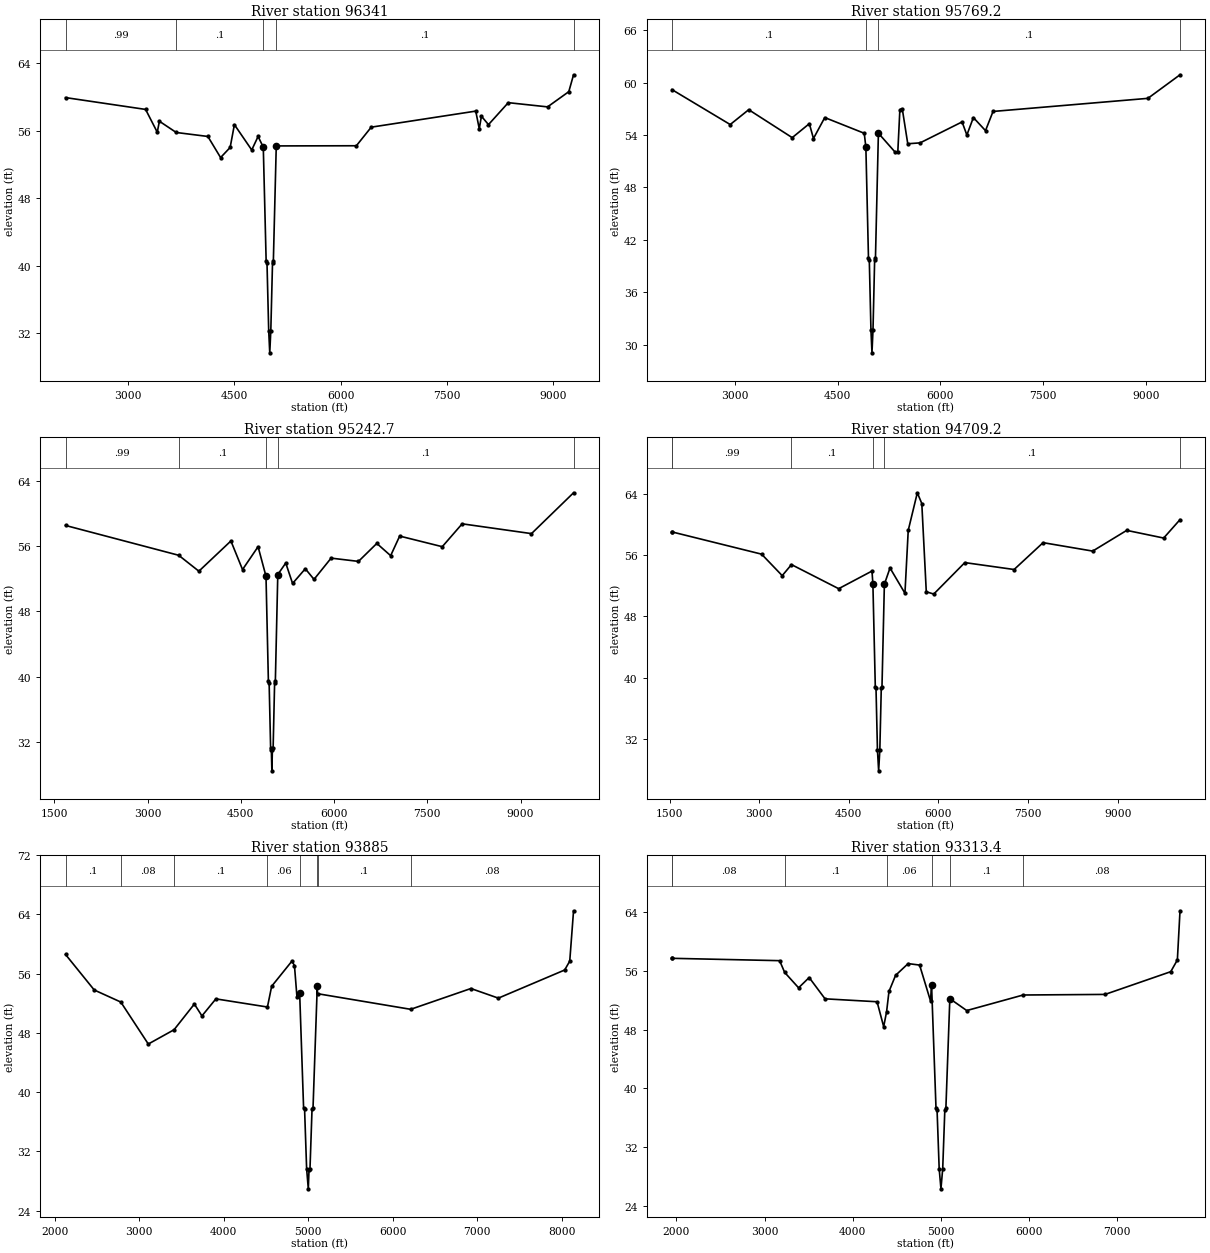
Type RM Length L Ch R = 1 ,96341   ,593.46,571.8,547.92
BEGIN DESCRIPTION:
Cross Section 98408.4
USACE Sims Bayou Rectification
Reach 8b Croquet to South Post Oak
File No. HSC 409-37
END DESCRIPTION:
XS GIS Cut Line= 6
       3092489.9     13792464.67      3092345.46     13791357.25
      3092061.13     13789366.95      3091960.78      13788731.4
       3090190.7     13788150.46      3088774.23     13787530.75
#Sta/Elev= 30
  2113.5    59.9  3245.3    58.5  3410.3    55.8  3440.3    57.1  3678.5   55.77
  4125.3    55.3  4305.3    52.8  4440.3      54  4500.3    56.7  4745.3    53.7
  4835.3    55.3 4908.62   54.03    4949   40.57    4961   40.33    4985   32.33
    5000   29.69    5015   32.33    5039   40.33    5051   40.57 5091.94   54.18
  6224.2    54.2  6434.2    56.4  7911.1    58.3  7961.1    56.2  7991.1    57.7
  8091.1    56.7  8371.1    59.3  8926.1    58.8  9226.1    60.6  9293.3    62.6
#Mann= 5 ,-1 , 0
  2113.5     .99       0  3678.5      .1       0 4908.62    .035       0
 5091.94      .1       0  9293.3      .2       0
Bank Sta=4908.62,5091.94
XS Rating Curve= 0 ,0
Exp/Cntr=0.3,0.1

Type RM Length L Ch R = 1 ,95769.2 ,541.11,526.46,511.54
BEGIN DESCRIPTION:
Cross Section 97839.0-Interpolated
USACE Sims Bayou Rectification
Reach 8b Croquet to South Post Oak
File No. HSC 409-37
END DESCRIPTION:
XS GIS Cut Line= 5
      3093026.13     13792386.26      3092902.83     13790068.24
       3092308.9     13788758.89      3091660.98     13788515.92
      3088880.31     13787490.05
#Sta/Elev= 30
    2081    59.2    2931    55.2    3201    56.9    3836    53.7    4086    55.3
    4146    53.6    4311      56  4887.3    54.2 4910.91   52.62    4949   39.92
    4961   39.68    4985   31.68    5000   29.05    5015   31.68    5039   39.68
    5051   39.92 5093.86   54.21  5342.3      52  5377.3    52.1  5407.3    56.9
  5442.3      57  5522.3      53  5702.3    53.1    6315    55.5    6385      54
    6480      56    6657    54.5    6767    56.7    9027    58.2  9495.9    60.9
#Mann= 4 ,-1 , 0
    2081      .1       0 4910.91    .035       0 5093.86      .1       0
  9495.9      .2       0
Bank Sta=4910.91,5093.86
XS Rating Curve= 0 ,0
Exp/Cntr=0.3,0.1

Type RM Length L Ch R = 1 ,95242.7 ,514.16,533.52,554.91
BEGIN DESCRIPTION:
Cross Section 97312.7
USACE Sims Bayou Rectification
Reach 8a South Post Oak to Bathurst Drive
File No. HSC 409-34
END DESCRIPTION:
XS GIS Cut Line= 6
      3093532.94     13792511.29      3093532.94      13791056.2
      3093482.77     13789835.26      3092847.21      13788865.2
       3091709.9     13788430.34      3088782.99     13787359.93
#Sta/Elev= 30
    1681    58.5    3501   54.85  3826.1    52.9  4341.1    56.6  4528.1    53.1
  4778.1    55.9 4905.47   52.28    4944   39.44    4956    39.2    4980    31.2
 4991.89   30.96    5000   28.46 5008.11   30.96    5020    31.2    5044    39.2
    5056   39.44 5095.16   52.49  5223.1    53.9  5333.1    51.4  5537.8    53.2
  5677.8    51.9  5952.8    54.5  6392.8    54.1  6687.8    56.3  6910.4    54.8
  7055.4    57.2  7740.4    55.9  8060.4    58.7  9175.4    57.5  9851.9    62.5
#Mann= 5 ,-1 , 0
    1681     .99       0    3501      .1       0 4905.47    .035       0
 5095.16      .1       0  9851.9      .2       0
Bank Sta=4905.47,5095.16
XS Rating Curve= 0 ,0
Exp/Cntr=0.3,0.1

Type RM Length L Ch R = 1 ,94709.2 ,782.64,824.19,877.24
BEGIN DESCRIPTION:
Cross Section 96778.3
USACE Sims Bayou Rectification
Reach 8a South Post Oak to Bathurst Drive
File No. HSC 409-34
END DESCRIPTION:
XS GIS Cut Line= 6
      3093716.92     13792511.29      3093750.37     13789433.86
      3093549.67     13788898.65      3093134.75     13788706.79
      3089884.44     13787373.61      3089002.48      13787321.4
#Sta/Elev= 30
    1541      59  1541.1      59  3041.1    56.1  3386.1    53.3  3541.1   54.74
  4331.1    51.6  4888.7    53.9 4903.95   52.19    4944   38.84    4956    38.6
    4980    30.6    5000   27.86    5020    30.6    5044    38.6    5056   38.84
 5096.03   52.18  5190.3    54.3  5440.3      51  5495.3    59.2  5647.4    64.1
  5722.4    62.7  5797.4    51.2  5922.4    50.9  6442.4      55  7267.4    54.1
  7752.4    57.6  8582.4    56.5  9152.4    59.2  9770.5    58.2 10044.1    60.6
#Mann= 6 ,-1 , 0
    1541     .99       0  1541.1     .99       0  3541.1      .1       0
 4903.95    .035       0 5096.03      .1       0 10044.1      .2       0
Bank Sta=4903.95,5096.03
XS Rating Curve= 0 ,0
Exp/Cntr=0.3,0.1

Type RM Length L Ch R = 1 ,93885   ,569.61,571.61,575.96
BEGIN DESCRIPTION:
Cross Section 95895.2-Interpolated
USACE Sims Bayou Rectification
Reach 8a South Post Oak to Bathurst Drive
File No. HSC 409-34
END DESCRIPTION:
XS GIS Cut Line= 5
      3094036.69     13792362.96      3094293.16     13789501.31
      3094321.15      13789011.5       3095041.4     13788173.88
       3095356.5     13786661.39
#Sta/Elev= 30
  2126.1    58.6  2466.1    53.8  2780.6   52.17  3106.1    46.5  3410.9   48.43
  3651.1    51.9  3741.1    50.3  3906.1    52.6  4516.2    51.5  4566.1    54.3
  4806.1    57.7  4836.1    57.1  4866.1    52.8 4897.53   53.41    4944   37.92
    4956   37.68    4980   29.68    5000   26.94 5008.11   29.44    5020   29.68
    5044   37.68    5056   37.92 5105.95   54.29  5109.2    53.3  6211.7   51.19
  6924.5      54  7249.5    52.7  8034.5    56.5  8094.5    57.7  8139.5    64.5
#Mann= 8 ,-1 , 0
  2126.1      .1       0  2780.6     .08       0  3410.9      .1       0
  4516.2     .06       0 4897.53    .035       0 5105.95     .06       0
  5109.2      .1       0  6211.7     .08       0
Bank Sta=4897.53,5105.95
XS Rating Curve= 0 ,0
Exp/Cntr=0.3,0.1

Type RM Length L Ch R = 1 ,93313.4 ,727.09,729.25,732.45
BEGIN DESCRIPTION:
Cross Section 95317.3
USACE Sims Bayou Rectification
Reach 8a South Post Oak to Bathurst Drive
File No. HSC 409-34
END DESCRIPTION:
XS GIS Cut Line= 6
      3094398.13     13792362.52      3094623.81      13791234.1
      3094805.72     13789717.56      3094857.01     13789185.38
      3095087.84     13788595.49      3095417.81     13786709.14
#Sta/Elev= 30
  1949.8    57.8    1954   57.72  3170.6    57.4  3227.7    55.8  3385.6    53.7
  3505.6    55.1  3685.6    52.2  4275.6    51.8  4350.6    48.4  4383.7   50.45
  4410.6    53.2  4485.6    55.4    4628      57    4758    56.8  4881.7   51.91
 4893.65   54.06    4944   37.28    4956   37.04    4980   29.04    5000    26.3
    5020   29.04    5044   37.04    5056   37.28 5100.83   52.22  5292.6    50.6
  5931.9   52.72  6861.1    52.8  7606.1    55.9  7681.1    57.5  7711.1    64.2
#Mann= 7 ,-1 , 0
  1949.8      .1       0    1954     .08       0  3227.7      .1       0
  4383.7     .06       0 4893.65    .035       0 5100.83      .1       0
  5931.9     .08       0
Bank Sta=4893.65,5100.83
XS Rating Curve= 0 ,0
Exp/Cntr=0.3,0.1

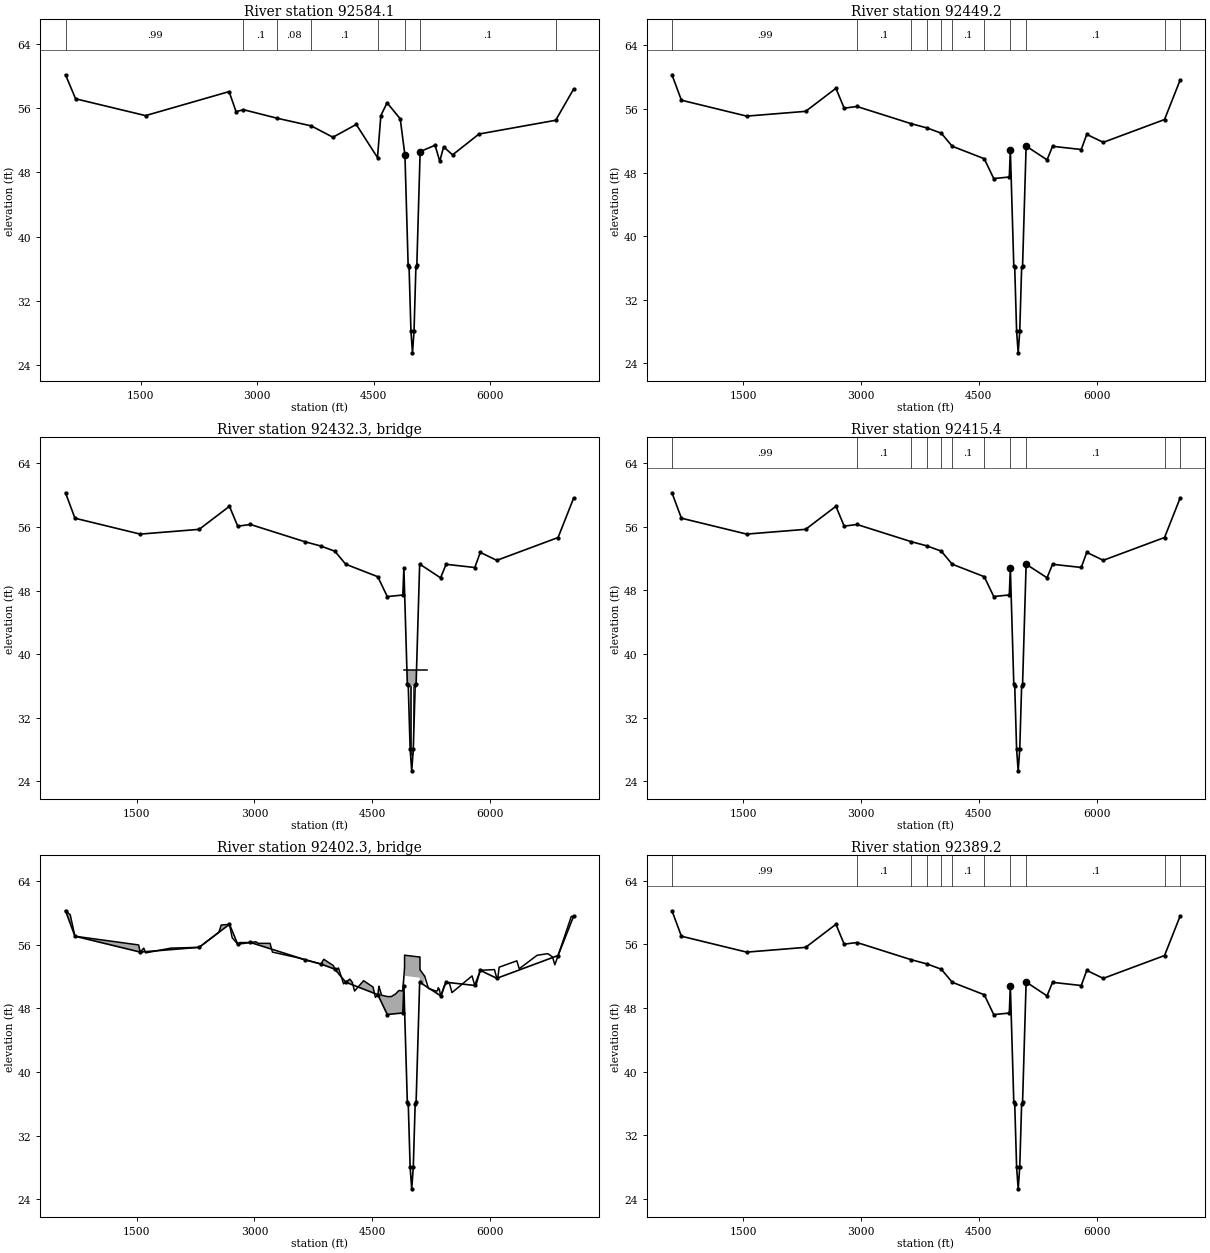
Type RM Length L Ch R = 1 ,92584.1 ,139.85,134.96,115.94
BEGIN DESCRIPTION:
Cross Section 94582.0 - Interpolated
USACE Sims Bayou Rectification
Reach 8a South Post Oak to Bathurst Drive
File No. HSC 409-34
END DESCRIPTION:
XS GIS Cut Line= 6
      3095629.62     13793774.24      3095791.46     13791405.28
      3095518.56     13790807.84      3095468.63     13789867.46
      3095576.81     13789284.92      3095709.96     13787320.94
#Sta/Elev= 30
   534.9    60.2   664.9    57.2  1564.9    55.1  2639.9    58.1  2729.9    55.6
  2825.2   55.84  3259.9   54.77  3696.4   53.82  3976.2    52.4  4276.2      54
  4549.8   49.86  4592.9    55.1  4672.9    56.7  4842.4    54.7 4902.98   50.13
    4944   36.46    4956   36.22    4980   28.22    5000   25.48    5020   28.22
    5044   36.22    5056   36.46 5098.45   50.61  5290.8    51.4  5350.8    49.4
  5400.8    51.2  5515.8    50.2  5855.8    52.8  6842.7   54.52  7072.6    58.4
#Mann= 8 ,-1 , 0
   534.9     .99       0  2825.2      .1       0  3259.9     .08       0
  3696.4      .1       0  4549.8     .06       0 4902.98    .035       0
 5098.45      .1       0  6842.7     .08       0
Bank Sta=4902.98,5098.45
XS Rating Curve= 0 ,0
Exp/Cntr=0.5,0.3

Type RM Length L Ch R = 1 ,92449.2 ,40.33,33.82,41.06
BEGIN DESCRIPTION:
Upstream Section of Bridge/Culvert/Weir
USACE Sims Bayou Rectification
Reach 8a South Post Oak to Bathurst Drive
File No. HSC 409-34
END DESCRIPTION:
XS GIS Cut Line= 6
      3095666.44     13793767.53      3095880.26     13791354.16
       3095768.7     13790375.77      3095619.73     13790021.19
      3095695.32     13789415.29      3095725.42      13787359.2
#Sta/Elev= 30
   597.1   60.31   717.1   57.11  1547.1   55.11  2297.1   55.71  2682.1   58.61
  2787.1   56.11  2949.6   56.32  3638.4   54.16  3841.4   53.62  4022.3   52.96
    4161   51.32  4568.6   49.75 4689.31   47.25 4887.21   47.45 4900.31   50.87
    4944   36.31    4956   36.07    4980   28.07    5000   25.33    5020   28.07
    5044   36.07    5056   36.31 5101.12   51.34  5367.1   49.61  5437.1   51.31
  5802.1   50.91  5872.1   52.81  6082.1   51.81  6861.3   54.68  7058.1   59.61
#Mann= 11 ,-1 , 0
   597.1     .99       0  2949.6      .1       0  3638.4     .08       0
  3841.4      .1       0  4022.3     .06       0    4161      .1       0
  4568.6     .06       0 4900.31    .035       0 5101.12      .1       0
  6861.3     .08       0  7058.1      .2       0
#XS Ineff= 2 , 0
       0 4900.31   47.25 5101.12       0   49.62
Permanent Ineff=
       F       F
Bank Sta=4900.31,5101.12
XS Rating Curve= 0 ,0
Exp/Cntr=0.5,0.3

Type RM Length L Ch R = 3 ,92432.3 ,,,
BEGIN DESCRIPTION:
24" PIPE AT FOOTBRIDGE
END DESCRIPTION:
Bridge Culvert--1,0,-1,-1, 0
Deck Dist Width WeirC Skew NumUp NumDn MinLoCord MaxHiCord MaxSubmerge Is_Ogee
10,2,2.6,0, 2, 2, , , 0.95, 0, 1,1,,
    4900    5200
      38      38
      36      36
    4900    5200
      38      38
      36      36
Pier Skew, UpSta & Num, DnSta & Num=  ,4985.1, 2 ,4985.1, 2 , 0 , 0 , 0 ,,
     1.4     1.4
   30.69   36.98
     1.4     1.4
   30.69   36.98
Pier Skew, UpSta & Num, DnSta & Num=  ,5015.1, 2 ,5015.1, 2 , 0 , 0 , 0 ,,
     1.4     1.4
   31.33      37
     1.4     1.4
   31.33      37
BR Coef= 1 , 1 , 0 ,1.25, 0 ,,,0.8,-1,2,0,
WSPro=,,,, 1 ,,,, 0 ,,,, 0 ,,,,-1 ,-1 ,-1 , 0 , 0 , 0 , 0 , 0
BC Design=,, 0 ,, 0 ,,,,,,
BC HTab HWMax=60.31
BC Use User HTab Curves=0
BC User HTab FreeFlow(D)= 0

Type RM Length L Ch R = 1 ,92415.4 ,26,26.18,26.49
BEGIN DESCRIPTION:
Upstream Section of Bridge/Culvert/Weir
USACE Sims Bayou Rectification
Reach 8a South Post Oak to Bathurst Drive
File No. HSC 409-34
END DESCRIPTION:
XS GIS Cut Line= 6
      3095728.45     13793790.21      3095951.87     13791330.04
      3095717.24     13789743.99      3095728.12     13789415.29
      3095734.31     13789081.68      3095805.56     13787358.72
#Sta/Elev= 30
   597.1    60.3   717.1    57.1  1547.1    55.1  2297.1    55.7  2682.1    58.6
  2787.1    56.1  2949.6   56.31  3638.4   54.15  3841.4   53.61  4022.3   52.95
    4161   51.31  4568.6   49.74  4689.3   47.24  4887.2   47.44 4900.31   50.84
    4944   36.27    4956   36.03    4980   28.03    5000    25.3    5020   28.03
    5044   36.03    5056   36.27 5101.12   51.31  5367.1    49.6  5437.1    51.3
  5802.1    50.9  5872.1    52.8  6082.1    51.8  6861.3   54.67  7058.1    59.6
#Mann= 11 ,-1 , 0
   597.1     .99       0  2949.6      .1       0  3638.4     .08       0
  3841.4      .1       0  4022.3     .06       0    4161      .1       0
  4568.6     .06       0 4900.31    .035       0 5101.12      .1       0
  6861.3     .08       0  7058.1      .2       0
#XS Ineff= 2 , 0
       0 4900.31    49.5 5101.12       0   49.61
Permanent Ineff=
       F       F
Bank Sta=4900.31,5101.12
XS Rating Curve= 0 ,0
Exp/Cntr=0.5,0.3

Type RM Length L Ch R = 3 ,92402.3 ,,,
BEGIN DESCRIPTION:
FOOTBRIDGE NEAR BUXLEY ROAD
Structure ID: C00-40
END DESCRIPTION:
Bridge Culvert--1,0,-1,-1, 0
Deck Dist Width WeirC Skew NumUp NumDn MinLoCord MaxHiCord MaxSubmerge Is_Ogee
10,6,2.6,0, 126, 126, , , 0.95, 0, 1,1,,
   597.1   657.1   717.1  1527.1  1547.1  1592.1  1617.1  1937.1  2297.1  2547.1
  2577.1  2682.1  2717.1  2787.1  2812.1  2942.1  2949.6  3018.6  3048.6  3198.6
  3228.6  3546.1  3638.4  3841.4  3846.1  3881.1  4003.5  4022.3  4028.5  4068.5
  4133.5    4161  4213.5  4243.5  4273.5  4388.1  4508.1  4538.1  4568.1  4568.6
  4581.8  4583.1  4601.8  4616.8  4689.3  4739.5  4740.1  4794.4  4794.8  4837.8
  4838.2  4883.9  4887.2  4900.3 4900.31  4908.6 4908.71  4908.8 4909.09  4909.2
 4909.31  4928.4    4929  4946.1  4947.1  4967.1  4975.7  4975.8    4979  4982.3
  4985.6  4985.8    5020  5020.9    5027  5027.1  5047.6  5054.4  5067.3  5082.5
 5101.11 5101.12 5105.09  5105.2 5105.31 5105.39  5105.5  5105.6  5161.5  5163.4
  5212.7  5213.8  5270.8  5271.6  5309.9  5311.5  5332.1  5337.1  5351.8  5366.8
  5367.1  5381.8  5387.1  5411.8  5437.1  5439.3  5482.1  5512.1  5767.1  5802.1
  5822.1  5872.1  6052.1  6082.1  6097.1  6112.1  6337.1  6367.1    6595    6730
    6790    6820    6835  6861.3    7030  7058.1
    60.3    59.8    57.1      56    55.1    55.6      55    55.6    55.7    57.6
    58.5    58.6    56.9    56.1    56.3    56.3   56.31    56.4    56.2    56.2
    55.1    54.4   54.15   53.61    53.6    54.2    53.4   52.95    52.8    53.1
    51.1   51.31    51.7    51.3    50.2    51.5    50.7    49.4    49.7   49.74
   50.71   50.81   50.18   49.68    49.5    49.5    49.5   49.83   49.83   50.27
   50.27    50.2   50.59      52      52   53.11   53.11   53.11   53.11   54.71
   54.71   54.69   54.69   54.66   54.66   54.64   54.63   54.63   54.62   54.62
   54.62   54.62   54.57   54.57   54.57   54.57   54.54   54.53   54.52    54.5
    54.5    54.5   54.47   54.47   52.87   52.87   52.87   52.87   52.11   52.13
   50.52   50.52   50.33   50.32   50.19   50.19    50.3   50.61    50.4   49.62
   49.61   49.83   49.91    50.8   51.31    51.3    51.1      50    52.1    50.9
    51.1    52.8    52.9    51.8      52    53.2      54      53    54.7    54.9
    54.5    53.5    53.9   54.67    59.6    59.6
                                                                                
                                                                                
                                                                                
                                                                                
                                                                                
                                                                   52.11   52.11
   52.11   52.09   52.09   52.06   52.06   52.04   52.03   52.03   52.02   52.02
   52.02   52.02   51.97   51.97   51.97   51.97   51.94   51.93   51.92    51.9
    51.9      51      51      51      51      51      51      51      51   52.12
   50.51   50.51   50.32   50.31   49.82   49.83   49.98    50.6   50.11   49.61
    49.6   49.82    49.9   50.59    51.3   51.29    51.1      50    52.1    50.9
    51.1    52.8    52.9    51.8      52    53.2      54      53    54.7    54.9
    54.5    53.5    53.9   54.67    59.6    59.6
   597.1   657.1   717.1  1527.1  1547.1  1592.1  1617.1  1937.1  2297.1  2547.1
  2577.1  2682.1  2717.1  2787.1  2812.1  2942.1  2949.6  3018.6  3048.6  3198.6
  3228.6  3546.1  3638.4  3841.4  3846.1  3881.1  4003.5  4022.3  4028.5  4068.5
  4133.5    4161  4213.5  4243.5  4273.5  4388.1  4508.1  4538.1  4568.1  4568.6
  4581.8  4583.1  4601.8  4616.8  4689.3  4739.5  4740.1  4794.4  4794.8  4837.8
  4838.2  4883.9  4887.2  4900.3 4900.31  4908.6 4908.71  4908.8 4909.09  4909.2
 4909.31  4928.4    4929  4946.1  4947.1  4967.1  4975.7  4975.8    4979  4982.3
  4985.6  4985.8    5020  5020.9    5027  5027.1  5047.6  5054.4  5067.3  5082.5
 5101.11 5101.12 5105.09  5105.2 5105.31 5105.39  5105.5  5105.6  5161.5  5163.4
  5212.7  5213.8  5270.8  5271.6  5309.9  5311.5  5332.1  5337.1  5351.8  5366.8
  5367.1  5381.8  5387.1  5411.8  5437.1  5439.3  5482.1  5512.1  5767.1  5802.1
  5822.1  5872.1  6052.1  6082.1  6097.1  6112.1  6337.1  6367.1    6595    6730
    6790    6820    6835  6861.3    7030  7058.1
    60.3    59.8    57.1      56    55.1    55.6      55    55.6    55.7    57.6
    58.5    58.6    56.9    56.1    56.3    56.3   56.31    56.4    56.2    56.2
    55.1    54.4   54.15   53.61    53.6    54.2    53.4   52.95    52.8    53.1
    51.1   51.31    51.7    51.3    50.2    51.5    50.7    49.4    49.7   49.74
   50.71   50.81   50.18   49.68    49.5    49.5    49.5   49.83   49.83   50.27
   50.27    50.2   50.59    52.4    52.4   53.11   53.11   53.11   53.11   54.71
   54.71   54.69   54.69   54.66   54.66   54.64   54.63   54.63   54.62   54.62
   54.62   54.62   54.57   54.57   54.57   54.57   54.54   54.53   54.52    54.5
    54.5    54.5   54.47   54.47   52.87   52.87   52.87   52.87   52.11   52.13
   50.52   50.52   50.33   50.32   50.19   50.19    50.3   50.61    50.4   49.62
   49.61   49.83   49.91    50.8   51.31    51.3    51.1      50    52.1    50.9
    51.1    52.8    52.9    51.8      52    53.2      54      53    54.7    54.9
    54.5    53.5    53.9   54.67    59.6    59.6
                                                                                
                                                                                
                                                                                
                                                                                
                                                                                
                                                                   52.06   52.06
   52.06   52.04   52.04   52.01   52.01   51.99   51.98   51.98   51.97   51.97
   51.97   51.97   51.92   51.92   51.92   51.92   51.89   51.88   51.87   51.85
   51.85
                                                                                
                                                                                
                                                                                
                                                
BR Coef= 1 , 1 , 0 ,1.25, 0 ,,,0.8,0,2,0,
WSPro=,,,, 1 ,,,, 0 ,,,, 0 ,,,,-1 ,-1 ,-1 , 0 , 0 , 0 , 0 , 0
BC Design=,, 0 ,, 0 ,,,,,,
BC HTab HWMax=60.3
BC Use User HTab Curves=0
BC User HTab FreeFlow(D)= 0

Type RM Length L Ch R = 1 ,92389.2 ,759.32,812.16,864.06
BEGIN DESCRIPTION:
Downstream Section of Bridge/Culvert/Weir
USACE Sims Bayou Rectification
Reach 8a South Post Oak to Bathurst Drive
File No. HSC 409-34
END DESCRIPTION:
XS GIS Cut Line= 6
      3095754.45     13793790.21      3095977.87     13791330.04
      3095743.24     13789743.99      3095754.12     13789415.29
      3095760.31     13789081.68      3095831.56     13787358.72
#Sta/Elev= 30
   597.1   60.24   717.1   57.04  1547.1   55.04  2297.1   55.64  2682.1   58.54
  2787.1   56.04  2949.6   56.25  3638.4   54.09  3841.4   53.55  4022.3   52.89
    4161   51.25  4568.6   49.68  4689.3   47.18  4887.2   47.38 4900.31   50.81
    4944   36.24    4956      36    4980      28    5000   25.27    5020      28
    5044      36    5056   36.24 5101.12   51.28  5367.1   49.54  5437.1   51.24
  5802.1   50.84  5872.1   52.74  6082.1   51.74  6861.3   54.61  7058.1   59.54
#Mann= 11 ,-1 , 0
   597.1     .99       0  2949.6      .1       0  3638.4     .08       0
  3841.4      .1       0  4022.3     .06       0    4161      .1       0
  4568.6     .06       0 4900.31    .035       0 5101.12      .1       0
  6861.3     .08       0  7058.1      .2       0
#XS Ineff= 2 , 0
       0 4900.31      49 5101.12       0   49.05
Permanent Ineff=
       F       F
Bank Sta=4900.31,5101.12
XS Rating Curve= 0 ,0
Exp/Cntr=0.5,0.3