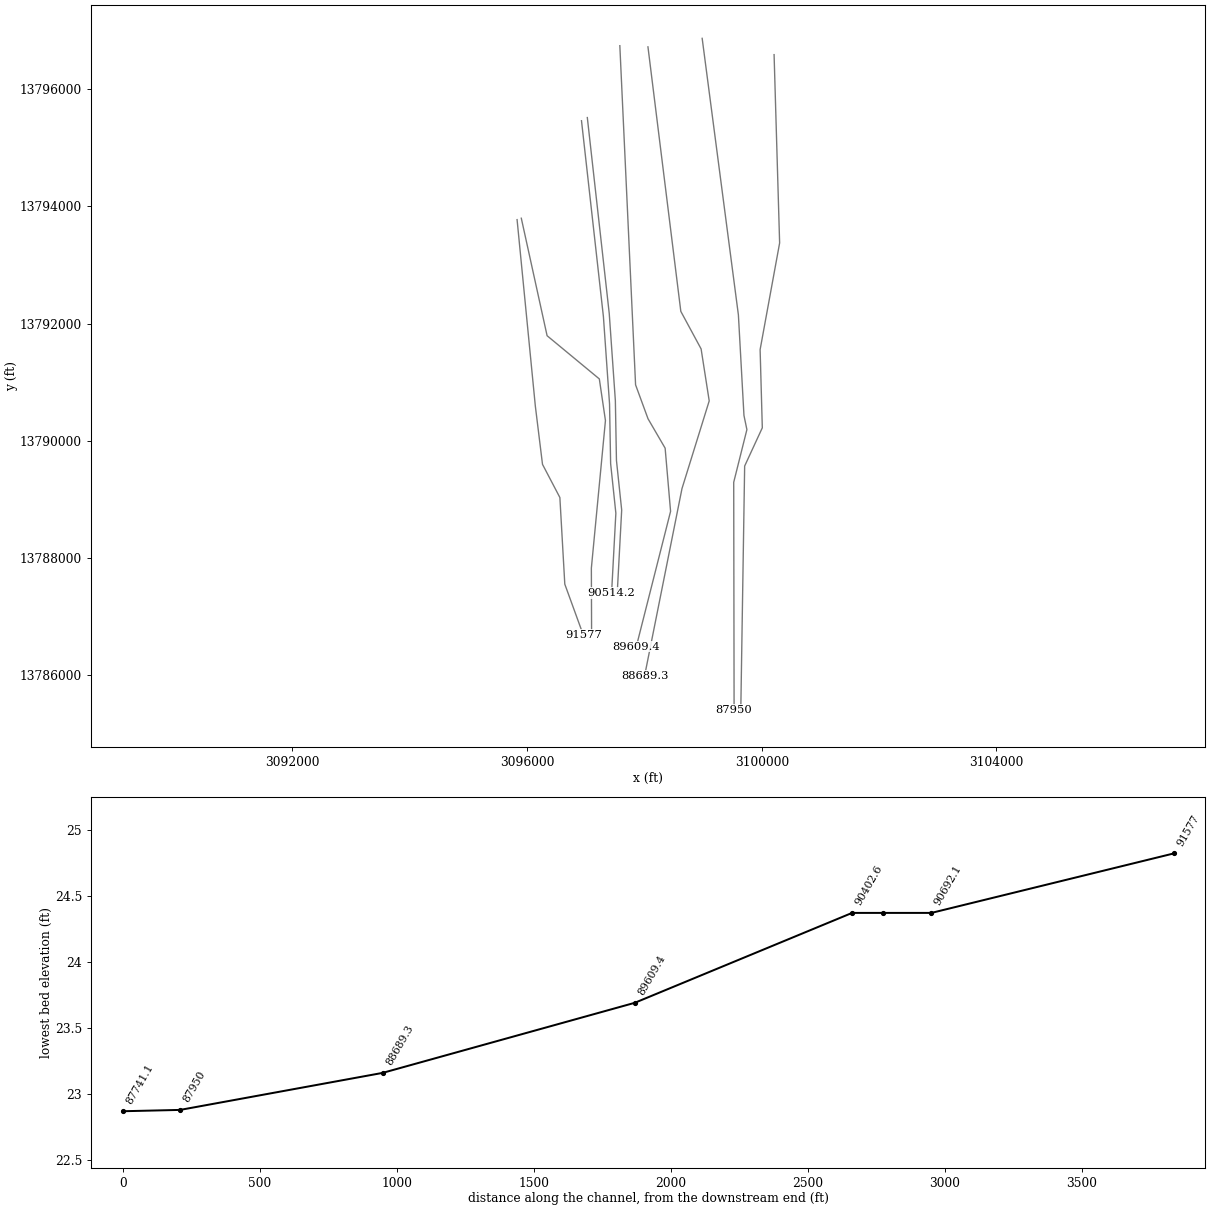
HEC-RAS study C100-00-00.prj: C100-00-00

--- C100-00-00.g01 (geometry) --- (continued)

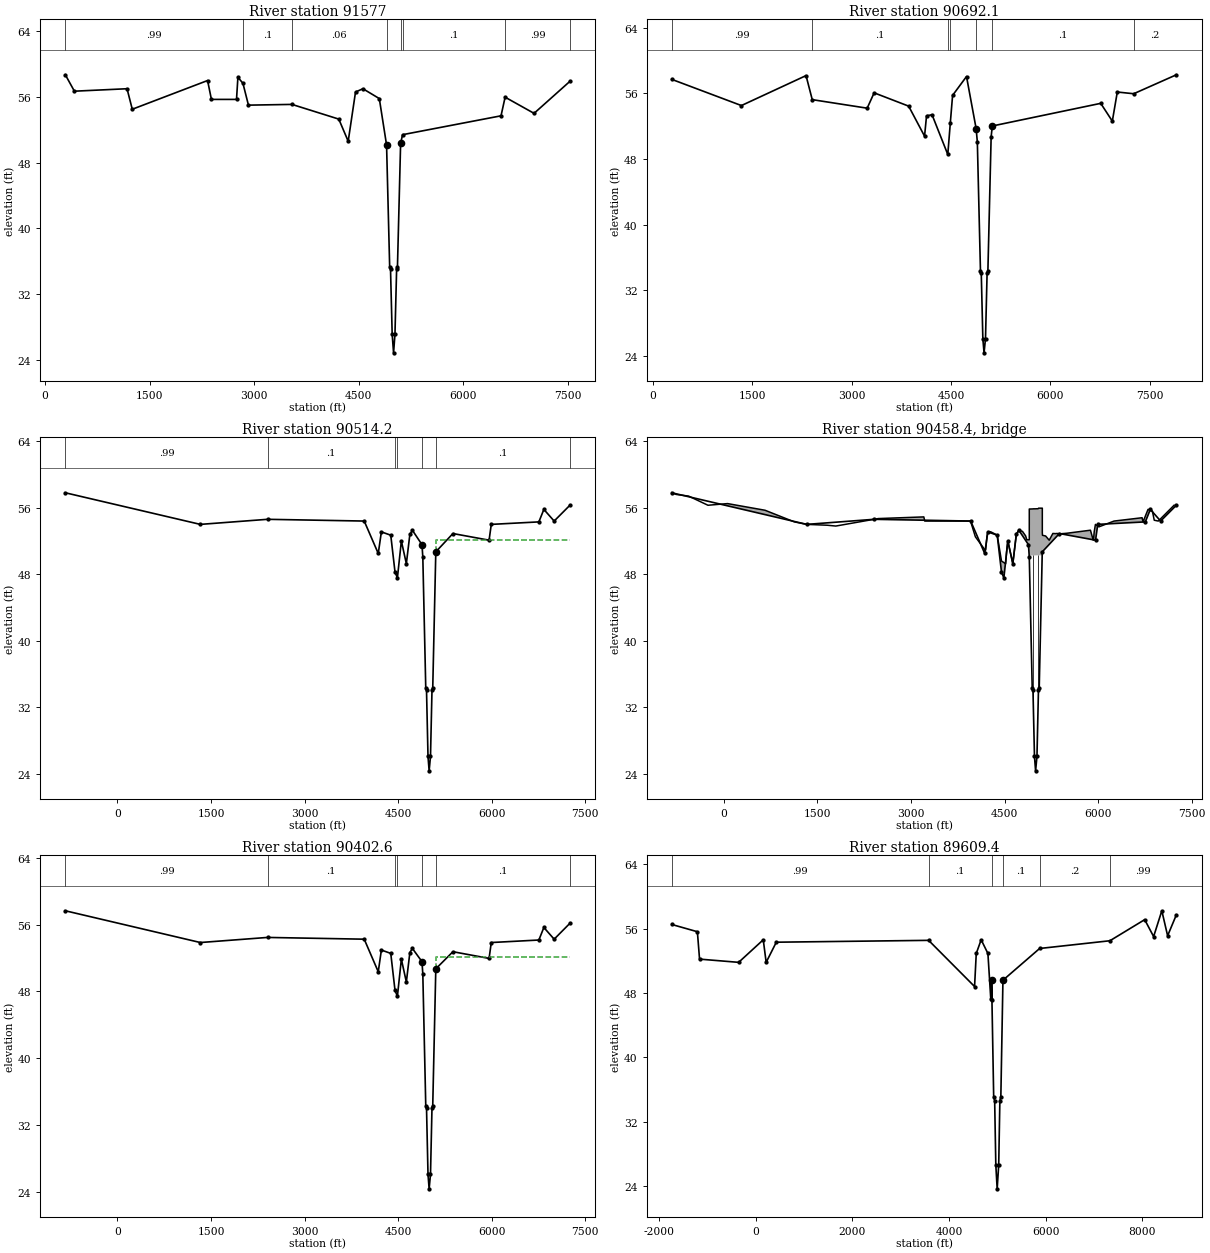
Type RM Length L Ch R = 1 ,91577   ,955.85,884.89,838.9
BEGIN DESCRIPTION:
Cross Section 93521.2
USACE Sims Bayou Rectification
Reach 8a South Post Oak to Bathurst Drive
File No. HSC 409-34
END DESCRIPTION:
XS GIS Cut Line= 6
      3095829.32     13793774.24      3096140.51      13790592.9
      3096262.61      13789599.2      3096558.67      13789033.6
      3096642.63     13787555.51      3096956.36     13786691.64
#Sta/Elev= 30
   292.6    58.7   422.6    56.7  1177.6      57  1252.6    54.5  2332.6      58
  2387.6    55.7  2747.6    55.7  2767.6    58.4  2839.8   57.66  2918.6      55
  3542.8   55.09  4214.3    53.3  4349.3    50.6  4454.3    56.6  4560.5      57
  4795.5    55.8 4899.55   50.15    4944   35.33    4956   35.09    4980   27.09
    5000   24.82    5020   27.09    5044   35.09 5055.87   35.33 5100.99   50.33
  5128.9    51.4    6541    53.7  6599.8   55.97  7014.8      54  7528.9    57.9
#Mann= 8 ,-1 , 0
   292.6     .99       0  2839.8      .1       0  3542.8     .06       0
 4899.55    .035       0 5100.99     .06       0  5128.9      .1       0
  6599.8     .99       0  7528.9      .2       0
Bank Sta=4899.55,5100.99
XS Rating Curve= 0 ,0
Exp/Cntr=0.3,0.1

Type RM Length L Ch R = 1 ,90692.1 ,167.36,177.9,178.88
BEGIN DESCRIPTION:
Cross Section 92650.4 - Interpolated
USACE Sims Bayou Rectification
Reach 8a South Post Oak to Bathurst Drive
File No. HSC 409-34
END DESCRIPTION:
XS GIS Cut Line= 6
       3095901.2      13793798.2      3096340.84     13791793.67
      3097231.03     13791056.72      3097335.41     13790346.51
      3097095.39     13787829.17      3097099.38     13786688.15
#Sta/Elev= 30
   287.8   57.69  1337.8    54.5  2312.8   58.15  2406.4   55.22    3235   54.18
    3340   56.05  3860.6   54.43  4100.6   50.77  4130.6   53.25  4213.5   53.38
  4451.1   48.54  4489.3    52.4  4523.5   55.74  4733.5   58.04  4878.5    51.7
 4896.81   50.07    4944   34.34    4956    34.1    4980    26.1 4998.09   24.37
    5020    26.1    5044    34.1    5056   34.34 5105.07    50.7  5122.7   52.01
  6758.1   54.77  6933.1    52.6  7008.1   56.15  7255.4   55.94  7899.2   58.25
#Mann= 7 ,-1 , 0
   287.8     .99       0  2406.4      .1       0  4451.1     .06       0
  4489.3      .1       0  4878.5    .035       0  5122.7      .1       0
  7255.4      .2       0
Bank Sta=4878.5,5122.7
XS Rating Curve= 0 ,0
Exp/Cntr=0.5,0.3

Type RM Length L Ch R = 1 ,90514.2 ,114.2,111.63,109.77
BEGIN DESCRIPTION:
Upstream Section of Bridge/Culvert/Weir
USACE Sims Bayou Rectification
Reach 8a South Post Oak to Bathurst Drive
File No. HSC 409-34
END DESCRIPTION:
XS GIS Cut Line= 6
      3096927.12     13795461.66       3097300.8     13792118.59
      3097405.13     13790631.37      3097423.71     13789612.01
      3097512.84     13788765.87      3097439.88     13787403.99
#Sta/Elev= 30
  -835.5    57.8  1329.5      54  2406.4   54.61  3957.3    54.4  4182.3    50.5
  4232.3    53.1  4382.8    52.7  4451.1   48.26  4489.3   47.57  4552.8      52
  4632.8   49.28  4689.1    52.8  4730.1   53.29  4883.5   51.56 4896.81   50.07
    4944   34.34    4956    34.1    4980    26.1 4998.09   24.37    5020    26.1
    5044    34.1    5056   34.34 5105.07    50.7  5379.6    52.9  5959.6    52.1
  5994.6      54  6757.8    54.3  6837.8    55.8  7002.8    54.4  7255.4    56.3
#Mann= 7 ,-1 , 0
  -835.5     .99       0  2406.4      .1       0  4451.1     .06       0
  4489.3      .1       0  4883.5    .035       0 5105.07      .1       0
  7255.4      .2       0
#XS Ineff= 2 , 0
       0 4896.81   49.28 5105.07       0    52.1
Permanent Ineff=
       F       F
Bank Sta=4883.5,5105.07
XS Rating Curve= 0 ,0
Exp/Cntr=0.5,0.3

Type RM Length L Ch R = 3 ,90458.4 ,,,
BEGIN DESCRIPTION:
HIRAM CLARKE DRIVE
Structure ID: C00-39
END DESCRIPTION:
Bridge Culvert--1,0,-1,-1, 0
Deck Dist Width WeirC Skew NumUp NumDn MinLoCord MaxHiCord MaxSubmerge Is_Ogee
10,93,2.6,0, 97, 99, , , 0.95, 0, 1,1,,
  -835.5  -765.5  -565.5  -255.5    59.5   659.5  1129.5  1329.5  1654.5  1794.5
  2406.4  2475.8  3205.8  3220.8  3957.3  3960.3  3962.3  4032.3  4182.3  4197.3
  4217.3  4232.3  4277.8  4382.8  4451.1  4462.8  4489.3  4502.8  4517.8  4532.8
  4552.8  4628.3  4632.8  4689.1  4691.4  4730.1  4733.4  4787.6  4788.4  4836.8
  4838.4  4857.6 4857.71  4857.8 4896.69  4896.8 4896.91  4897.1  4901.9  4915.7
  4951.9  4956.5  4959.1  4979.8  4981.4  4983.8  4983.9    4985  4986.8  5014.9
  5035.7 5037.89    5038  5038.1  5044.6 5046.29  5046.4 5084.13 5084.14  5098.4
  5105.9    5106  5108.5  5156.3  5158.4  5214.7  5217.5    5275  5277.1    5317
  5342.6  5377.6  5494.5  5877.6  5922.6  5927.6  5937.6  5957.6  6012.2  6255.8
  6705.8  6720.8  6800.8  6870.8  6900.8  6965.8  7218.4
    57.8    57.6    57.4    56.3    56.5    55.7    54.3      54    53.9    53.8
   54.61    54.7    54.9    54.4    54.4   54.29   54.21   52.51   50.97   50.91
   52.51   53.11   53.11   52.71    49.6   49.54   49.41   49.34   49.26   50.71
   52.01   49.44   49.29   52.81   52.84    53.3   53.29   53.16   53.15   52.63
   52.61   52.15   52.15   52.15   52.15   55.85   55.85   55.85   55.85   55.85
   55.86   55.86   55.87   55.87   55.87   55.87   55.87   55.87   55.87   55.88
   55.88   55.88   55.88   55.88   55.94   55.95   55.95   55.95   55.95   55.95
   55.95   52.96   52.69   52.61   52.61   52.11   52.11   52.91   52.91   52.89
   52.91   52.86   52.93    53.3    52.1    52.2    53.1      54    53.7    54.4
    54.8    54.3    55.8    55.6    54.5    54.4    56.3
                                                                                
                                                                                
                                                                                
                                                                                
                                                                   50.25   50.25
   50.26   50.26   50.27   50.27   50.27   50.27   50.27   50.27   50.27   50.28
   50.28   50.28   50.28   50.28   50.28   50.28   50.28   50.28   50.28   50.28
                                                                                
                                                                                
                                                        
  -835.5  -765.5  -565.5  -255.5    59.5   659.5  1129.5  1329.5  1654.5  1794.5
  2406.4  2475.8  3205.8  3220.8  3957.3  3960.3  3962.3  4032.3  4182.3  4197.3
  4217.3  4232.3  4277.8  4382.8  4451.1  4462.8  4489.3  4502.8  4517.8  4532.8
  4552.8  4628.3  4632.8  4689.1  4691.4  4730.1  4733.4  4787.6  4788.4  4836.8
  4838.4  4894.6 4898.02 4898.03  4901.9  4926.5  4935.9  4938.5  4938.6  4944.7
  4945.3  4959.1  4979.8  4981.4  4983.8  4983.9    4985  4986.8  5014.9  5035.7
 5037.89    5038  5038.1  5044.6 5046.29  5046.4 5046.51 5082.44  5098.3  5098.4
  5105.9    5106 5119.45  5142.9  5145.5  5193.3  5195.4  5251.7  5254.5    5312
  5314.1    5354  5379.6  5414.6  5531.5  5914.6  5959.6  5964.6  5974.6  5994.6
  6049.2  6292.8  6742.8  6757.8  6837.8  6907.8  6937.8  7002.8  7255.4
    57.8    57.6    57.4    56.3    56.5    55.7    54.3      54    53.9    53.8
   54.61    54.7    54.9    54.4    54.4   54.29   54.21   52.51   50.97   50.91
   52.51   53.11   53.11   52.71    49.6   49.54   49.41   49.34   49.26   50.71
   52.01   49.44   49.29   52.81   52.84    53.3   53.29   53.16   53.15   52.63
   52.61   52.15   52.15   55.86   55.86   55.86   55.86   55.86   55.86   55.86
   55.86   55.87   55.87   55.87   55.87   55.87   55.87   55.87   55.88   55.88
   55.88   55.88   55.88   55.94   55.95   55.95   55.95   55.95   55.95   55.95
   55.95    52.5    52.5   52.69   52.69   52.61   52.61   52.11   52.11   52.91
   52.91   52.89   52.91   52.86   52.93    53.3    52.1    52.2    53.1      54
    53.7    54.4    54.8    54.3    55.8    55.6    54.5    54.4    56.3
                                                                                
                                                                                
                                                                                
                                                                                
                                   50.12   50.12   50.12   50.12   50.12   50.12
   50.12   50.13   50.13   50.13   50.13   50.13   50.13   50.13   50.14   50.14
   50.14   50.14   50.14   50.14   50.14   50.14   50.14   50.14   50.14
                                                                                
                                                                                
                                                                        
Pier Skew, UpSta & Num, DnSta & Num=  ,4959.2, 2 ,4959.2, 2 , 0 , 0 , 0 ,,
     1.4     1.4
   35.48   51.26
     1.4     1.4
   35.34   51.12
Pier Skew, UpSta & Num, DnSta & Num=  ,5040.6, 2 ,5040.6, 2 , 0 , 0 , 0 ,,
     1.4     1.4
   35.82   51.27
     1.4     1.4
   35.68   51.13
BR Coef= 1 , 1 , 0 ,1.25, 0 ,,,0.8,0,2,0,
WSPro=,,,, 1 ,,,, 0 ,,,, 0 ,,,,-1 ,-1 ,-1 , 0 , 0 , 0 , 0 , 0
BC Design=,, 0 ,, 0 ,,,,,,
BC HTab HWMax=57.8
BC Use User HTab Curves=0
BC User HTab FreeFlow(D)= 0

Type RM Length L Ch R = 1 ,90402.6 ,745.55,793.22,839.7
BEGIN DESCRIPTION:
Downstream Section of Bridge/Culvert/Weir
USACE Sims Bayou Rectification
Reach 8a South Post Oak to Bathurst Drive
File No. HSC 409-34
END DESCRIPTION:
XS GIS Cut Line= 6
      3097026.43     13795515.58       3097400.1     13792172.51
      3097504.43     13790685.29      3097523.01     13789665.93
      3097612.14     13788819.79      3097539.18     13787457.92
#Sta/Elev= 30
  -835.5   57.65  1329.5   53.85  2406.4   54.46  3957.3   54.25  4182.3   50.35
  4232.3   52.95  4382.8   52.55  4451.1   48.11  4489.3   47.42  4552.8   51.85
  4632.8   49.13  4689.1   52.65  4730.1   53.14  4883.5   51.56 4896.81   50.07
    4944   34.34    4956    34.1    4980    26.1 4998.09   24.37    5020    26.1
    5044    34.1    5056   34.34 5105.07    50.7  5379.6   52.75  5959.6   51.95
  5994.6   53.85  6757.8   54.15  6837.8   55.65  7002.8   54.25  7255.4   56.15
#Mann= 7 ,-1 , 0
  -835.5     .99       0  2406.4      .1       0  4451.1     .06       0
  4489.3      .1       0  4883.5    .035       0 5105.07      .1       0
  7255.4      .2       0
#XS Ineff= 2 , 0
       0 4896.81   49.13 5105.07       0   52.11
Permanent Ineff=
       F       F
Bank Sta=4883.5,5105.07
XS Rating Curve= 0 ,0
Exp/Cntr=0.5,0.3

Type RM Length L Ch R = 1 ,89609.4 ,1011.64,920.08,839.28
BEGIN DESCRIPTION:
Cross Section 91556.8
USACE Sims Bayou Rectification
Reach 8a South Post Oak to Bathurst Drive
File No. HSC 409-34
END DESCRIPTION:
XS GIS Cut Line= 6
      3097580.61     13796741.66      3097848.96     13790955.77
      3098061.06     13790376.91       3098352.7     13789875.37
       3098445.5     13788797.19      3097860.95     13786488.72
#Sta/Elev= 30
 -1743.2    56.5 -1213.2    55.6 -1168.2    52.2  -358.2    51.8   151.8    54.6
   211.8    51.8   421.8    54.3  3577.7   54.53  4529.8    48.8  4564.8    52.9
  4666.3    54.6  4806.3    52.9  4866.3    47.2  4881.3    47.1 4882.41   49.58
    4926   35.05    4946   34.65    4970   26.65    4998   23.69    5030   26.65
    5054   34.65    5074   35.05 5117.59   49.58  5877.7   53.52  7333.9   54.48
  8054.6    57.1  8239.6      55  8409.6    58.2  8529.6    55.1  8710.9    57.7
#Mann= 6 ,-1 , 0
 -1743.2     .99       0  3577.7      .1       0 4882.41    .035       0
 5117.59      .1       0  5877.7      .2       0  7333.9     .99       0
Bank Sta=4882.41,5117.59
XS Rating Curve= 0 ,0
Exp/Cntr=0.3,0.1

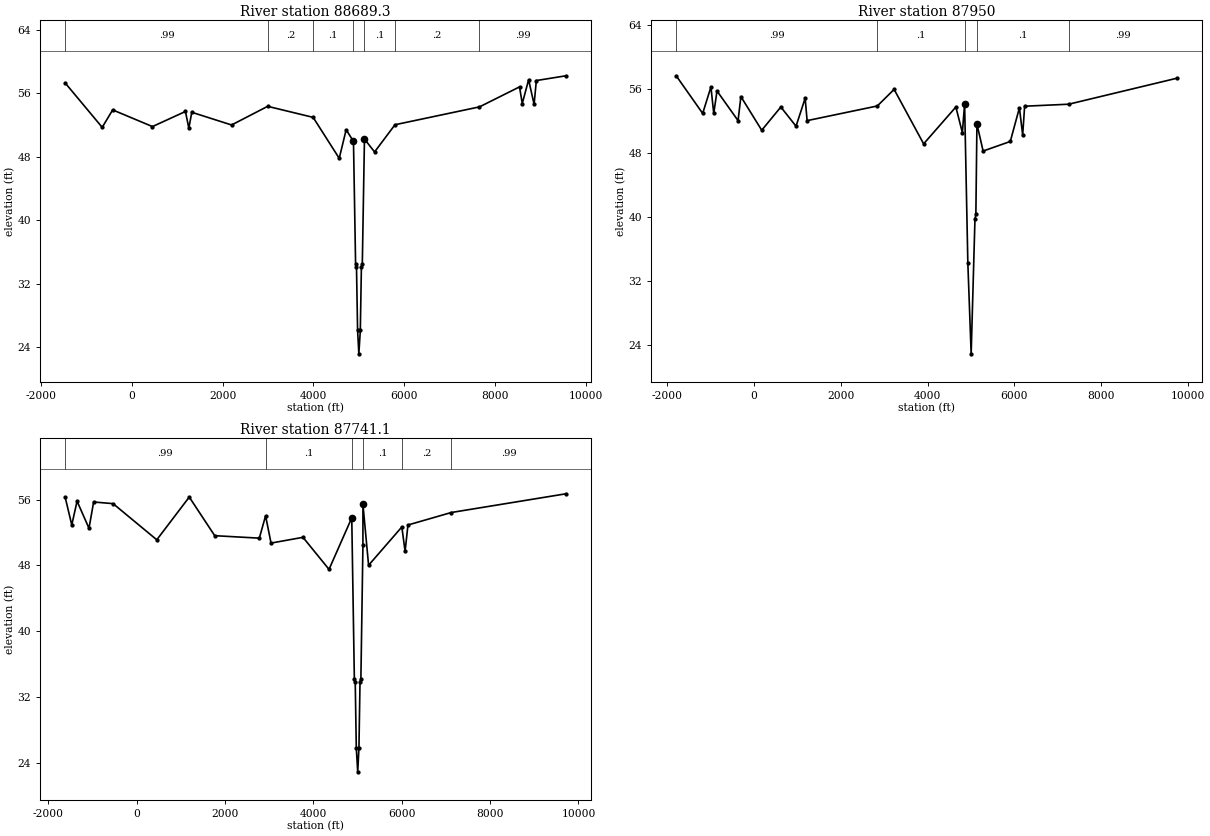
Type RM Length L Ch R = 1 ,88689.3 ,719.04,739.26,726.62
BEGIN DESCRIPTION:
Cross Section 90653.9
USACE Sims Bayou Rectification
Reach 7b Bathurst Drive to Robin Boulevard
File No. HSC 409-33
END DESCRIPTION:
XS GIS Cut Line= 6
      3098059.88     13796721.69      3098619.95     13792209.15
      3098965.83     13791568.36       3099103.9      13790681.8
      3098639.92     13789186.04      3098002.85     13785992.06
#Sta/Elev= 30
 -1460.8    57.3  -645.8    51.7  -415.8    53.9   459.2    51.8  1184.2    53.7
  1259.2    51.6  1324.2    53.6  2199.2      52  2992.4   54.35  3992.4   52.96
  4566.2    47.8  4718.8    51.4 4879.77   49.93    4926   34.52    4946   34.12
    4970   26.12    4998   23.16    5030   26.12    5054   34.12    5074   34.52
 5121.13   50.23  5343.6    48.6  5792.4   52.03  7650.3   54.28  8531.3    56.8
  8591.3    54.7  8731.3    57.7  8851.3    54.6  8901.3    57.6  9553.2    58.2
#Mann= 7 ,-1 , 0
 -1460.8     .99       0  2992.4      .2       0  3992.4      .1       0
 4879.77    .035       0 5121.13      .1       0  5792.4      .2       0
  7650.3     .99       0
Bank Sta=4879.77,5121.13
XS Rating Curve= 0 ,0
Exp/Cntr=0.3,0.1

Type RM Length L Ch R = 1 ,87950   ,267.55,208.86,188.93
BEGIN DESCRIPTION:
Cross Section 89916.0 - Interpolated
USACE Sims Bayou Rectification
Reach 7b Bathurst Drive to Robin Boulevard
File No. HSC 409-33
END DESCRIPTION:
XS GIS Cut Line= 6
      3098983.78     13796867.06      3099601.36     13792147.85
      3099696.17     13790433.35      3099746.11     13790192.01
      3099521.41     13789293.24      3099527.99     13785409.07
#Sta/Elev= 30
 -1790.8    57.6 -1180.8    52.9  -990.8    56.2  -925.8    52.9  -850.8    55.7
  -365.8      52  -300.8      55   179.2    50.8   619.2    53.7   969.2    51.3
  1179.2    54.8  1224.2      52  2841.3   53.83  3227.8    55.9  3907.8    49.1
  4649.9    53.7  4799.9    50.5 4851.26   54.11    4926   34.19  5002.2   22.88
 5089.75   39.68 5110.71   40.31 5135.21   51.59  5277.4    48.2  5903.7    49.4
  6113.7    53.6  6188.7    50.2  6233.7    53.8  7248.7   54.05  9743.7    57.3
#Mann= 5 ,-1 , 0
 -1790.8     .99       0  2841.3      .1       0 4851.26    .035       0
 5135.21      .1       0  7248.7     .99       0
Bank Sta=4851.26,5135.21
XS Rating Curve= 0 ,0
Exp/Cntr=0.5,0.3

Type RM Length L Ch R = 1 ,87741.1 ,57.5,57.52,57.52
BEGIN DESCRIPTION:
Upstream Section of Bridge/Culvert/Weir
USACE Sims Bayou Rectification
Reach 7b Bathurst Drive to Robin Boulevard
File No. HSC 409-33
END DESCRIPTION:
XS GIS Cut Line= 6
      3100209.54     13796589.03      3100304.04     13793375.61
      3099971.47     13791556.59      3100008.92     13790223.07
      3099707.93     13789570.15      3099641.24     13785350.89
#Sta/Elev= 30
 -1622.3   56.31 -1472.3   52.91 -1352.3   55.81 -1082.3   52.51  -977.3   55.71
  -537.3   55.51   452.7   51.11  1187.7   56.31  1764.6   51.61  2774.6   51.31
    2916   54.03  3039.6   50.71  3762.9   51.41  4352.5   47.51 4867.23   53.78
    4926   34.19    4946   33.79    4970   25.79  5002.2   22.87    5030   25.79
 5053.94   33.77    5074   34.19  5120.1   50.43  5120.4   55.43  5248.2   48.01
    6001   52.67  6074.8   49.71  6139.8   52.91  7119.7   54.43  9718.3   56.71
#Mann= 6 ,-1 , 0
 -1622.3     .99       0    2916      .1       0 4867.23    .035       0
  5120.4      .1       0    6001      .2       0  7119.7     .99       0
#XS Ineff= 2 , 0
       0  4872.2   50.31  5128.2       0   50.08
Permanent Ineff=
       F       F
Bank Sta=4867.23,5120.4
XS Rating Curve= 0 ,0
Exp/Cntr=0.5,0.3