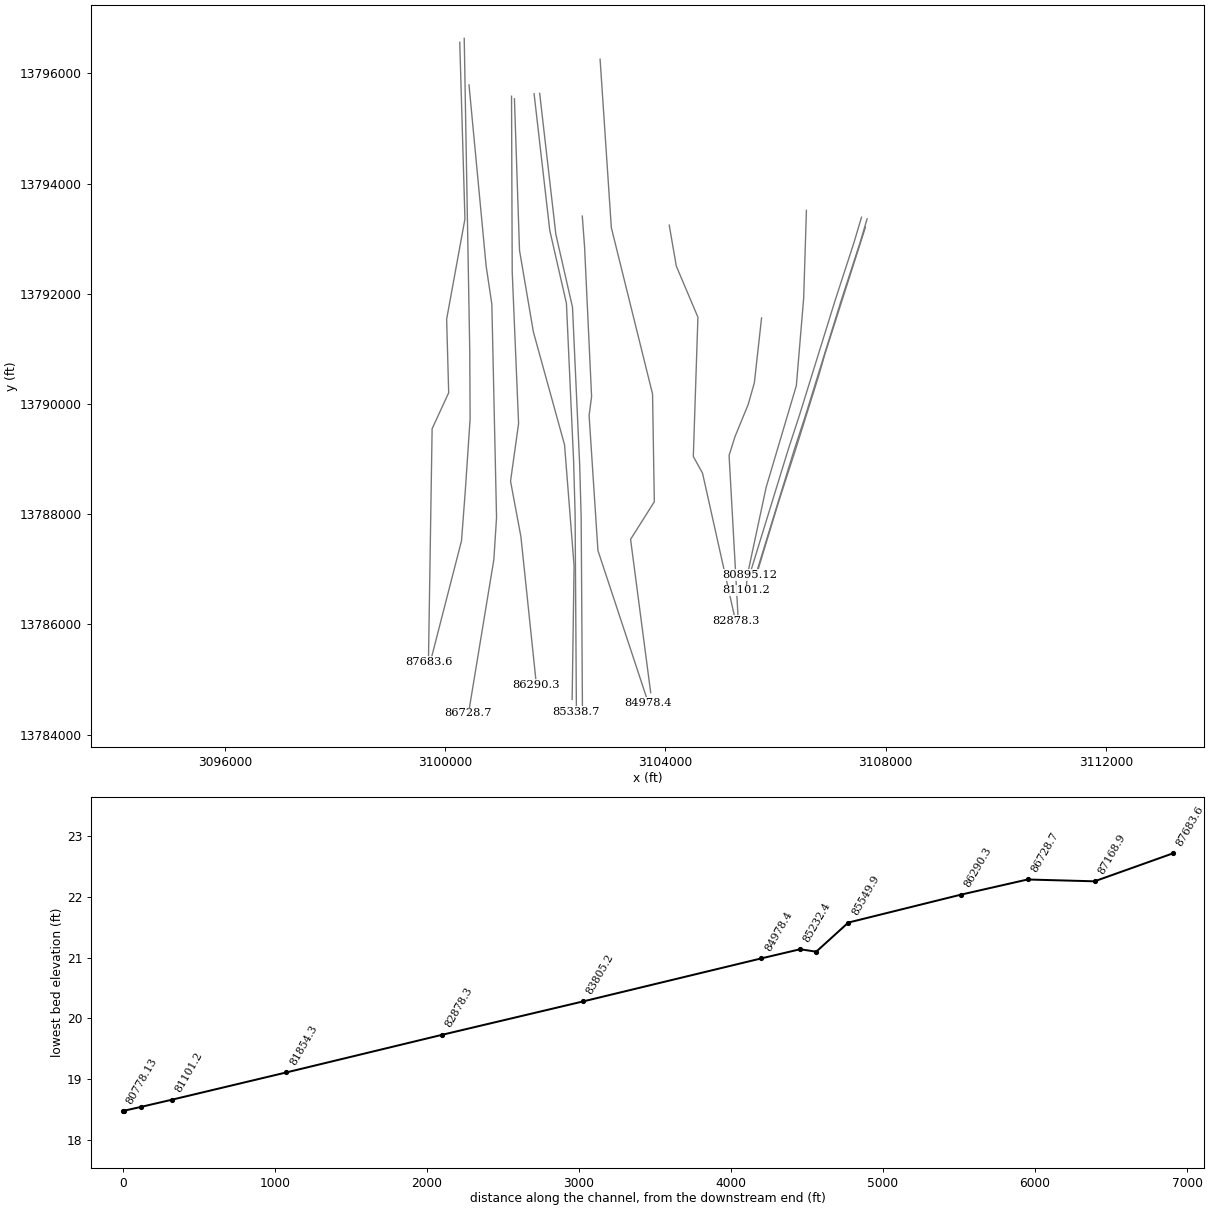
HEC-RAS study C100-00-00.prj: C100-00-00

--- C100-00-00.g01 (geometry) --- (continued)

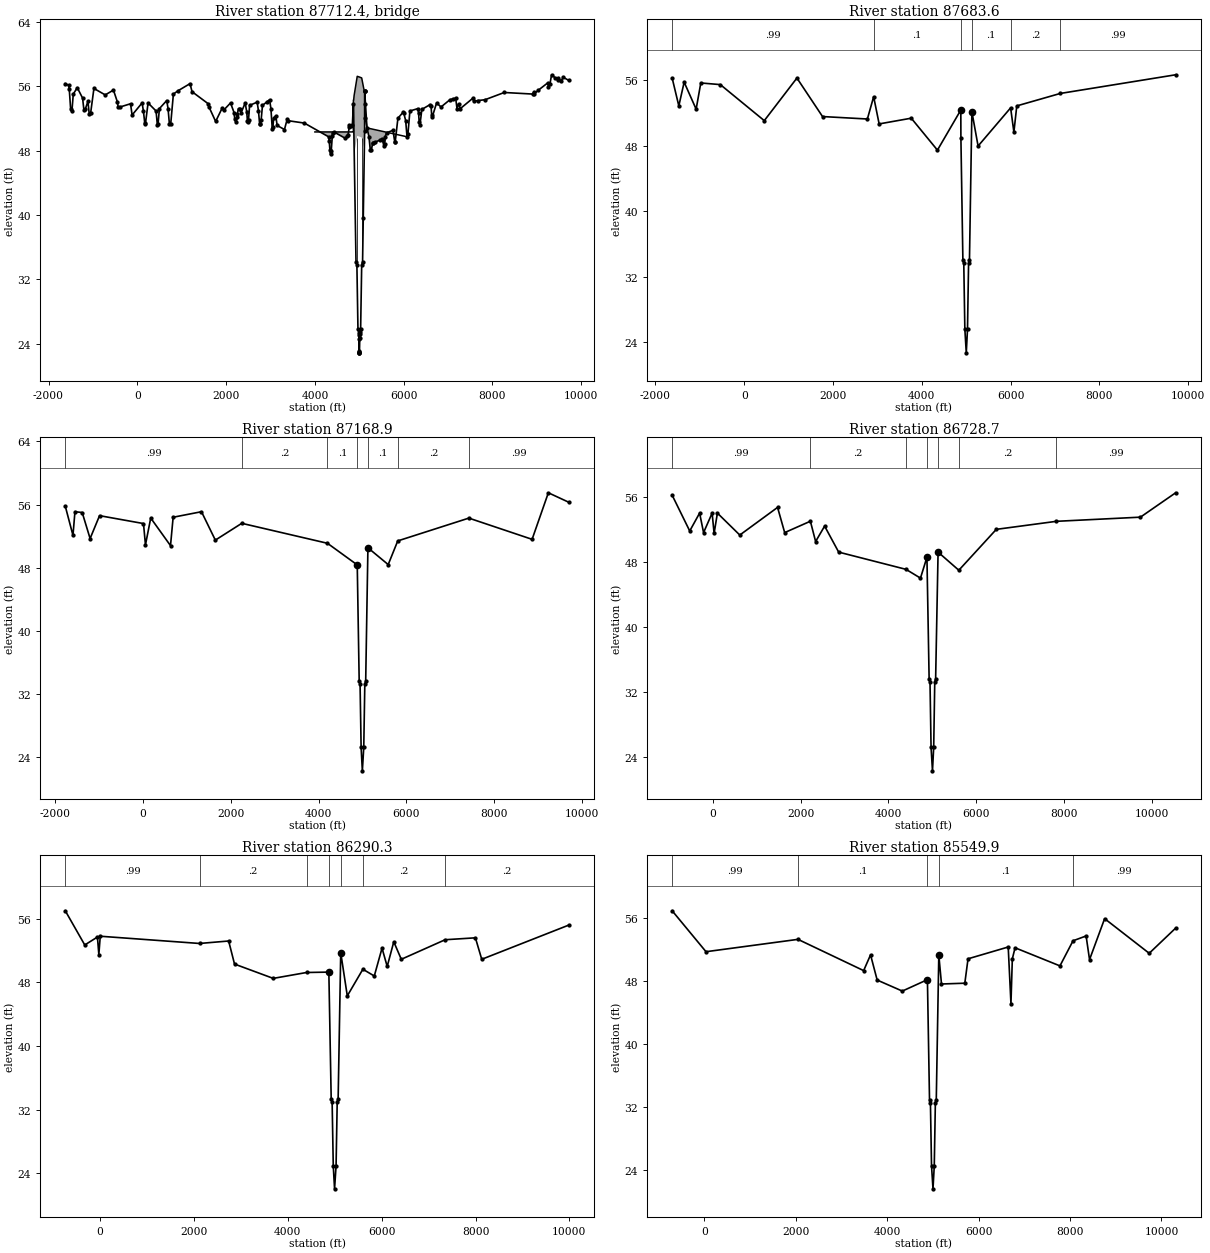
Type RM Length L Ch R = 3 ,87712.4 ,,,
BEGIN DESCRIPTION:
WHITE HEATHER
Structure ID: C00-38
END DESCRIPTION:
Bridge Culvert--1,0,-1,-1, 0
Deck Dist Width WeirC Skew NumUp NumDn MinLoCord MaxHiCord MaxSubmerge Is_Ogee
0.1,43.8,2.6,0, 17, 17, , , 0.95, 0, 1,1,,
    4000 4867.28 4867.29  4867.3  4873.1    4883  4896.2  4953.5  5008.1  5011.7
    5054  5095.3    5133 5133.01  5148.1  5173.2  6074.8
   50.31   50.31   50.31   54.26   54.27   54.82   55.27   57.22   57.12   57.11
   57.02   55.85   54.82   51.67   51.67   50.81   49.71
      42    48.3    48.3   46.86   46.87   47.42   47.87   49.82   49.72   49.71
   49.62   48.45   47.42   51.67   51.67
    4000 4867.28 4867.29  4867.3  4873.1    4883  4896.2  4953.5  5008.1  5011.7
    5054  5095.3    5133 5133.01  5148.1  5173.2  6074.8
   50.31   50.31   50.31   54.26   54.27   54.82   55.27   57.22   57.12   57.11
   57.02   55.85   54.82   51.67   51.67   50.81   49.71
      42    48.3    48.3   46.86   46.87   47.42   47.87   49.82   49.72   49.71
   49.62   48.45   47.42   51.67   51.67
Pier Skew, UpSta & Num, DnSta & Num=  ,4944.4, 2 ,4944.4, 2 , 0 , 0 , 0 ,,
       4       4
      25      50
       4       4
      25      50
Pier Skew, UpSta & Num, DnSta & Num=  ,5054.4, 2 ,5054.4, 2 , 0 , 0 , 0 ,,
       4       4
      25      50
       4       4
      25      50
BR Coef= 1 , 1 , 0 ,1.25, 0 ,,,0.8,0,2,0,
WSPro=,,,, 1 ,,,, 0 ,,,, 0 ,,,,-1 ,-1 ,-1 , 0 , 0 , 0 , 0 , 0
BR U #Sta/Elev= 177
 -1622.3   56.31 -1547.3   56.11 -1532.3   55.61 -1502.3   53.21 -1472.3   52.91
 -1442.3   55.01 -1352.3   55.81 -1232.3   54.51 -1202.3   53.01 -1167.3   53.21
 -1112.3   54.11 -1082.3   52.51 -1052.3   52.61  -977.3   55.71  -722.3   54.91
  -537.3   55.51  -447.3   54.01  -432.3   53.41  -387.3   53.41  -152.3   53.81
  -117.3   52.41   107.7   53.91   137.7   52.91   167.7   51.41   182.7   51.31
   242.7   53.91   422.7   52.91   452.7   51.11   467.7   51.31   497.7   53.21
   662.7   54.21   692.7   53.21   722.7   51.31   752.7   51.31   812.7   55.01
   912.7   55.41  1187.7   56.31  1232.7   55.31  1597.7   53.81  1614.6   53.41
  1764.6   51.61  1914.6   53.31  1944.6   53.01  2099.6   53.91  2179.6   52.71
  2194.6   51.91  2219.6   51.51  2244.6   52.11  2249.6   52.51  2279.6   53.21
  2309.6   53.21  2339.6   52.71  2429.6   53.91  2464.6   52.81  2479.6   51.71
  2494.6   51.51  2504.6   51.81  2529.6   53.61  2699.6   54.01  2729.6   52.91
  2754.6   51.31  2774.6   51.31  2789.6   51.81  2819.6   53.61    2916   54.03
  2979.6   54.31  3009.6   53.21  3039.6   50.71  3054.6   50.91  3069.6   52.01
  3119.6   52.31  3149.6   51.11  3314.6   50.61  3376.7   51.91  3391.7   51.71
  3762.9   51.41  4307.5   49.71  4322.5   49.21  4337.5   48.11  4352.5   47.51
  4367.5   47.91  4392.6   49.83  4397.5   50.21  4427.5   50.31  4687.6   49.51
  4732.9   49.81  4747.6   49.91  4773.5   50.95  4777.6   51.11  4819.4   51.01
  4844.4   51.21 4867.23   53.78    4926   34.19    4946   33.79    4970   25.79
 4987.36   25.38 4989.49   25.14 4991.73   24.56 4996.13    23.1 4996.68   22.98
  4997.4    22.9  5002.2   22.87    5003    22.9 5004.02   23.03 5009.04   24.68
 5011.41   25.21 5013.83   25.44    5030   25.79 5053.94   33.77    5074   34.19
 5089.75   39.68  5120.1   50.43  5120.2    52.1  5120.3   53.76  5120.4   55.43
 5120.49   55.42  5120.6   55.41  5173.2   50.81  5218.2   49.71  5248.2   48.01
  5268.2   48.01  5303.2   48.91  5303.5   48.91  5357.3   49.04  5469.5   49.31
  5519.5   49.41  5523.7    49.3  5554.5   48.51  5569.5   48.81  5584.5   49.71
  5614.8   50.21  5759.8   50.51  5799.8   49.01  5809.8   49.11  5869.8   52.01
  5994.8   52.81    6001   52.67  6044.8   51.71  6074.8   49.71  6094.8   50.01
  6139.8   52.91  6319.3   53.21  6334.3   52.71  6349.3   51.51  6364.3   51.11
  6409.3   53.11  6595.9   53.71  6615.9   53.51  6630.9   52.41  6645.9   52.21
  6740.9   53.91  6840.9   53.41  7040.9   54.31  7119.7   54.43  7170.9   54.51
  7200.9   53.21  7235.9   53.81  7275.9   53.21  7560.9   54.51  7575.9   54.11
  7670.9   54.21  7830.9   54.31  8265.9   55.21  8920.9   55.01  8925.9   55.21
  8930.9   55.01  9035.9   55.51  9245.9   56.41  9260.9   55.91  9295.9   56.31
  9330.9   57.41  9415.9   57.01  9470.9   56.71  9485.9   57.01  9545.9   56.61
  9590.9   57.11  9718.3   56.71
BR U #Mann= 6
 -1622.3     .99    2916      .1 4867.23    .015  5120.4      .1    6001      .2
  7119.7     .99
BR D #Sta/Elev= 174
 -1622.3   56.27 -1547.3   56.07 -1532.3   55.57 -1502.3   53.17 -1472.3   52.87
 -1442.3   54.97 -1352.3   55.77 -1232.3   54.47 -1202.3   52.97 -1167.3   53.17
 -1112.3   54.07 -1082.3   52.47 -1052.3   52.57  -977.3   55.67  -722.3   54.87
  -537.3   55.47  -447.3   53.97  -432.3   53.37  -387.3   53.37  -152.3   53.77
  -117.3   52.37   107.7   53.87   137.7   52.87   167.7   51.37   182.7   51.27
   242.7   53.87   422.7   52.87   452.7   51.07   467.7   51.27   497.7   53.17
   662.7   54.17   692.7   53.17   722.7   51.27   752.7   51.27   812.7   54.97
   912.7   55.37  1187.7   56.27  1232.7   55.27  1597.7   53.77  1614.6   53.37
  1764.6   51.57  1914.6   53.27  1944.6   52.97  2099.6   53.87  2179.6   52.67
  2194.6   51.87  2219.6   51.47  2244.6   52.07  2249.6   52.47  2279.6   53.17
  2309.6   53.17  2339.6   52.67  2429.6   53.87  2464.6   52.77  2479.6   51.67
  2494.6   51.47  2504.6   51.77  2529.6   53.57  2699.6   53.97  2729.6   52.87
  2754.6   51.27  2774.6   51.27  2789.6   51.77  2819.6   53.57    2916   53.99
  2979.6   54.27  3009.6   53.17  3039.6   50.67  3054.6   50.87  3069.6   51.97
  3119.6   52.27  3149.6   51.07  3314.6   50.57  3376.7   51.87  3391.7   51.67
  3762.9   51.37  4307.5   49.67  4322.5   49.17  4337.5   48.07  4352.5   47.47
  4367.5   47.87  4392.6   49.79  4397.5   50.17  4427.5   50.27  4687.6   49.47
  4732.9   49.77  4747.6   49.87  4773.5   50.91  4777.6   51.07  4819.4   50.97
  4844.4   51.17  4869.4   50.67 4879.11   52.36  4879.2   52.37 4881.07   49.01
    4926   34.03    4946   33.63    4970   25.63 4987.36   25.23 4990.38   24.81
 4991.73    24.4 4996.13   22.95 4996.68   22.83  4997.8   22.73  5002.2   22.72
 5003.38   22.78 5004.28   22.94 5008.83   24.44 5011.41   25.05 5013.83   25.28
    5030   25.63    5054   33.63    5074   34.03 5128.39   52.16  5173.2   50.77
  5218.2   49.67  5248.2   47.97  5268.2   47.97  5303.2   48.87  5303.5   48.87
  5357.3      49  5469.5   49.27  5519.5   49.37  5523.7   49.26  5554.5   48.47
  5569.5   48.77  5584.5   49.67  5614.8   50.17  5759.8   50.47  5799.8   48.97
  5809.8   49.07  5869.8   51.97  5994.8   52.77    6001   52.63  6044.8   51.67
  6074.8   49.67  6094.8   49.97  6139.8   52.87  6319.3   53.17  6334.3   52.67
  6349.3   51.47  6364.3   51.07  6409.3   53.07  6595.9   53.67  6615.9   53.47
  6630.9   52.37  6645.9   52.17  6740.9   53.87  6840.9   53.37  7040.9   54.27
  7119.7   54.39  7170.9   54.47  7200.9   53.17  7235.9   53.77  7275.9   53.17
  7560.9   54.47  7575.9   54.07  7670.9   54.17  7830.9   54.27  8265.9   55.17
  8920.9   54.97  8925.9   55.17  8930.9   54.97  9035.9   55.47  9245.9   56.37
  9260.9   55.87  9295.9   56.27  9330.9   57.37  9415.9   56.97  9470.9   56.67
  9485.9   56.97  9545.9   56.57  9590.9   57.07  9718.3   56.67
BR D #Mann= 6
 -1622.3     .99    2916      .1  4879.2    .015 5128.39      .1    6001      .2
  7119.7     .99
BC Design=,, 0 ,, 0 ,,,,,,
BC HTab HWMax=57.41
BC Use User HTab Curves=0
BC User HTab FreeFlow(D)= 0

Type RM Length L Ch R = 1 ,87683.6 ,455.72,514.71,575.96
BEGIN DESCRIPTION:
Downstream Section of Bridge/Culvert/Weir
USACE Sims Bayou Rectification
Reach 7b Bathurst Drive to Robin Boulevard
File No. HSC 409-33
END DESCRIPTION:
XS GIS Cut Line= 6
      3100264.48      13796561.1      3100358.72     13793356.29
      3100026.15     13791537.27       3100063.6     13790203.75
      3099762.61     13789550.83      3099695.73     13785322.96
#Sta/Elev= 30
 -1622.3   56.27 -1472.3   52.87 -1352.3   55.77 -1082.3   52.47  -977.3   55.67
  -537.3   55.47   452.7   51.07  1187.7   56.27  1764.6   51.57  2774.6   51.27
    2916   53.99  3039.6   50.67  3762.9   51.37  4352.5   47.47  4879.2   52.37
 4881.07   49.01    4926   34.03    4946   33.63    4970   25.63  5002.2   22.72
    5030   25.63    5054   33.63    5074   34.03 5128.39   52.16  5268.2   47.97
    6001   52.63  6074.8   49.67  6139.8   52.87  7119.7   54.39  9718.3   56.67
#Mann= 6 ,-1 , 0
 -1622.3     .99       0    2916      .1       0  4879.2    .035       0
 5128.39      .1       0    6001      .2       0  7119.7     .99       0
#XS Ineff= 2 , 0
       0  4879.2   49.81  5128.2       0   50.08
Permanent Ineff=
       F       F
Bank Sta=4879.2,5128.39
XS Rating Curve= 0 ,0
Exp/Cntr=0.5,0.3

Type RM Length L Ch R = 1 ,87168.9 ,438.78,440.21,445.2
BEGIN DESCRIPTION:
Cross Section 89118.6
USACE Sims Bayou Rectification
Reach 7b Bathurst Drive to Robin Boulevard
File No. HSC 409-33
END DESCRIPTION:
XS GIS Cut Line= 6
     3100345.767    13796633.725      3100446.27      13790952.6
      3100452.55     13789727.89      3100364.63     13788418.39
      3100296.49     13787518.45      3099713.63    13785254.255
#Sta/Elev= 30
 -1763.5    55.8 -1588.5    52.1 -1543.5    55.1 -1378.5      55 -1198.5    51.7
  -983.5    54.6    16.5    53.6    61.5    50.9   181.5    54.3   631.5    50.8
   691.5    54.4  1336.5    55.1    1652    51.5  2253.5   53.63  4203.5    51.1
 4881.78   48.36    4926   33.62    4946   33.22    4970   25.22    4998   22.26
    5030   25.22    5054   33.22    5074   33.62 5124.74   50.53  5586.4    48.4
  5803.5    51.4  7422.2   54.29  8861.4    51.6  9231.4    57.5  9696.2    56.3
#Mann= 7 ,-1 , 0
 -1763.5     .99       0  2253.5      .2       0  4203.5      .1       0
 4881.78    .035       0 5124.74      .1       0  5803.5      .2       0
  7422.2     .99       0
Bank Sta=4881.78,5124.74
XS Rating Curve= 0 ,0
Exp/Cntr=0.3,0.1

Type RM Length L Ch R = 1 ,86728.7 ,438.35,438.4,433.99
BEGIN DESCRIPTION:
Cross Section 88679.1
USACE Sims Bayou Rectification
Reach 7b Bathurst Drive to Robin Boulevard
File No. HSC 409-33
END DESCRIPTION:
XS GIS Cut Line= 6
     3100432.563    13795788.499      3100743.87     13792501.31
      3100847.36     13791811.41      3100932.74     13787941.31
      3100883.72     13787175.62     3100423.315    13784386.554
#Sta/Elev= 30
  -925.2    56.2  -525.2    51.8  -300.2      54  -210.2    51.6   -15.2      54
    29.8    51.5   104.8      54   614.8    51.3  1474.8    54.7  1636.8    51.6
  2222.2      53  2341.3    50.5  2546.3    52.4  2866.3    49.2  4399.2   47.08
  4728.9      46    4876   48.57    4926   33.59    4946   33.19    4970   25.19
 5002.24   22.29    5030   25.19    5054   33.19    5074   33.59 5129.84    49.2
  5602.2   46.97  6455.6      52  7826.1   52.99  9737.3    53.5 10539.5    56.5
#Mann= 7 ,-1 , 0
  -925.2     .99       0  2222.2      .2       0  4399.2      .1       0
    4876    .035       0 5129.84      .1       0  5602.2      .2       0
  7826.1     .99       0
Bank Sta=4876,5129.84
XS Rating Curve= 0 ,0
Exp/Cntr=0.3,0.1

Type RM Length L Ch R = 1 ,86290.3 ,693.97,740.39,760.09
BEGIN DESCRIPTION:
Cross Section 88239.9
USACE Sims Bayou Rectification
Reach 7b Bathurst Drive to Robin Boulevard
File No. HSC 409-33
END DESCRIPTION:
XS GIS Cut Line= 6
      3101205.03     13795583.45      3101217.49     13792399.21
      3101333.28     13789644.72      3101187.02     13788599.59
      3101375.16     13787593.34      3101656.86     13784904.13
#Sta/Elev= 30
  -738.5      57  -323.5    52.7   -53.5    53.7   -23.5    51.5     6.5    53.8
  2120.9   52.89  2741.7    53.2  2866.7    50.3  3691.7    48.5  4400.9   49.24
    4876   49.29    4926   33.35    4946   32.95    4970   24.95  4997.8   22.04
    5030   24.95    5054   32.95    5074   33.35 5129.13   51.73    5269    46.3
  5600.9   49.65    5844    48.8    6009    52.3    6119      50  6259.3    53.1
  6419.3    50.9  7353.5   53.36    7998    53.6    8133    50.9  9986.9    55.2
#Mann= 7 ,-1 , 0
  -738.5     .99       0  2120.9      .2       0  4400.9      .1       0
    4876    .035       0 5129.13      .1       0  5600.9      .2       0
  7353.5      .2       0
Bank Sta=4876,5129.13
XS Rating Curve= 0 ,0
Exp/Cntr=0.3,0.1

Type RM Length L Ch R = 1 ,85549.9 ,253.66,211.18,196.16
BEGIN DESCRIPTION:
Cross Section 87491.0 - Interpolated
USACE Sims Bayou Rectification
Reach 7b Bathurst Drive to Robin Boulevard
File No. HSC 409-33
END DESCRIPTION:
XS GIS Cut Line= 6
     3101257.892    13795535.591      3101350.02     13792786.94
       3101601.9     13791307.15      3102167.79     13789259.95
      3102341.18     13787060.05     3102305.973    13784638.921
#Sta/Elev= 30
  -702.8    56.9    37.2    51.7  2049.2   53.27  3485.2    49.3  3636.3    51.3
  3781.3    48.1  4331.3    46.7 4880.24   48.15    4926    32.9    4946    32.5
    4970    24.5  5002.2   21.58    5030    24.5    5054    32.5    5074    32.9
 5129.13   51.28  5188.1    47.6  5698.1    47.7  5768.6    50.8  6647.4    52.3
  6707.4    45.1  6737.4    50.8  6797.4    52.2  7778.8    49.9  8065.3   53.09
  8351.2    53.7  8426.2    50.7  8756.2    55.9  9731.2    51.5 10309.8    54.7
#Mann= 5 ,-1 , 0
  -702.8     .99       0  2049.2      .1       0 4880.24    .035       0
 5129.13      .1       0  8065.3     .99       0
Bank Sta=4880.24,5129.13
XS Rating Curve= 0 ,0
Exp/Cntr=0.5,0.3

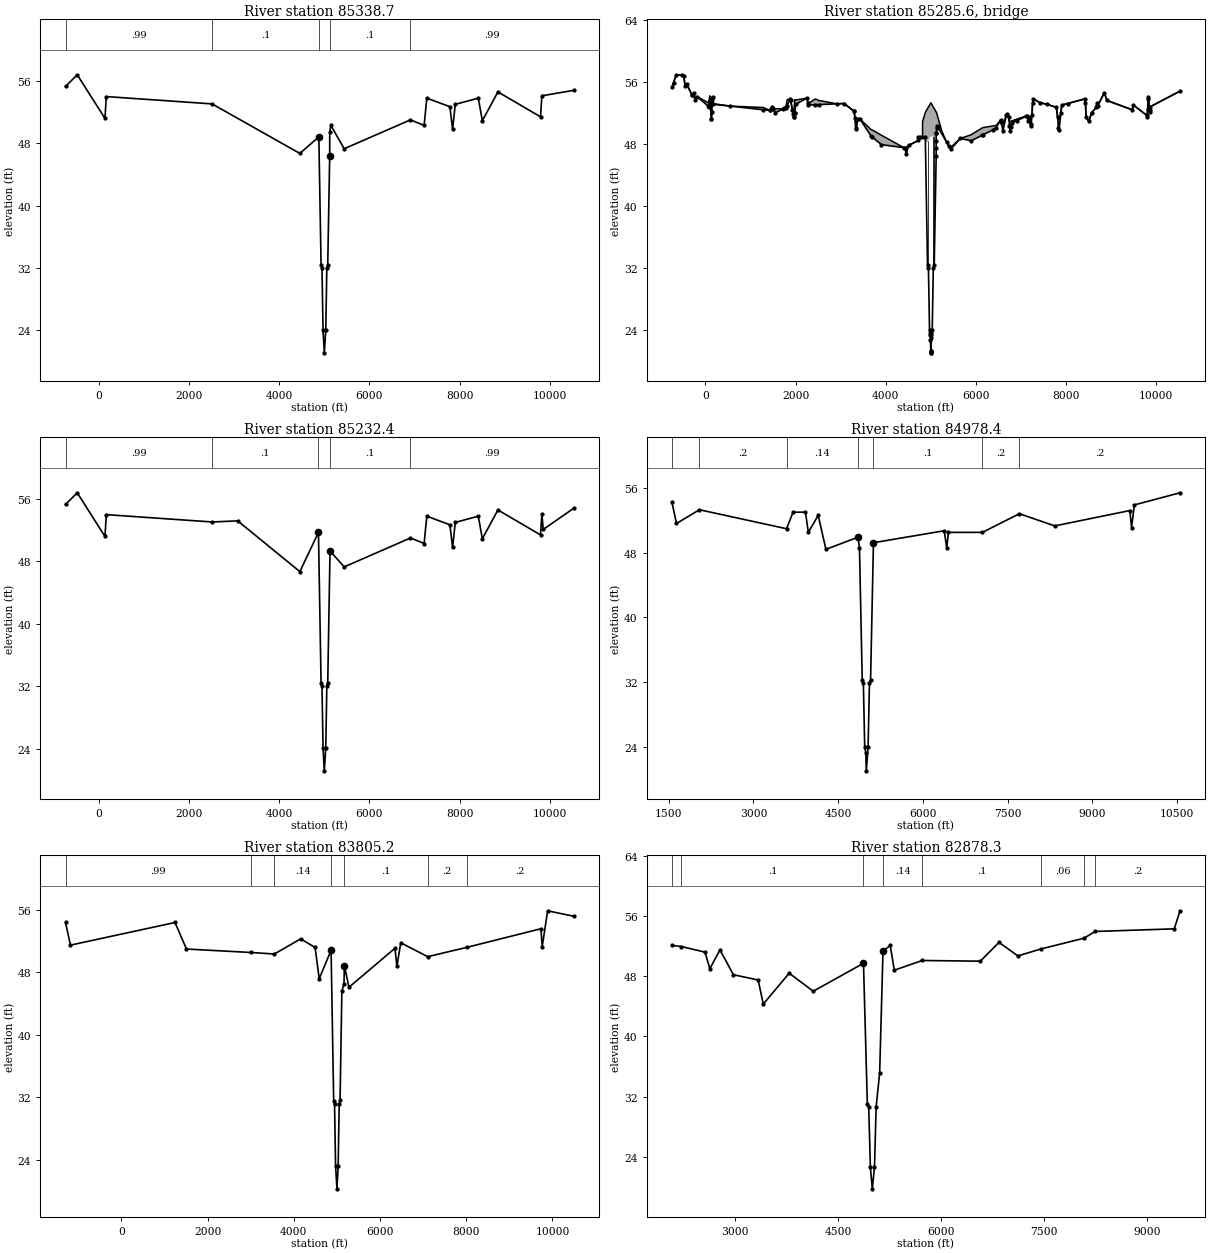
Type RM Length L Ch R = 1 ,85338.7 ,108.32,106.39,106.32
BEGIN DESCRIPTION:
Upstream Section of Bridge/Culvert/Weir
USACE Sims Bayou Rectification
Reach 7b Bathurst Drive to Robin Boulevard
File No. HSC 409-33
END DESCRIPTION:
XS GIS Cut Line= 6
      3101614.82     13795628.18       3101899.4     13793150.45
      3102202.09     13791826.28      3102332.39     13788970.09
      3102359.76     13788009.43     3102383.521    13784415.907
#Sta/Elev= 30
  -741.4   55.31  -481.3   56.81   133.7   51.21   163.7   54.01    2509   53.07
  4455.3   46.71 4876.71   48.84    4926   32.41    4946   32.01 4970.02   24.01
 4997.86    21.1    5030   24.01    5054   32.01    5074   32.41  5117.6   46.43
  5117.9   49.43  5143.9   50.31  5438.9   47.31    6909   51.02  7211.3   50.31
  7271.3   53.81  7782.5   52.71  7842.5   49.81  7902.5   53.01  8412.7   53.81
  8502.7   50.91  8847.7   54.61  9792.7   51.41  9822.7   54.11 10525.1   54.81
#Mann= 5 ,-1 , 0
  -741.4     .99       0    2509      .1       0 4876.71    .035       0
  5117.6      .1       0    6909     .99       0
#XS Ineff= 2 , 0
       0  4872.4   47.52    5128       0   47.56
Permanent Ineff=
       F       F
Bank Sta=4876.71,5117.6
XS Rating Curve= 0 ,0
Exp/Cntr=0.5,0.3

Type RM Length L Ch R = 3 ,85285.6 ,,,
BEGIN DESCRIPTION:
BUFFALO SPEEDWAY
Structure ID: C00-37
END DESCRIPTION:
Bridge Culvert--1,0,-1,-1, 0
Deck Dist Width WeirC Skew NumUp NumDn MinLoCord MaxHiCord MaxSubmerge Is_Ogee
5,94,2.6,0, 140, 140, , , 0.95, 0, 1,1,,
  -741.4  -706.4  -646.3  -511.4  -481.3  -451.3  -416.3  -301.4  -296.3  -251.3
  -231.3  -186.3    68.6    73.7    98.6   103.7   108.6   133.6   133.7   138.6
   148.6   148.7   153.6   163.7   178.7   543.6  1283.6  1433.6  1433.7  1473.7
  1498.6  1548.7  1723.6  1753.6  1778.6  1793.7  1813.6  1883.7  1888.6  1929.8
  1944.8  1960.7  1964.8  1979.8  1980.7  2005.7  2250.7  2274.8  2285.7  2439.8
    2509  2919.8  3077.8  3288.1  3297.8  3317.8  3332.8  3347.8  3377.8  3428.2
  3674.7  3698.4  3904.7  4399.9  4420.3  4455.3  4505.3  4724.9  4741.3    4760
  4815.9    4816    4876    4879    50005120.126    5123    5127    5266    5266
  5352.7  5397.7  5438.9  5653.9  5893.9  6135.8  6147.6  6374.1  6449.1  6549.1
  6557.6  6599.1  6674.1  6698.5  6728.5  6743.5  6758.5  6778.5  6788.5    6909
  7108.6  7136.3  7151.3  7181.3  7211.3  7226.3  7241.3  7256.3  7271.3  7421.3
  7577.5  7782.5  7812.5  7827.5  7842.5  7883.6  7902.5  8032.7  8412.7  8427.7
  8442.7  8502.7  8562.7  8667.7  8682.7  8697.7  8847.7  8902.7  9462.7  9492.7
  9782.7  9792.7  9807.7  9817.7  9822.7  9842.7  9852.7  9862.7  9867.7 10525.1
    55.3    55.9   56.91   56.83   56.81   55.51   55.71   54.37   54.31   54.61
   53.71   54.11    53.3   53.45    54.2      54    53.8    51.5    51.5   52.06
   53.79   53.81   53.88   54.01   53.19   52.88    52.7   52.31   52.31   52.81
    52.7   52.54   52.51    52.6   52.67   53.02    53.7   53.81   53.66   52.37
   51.91    52.3    52.5    53.7    53.7   53.66   53.91   53.29   53.24    53.8
   53.61   53.17   53.21   52.25   52.21   51.31    50.6   50.57   51.21   51.21
   49.85    49.8   49.12   47.53   47.52   47.55   47.81   48.46   48.51   48.92
   48.92    50.9   52.03   52.09    53.3   52.09   52.09  52.009    49.2   49.35
   48.19   47.73   47.55   48.71   49.19   50.06    50.1   50.32   50.39   51.11
   50.87   50.58   51.71   51.81   51.41   50.87    50.9   50.94   50.96    51.2
    51.6   51.61   51.57   51.55   51.53   51.52   51.71   53.31   53.81   53.31
   53.11   52.71   51.41   51.14   51.13      52      53    53.2    53.8    53.3
    51.5    50.9      52    52.7    53.3    52.9    54.6    53.6    52.4      53
    51.7    51.4    52.5    53.8    54.1    52.5    52.1    52.4    52.8    54.8
                                                                                
                                                                                
                                                                                
                                                                                
                                                                                
                                                                                
                                                                                
           47.77   47.77  47.799   48.98  48.815
                                                                                
                                                                                
                                                                                
                                                                                
                                                                                
                                                                                
  -741.4  -706.4  -646.3  -511.4  -481.3  -451.3  -416.3  -301.4  -296.3  -251.3
  -231.3  -186.3    68.6    73.7    98.6   103.7   108.6   133.6   133.7   138.6
   148.6   148.7   153.6   163.7   178.7   543.6  1283.6  1433.6  1433.7  1473.7
  1498.6  1548.7  1723.6  1753.6  1778.6  1793.7  1813.6  1883.7  1888.6  1929.8
  1944.8  1960.7  1964.8  1979.8  1980.7  2005.7  2250.7  2274.8  2285.7  2439.8
    2509  2919.8  3077.8  3288.1  3297.8  3317.8  3332.8  3347.8  3377.8  3428.2
  3674.7  3698.4  3904.7  4399.9  4420.3  4455.3  4505.3  4724.9  4741.3    4760
  4815.9    4816    4876    4879    50005120.126    5123    5127    5266    5266
  5352.7  5397.7  5438.9  5653.9  5893.9  6135.8  6147.6  6374.1  6449.1  6549.1
  6557.6  6599.1  6674.1  6698.5  6728.5  6743.5  6758.5  6778.5  6788.5    6909
  7108.6  7136.3  7151.3  7181.3  7211.3  7226.3  7241.3  7256.3  7271.3  7421.3
  7577.5  7782.5  7812.5  7827.5  7842.5  7883.6  7902.5  8032.7  8412.7  8427.7
  8442.7  8502.7  8562.7  8667.7  8682.7  8697.7  8847.7  8902.7  9462.7  9492.7
  9782.7  9792.7  9807.7  9817.7  9822.7  9842.7  9852.7  9862.7  9867.7 10525.1
    55.3    55.9   56.91   56.83   56.81   55.51   55.71   54.37   54.31   54.61
   53.71   54.11    53.3   53.45    54.2      54    53.8    51.5    51.5   52.06
   53.79   53.81   53.88   54.01   53.19   52.88    52.7   52.31   52.31   52.81
    52.7   52.54   52.51    52.6   52.67   53.02    53.7   53.81   53.66   52.37
   51.91    52.3    52.5    53.7    53.7   53.66   53.91   53.29   53.24    53.8
   53.61   53.17   53.21   52.25   52.21   51.31    50.6   50.57   51.21   51.21
   49.85    49.8   49.12   47.53   47.52   47.55   47.81   48.46   48.51   48.92
   48.92    50.9   52.03   52.09    53.3   52.09   52.09  52.009    49.2   49.35
   48.19   47.73   47.55   48.71   49.19   50.06    50.1   50.32   50.39   51.11
   50.87   50.58   51.71   51.81   51.41   50.87    50.9   50.94   50.96    51.2
    51.6   51.61   51.57   51.55   51.53   51.52   51.71   53.31   53.81   53.31
   53.11   52.71   51.41   51.14   51.13      52      53    53.2    53.8    53.3
    51.5    50.9      52    52.7    53.3    52.9    54.6    53.6    52.4      53
    51.7    51.4    52.5    53.8    54.1    52.5    52.1    52.4    52.8    54.8
                                                                                
                                                                                
                                                                                
                                                                                
                                                                                
                                                                                
                                                                                
           47.77   47.77  47.799   48.98  48.815
                                                                                
                                                                                
                                                                                
                                                                                
                                                                                
                                                                                
Pier Skew, UpSta & Num, DnSta & Num=  ,4874, 2 ,4874, 2 , 0 , 0 , 0 ,,
       4       4
      45      49
       4       4
      45      49
Pier Skew, UpSta & Num, DnSta & Num=  ,4942, 2 ,4942, 2 , 0 , 0 , 0 ,,
       4       4
      32      50
       4       4
      32      50
Pier Skew, UpSta & Num, DnSta & Num=  ,5058, 2 ,5058, 2 , 0 , 0 , 0 ,,
       4       4
      32      50
       4       4
      32      50
Pier Skew, UpSta & Num, DnSta & Num=  ,5127, 2 ,5127, 2 , 0 , 0 , 0 ,,
       4       4
      45      49
       4       4
      45      49
BR Coef= 1 , 1 , 0 ,1.25, 0 ,,,0.8,0,2,0,
WSPro=,,,, 1 ,,,, 0 ,,,, 0 ,,,,-1 ,-1 ,-1 , 0 , 0 , 0 , 0 , 0
BR U #Sta/Elev= 159
  -741.4   55.31  -706.4    55.9  -646.3   56.91  -511.4   56.83  -481.3   56.81
  -451.3   55.51  -416.3   55.71  -301.4   54.37  -296.3   54.31  -251.3   54.61
  -231.3   53.71  -186.3   54.11    68.6   52.84    73.7   52.81    98.6   53.23
   103.7   53.31   108.6   52.97   133.6   51.22   133.7   51.21   138.6   52.06
   148.6   53.79   148.7   53.81   153.6   53.88   163.7   54.01   178.7   53.11
   543.6   52.88  1283.6   52.41  1433.6   52.31  1433.7   52.31  1473.7   52.81
  1498.6   52.54  1548.7   52.01  1723.6   52.51  1753.6    52.6  1778.6   52.67
  1793.7   52.71  1813.6   52.95  1883.7   53.81  1888.6   53.66  1929.8   52.37
  1944.8   51.91  1960.7   51.41  1964.8   51.53  1979.8   51.98  1980.7   52.01
  2005.7   53.11  2250.7   53.91  2274.8   53.29  2285.7   53.01  2439.8   53.05
    2509   53.07  2919.8   53.17  3077.8   53.21  3288.1   52.25  3297.8   52.21
  3317.8   51.31  3332.8   50.01  3347.8   49.91  3377.8   51.21  3428.2   51.21
  3674.7   49.01  3698.4    48.9  3904.7   47.91  4399.9   47.53  4420.3   47.51
  4455.3   46.71  4505.3   47.81 4724.87   48.46 4724.88   48.84    4760   48.84
    4813   48.84 4876.71   48.84    4926   32.41    4946   32.01 4970.02   24.01
 4985.88   23.68 4989.16   23.36 4991.39   22.79 4995.79   21.33 4996.68   21.16
 4997.86    21.1 5001.86    21.1 5003.03   21.16 5003.93   21.32 5009.17   23.06
 5011.08   23.43 5013.51   23.66    5030   24.01    5054   32.01    5074   32.41
  5117.6   46.43  5117.7   47.43  5117.8   48.43  5117.9   49.43 5117.99   49.43
  5118.1   49.44  5137.7    50.1  5143.9   50.31  5157.7   50.17  5352.7   48.19
  5397.7   47.73  5438.9   47.31  5653.9   48.71  5893.9   48.41  6135.8   49.11
  6147.6   49.14  6374.1   49.81  6449.1   50.11  6549.1   51.11  6557.6   50.87
  6599.1   49.71  6674.1   51.71  6698.5   51.81  6728.5   51.41  6743.5   50.31
  6758.5   49.71  6778.5   50.21  6788.5   50.71    6909   51.02  7108.6   51.54
  7136.3   51.61  7151.3   51.01  7181.3   51.31  7211.3   50.31  7226.3   50.61
  7241.3   51.71  7256.3   53.31  7271.3   53.81  7421.3   53.31  7577.5   53.11
  7782.5   52.71  7812.5   51.41  7827.5   50.01  7842.5   49.81  7883.6      52
  7902.5   53.01  8032.7   53.21  8412.7   53.81  8427.7   53.31  8442.7   51.51
  8502.7   50.91  8562.7   52.01  8667.7   52.71  8682.7   53.31  8697.7   52.91
  8847.7   54.61  8902.7   53.61  9462.7   52.41  9492.7   53.01  9782.7   51.71
  9792.7   51.41  9807.7   52.51  9817.7   53.81  9822.7   54.11  9842.7   52.51
  9852.7   52.11  9862.7   52.41  9867.7   52.81 10525.1   54.81
BR U #Mann= 9
  -741.4     .99    2509      .1 4876.71    .035    4926    .015    4946    .035
    5054    .015    5074    .035  5117.6      .1    6909     .99
BR D #Sta/Elev= 153
  -741.4   55.27  -706.4   55.86  -646.3   56.87  -511.4   56.79  -481.3   56.77
  -451.3   55.47  -416.3   55.67  -301.4   54.33  -296.3   54.27  -251.3   54.57
  -231.3   53.67  -186.3   54.07    68.6    52.8    73.7   52.77    98.6   53.19
   103.7   53.27   108.6   52.93   133.6   51.18   133.7   51.17   138.6   52.02
   148.6   53.75   148.7   53.77   153.6   53.84   163.7   53.97   178.7   53.07
   543.6   52.84  1283.6   52.37  1433.6   52.27  1433.7   52.27  1473.7   52.77
  1498.6    52.5  1548.7   51.97  1723.6   52.47  1753.6   52.56  1778.6   52.63
  1793.7   52.67  1813.6   52.91  1883.7   53.77  1888.6   53.62  1929.8   52.33
  1944.8   51.87  1960.7   51.37  1964.8   51.49  1979.8   51.94  1980.7   51.97
  2005.7   53.07  2250.7   53.87  2274.8   53.25  2285.7   52.97  2439.8   53.01
    2509   53.03  2919.8   53.13  3077.8   53.17  3288.1   52.21  3297.8   52.17
  3317.8   51.27  3332.8   49.97  3347.8   49.87  3377.8   51.17  3428.2   51.17
  3674.7   48.97  3698.4   48.86  3904.7   47.87  4399.9   47.49  4420.3   47.47
  4455.3   46.67  4505.3   47.77  4724.9   48.42  4741.3   48.47  4786.2   51.69
 4868.25   51.69    4926   32.44    4946   32.04    4970   24.04 4985.83   23.71
 4988.12   23.54 4991.39   22.82 4995.79   21.36 4996.68    21.2 4997.45   21.14
 5001.86   21.14 5003.03   21.19 5003.93   21.35 5008.48   22.86 5011.09   23.46
 5013.52   23.69    5030   24.04    5054   32.04    5074   32.44 5124.64   49.32
  5137.7   50.06  5143.9   50.27  5157.7   50.13  5352.7   48.15  5397.7   47.69
  5438.9   47.27  5653.9   48.67  5893.9   48.37  6135.8   49.07  6147.6    49.1
  6374.1   49.77  6449.1   50.07  6549.1   51.07  6557.6   50.83  6599.1   49.67
  6674.1   51.67  6698.5   51.77  6728.5   51.37  6743.5   50.27  6758.5   49.67
  6778.5   50.17  6788.5   50.67    6909   50.98  7108.6    51.5  7136.3   51.57
  7151.3   50.97  7181.3   51.27  7211.3   50.27  7226.3   50.57  7241.3   51.67
  7256.3   53.27  7271.3   53.77  7421.3   53.27  7577.5   53.07  7782.5   52.67
  7812.5   51.37  7827.5   49.97  7842.5   49.77  7883.6   51.96  7902.5   52.97
  8032.7   53.17  8412.7   53.77  8427.7   53.27  8442.7   51.47  8502.7   50.87
  8562.7   51.97  8667.7   52.67  8682.7   53.27  8697.7   52.87  8847.7   54.57
  8902.7   53.57  9462.7   52.37  9492.7   52.97  9782.7   51.67  9792.7   51.37
  9807.7   52.47  9817.7   53.77  9822.7   54.07  9842.7   52.47  9852.7   52.07
  9862.7   52.37  9867.7   52.77 10525.1   54.77
BR D #Mann= 9
  -741.4     .99    2509      .1 4868.25    .035    4926    .015    4946    .035
    5054    .015    5074    .035 5124.64      .1    6909     .99
BC Design=,, 0 ,, 0 ,,,,,,
BC HTab HWMax=56.91
BC Use User HTab Curves=0
BC User HTab FreeFlow(D)= 0

Type RM Length L Ch R = 1 ,85232.4 ,281.29,253.93,228.01
BEGIN DESCRIPTION:
Downstream Section of Bridge/Culvert/Weir
USACE Sims Bayou Rectification
Reach 7b Bathurst Drive to Robin Boulevard
File No. HSC 409-33
END DESCRIPTION:
XS GIS Cut Line= 6
     3101716.135    13795635.852      3102009.72     13793079.79
      3102312.41     13791755.62      3102442.71     13788899.43
      3102470.08     13787938.77      3102493.32    13784424.092
#Sta/Elev= 30
  -741.4   55.27  -481.3   56.77   133.7   51.17   163.7   53.97    2509   53.03
  3077.8   53.17  4455.3   46.67 4868.25   51.69    4926   32.44    4946   32.04
    4970   24.04 4997.45   21.14    5030   24.04    5054   32.04    5074   32.44
 5124.64   49.32  5438.9   47.27    6909   50.98  7211.3   50.27  7271.3   53.77
  7782.5   52.67  7842.5   49.77  7902.5   52.97  8412.7   53.77  8502.7   50.87
  8847.7   54.57  9792.7   51.37  9822.7   54.07  9852.7   52.07 10525.1   54.77
#Mann= 5 ,-1 , 0
  -741.4     .99       0    2509      .1       0 4868.25    .035       0
 5124.64      .1       0    6909     .99       0
#XS Ineff= 2 , 0
       0  4872.4   47.52    5128       0   47.52
Permanent Ineff=
       F       F
Bank Sta=4868.25,5124.64
XS Rating Curve= 0 ,0
Exp/Cntr=0.5,0.3

Type RM Length L Ch R = 1 ,84978.4 ,1143.64,1173.23,1193.08
BEGIN DESCRIPTION:
Cross Section 86837.0
USACE Sims Bayou Rectification
Reach 7b Bathurst Drive to Robin Boulevard
File No. HSC 409-33
END DESCRIPTION:
XS GIS Cut Line= 6
      3102490.14    13793408.772      3102531.67     13792853.39
      3102659.14     13790135.47      3102614.07       13789791.
      3102774.69     13787340.92     3103690.368    13784574.594
#Sta/Elev= 30
  1557.7    54.2  1637.7    51.6  2044.2    53.3  3586.4   50.95  3701.5      53
  3921.5      53  3971.5    50.5  4146.5    52.6  4283.3    48.4  4851.6    49.9
    4877   48.62    4926   32.29    4946   31.89    4970   23.89 4989.29   23.24
 4997.62   20.99    5030   23.89    5054   31.89    5074   32.29 5124.79   49.22
  6377.3    50.7  6422.3    48.6  6452.3    50.5  7054.2    50.5  7708.7   52.81
  8334.3    51.3  9664.3    53.2  9694.3    51.1  9744.3    53.9 10552.3    55.4
#Mann= 7 ,-1 , 0
  1557.7      .2       0  2044.2      .2       0  3586.4     .14       0
  4851.6    .035       0 5124.79      .1       0  7054.2      .2       0
  7708.7      .2       0
Bank Sta=4851.6,5124.79
XS Rating Curve= 0 ,0
Exp/Cntr=0.3,0.1

Type RM Length L Ch R = 1 ,83805.2 ,926.62,926.86,979.87
BEGIN DESCRIPTION:
Cross Section 85636.0
USACE Sims Bayou Rectification
Reach 7b Bathurst Drive to Robin Boulevard
File No. HSC 409-33
END DESCRIPTION:
XS GIS Cut Line= 6
     3102813.702    13796254.808      3103017.75     13793199.24
      3103766.57     13790180.54      3103798.77     13788226.43
      3103367.38     13787543.94     3103732.672    13784763.514
#Sta/Elev= 30
 -1293.6    54.4 -1178.6    51.5  1246.4    54.4  1511.4      51    3000   50.56
  3549.1   50.36  4160.2    52.3  4495.2    51.2  4590.2    47.2    4866   50.84
    4926   31.59    4946   31.19    4970   23.19 5002.07   20.28    5030   23.19
    5054   31.19 5074.13   31.63    5116   45.59 5165.83   46.58 5173.86   48.88
  5279.8    46.1  6347.2    51.1  6392.2    48.8  6482.2    51.8  7105.9   50.02
  8011.3   51.21  9732.4    53.6  9762.4    51.3  9887.4    55.9 10489.2    55.2
#Mann= 7 ,-1 , 0
 -1293.6     .99       0    3000      .1       0  3549.1     .14       0
    4866    .035       0 5165.83      .1       0  7105.9      .2       0
  8011.3      .2       0
Bank Sta=4866,5173.86
XS Rating Curve= 0 ,0
Exp/Cntr=0.3,0.1

Type RM Length L Ch R = 1 ,82878.3 ,1054.7,1024.03,981.89
BEGIN DESCRIPTION:
Cross Section 84649.3
USACE Sims Bayou Rectification
Reach 7b Bathurst Drive to Robin Boulevard
File No. HSC 409-33
END DESCRIPTION:
XS GIS Cut Line= 6
     3104069.716    13793244.079      3104197.96     13792501.65
      3104590.71     13791574.49      3104507.01     13789047.35
      3104674.41     13788744.73     3105274.154    13786062.318
#Sta/Elev= 30
  2083.9    52.1  2219.9   51.95  2564.5    51.2  2634.5      49  2782.4    51.5
  2977.4    48.2  3337.4    47.5  3412.4    44.3  3789.3    48.4  4139.3      46
 4869.92   49.72    4926   31.03    4946   30.63    4970   22.63 4997.92   19.73
    5030   22.63    5054   30.63 5104.99   35.11 5153.58    51.3  5258.6    52.1
  5318.6    48.8  5724.3   50.09  6570.1      50    6841    52.5    7116    50.7
  7454.5   51.63  8077.1   53.05  8240.1   53.95    9391    54.3  9474.5    56.7
#Mann= 8 ,-1 , 0
  2083.9     .99       0  2219.9      .1       0 4869.92    .035       0
 5153.58     .14       0  5724.3      .1       0  7454.5     .06       0
  8077.1      .1       0  8240.1      .2       0
Bank Sta=4869.92,5153.58
XS Rating Curve= 0 ,0
Exp/Cntr=0.3,0.1

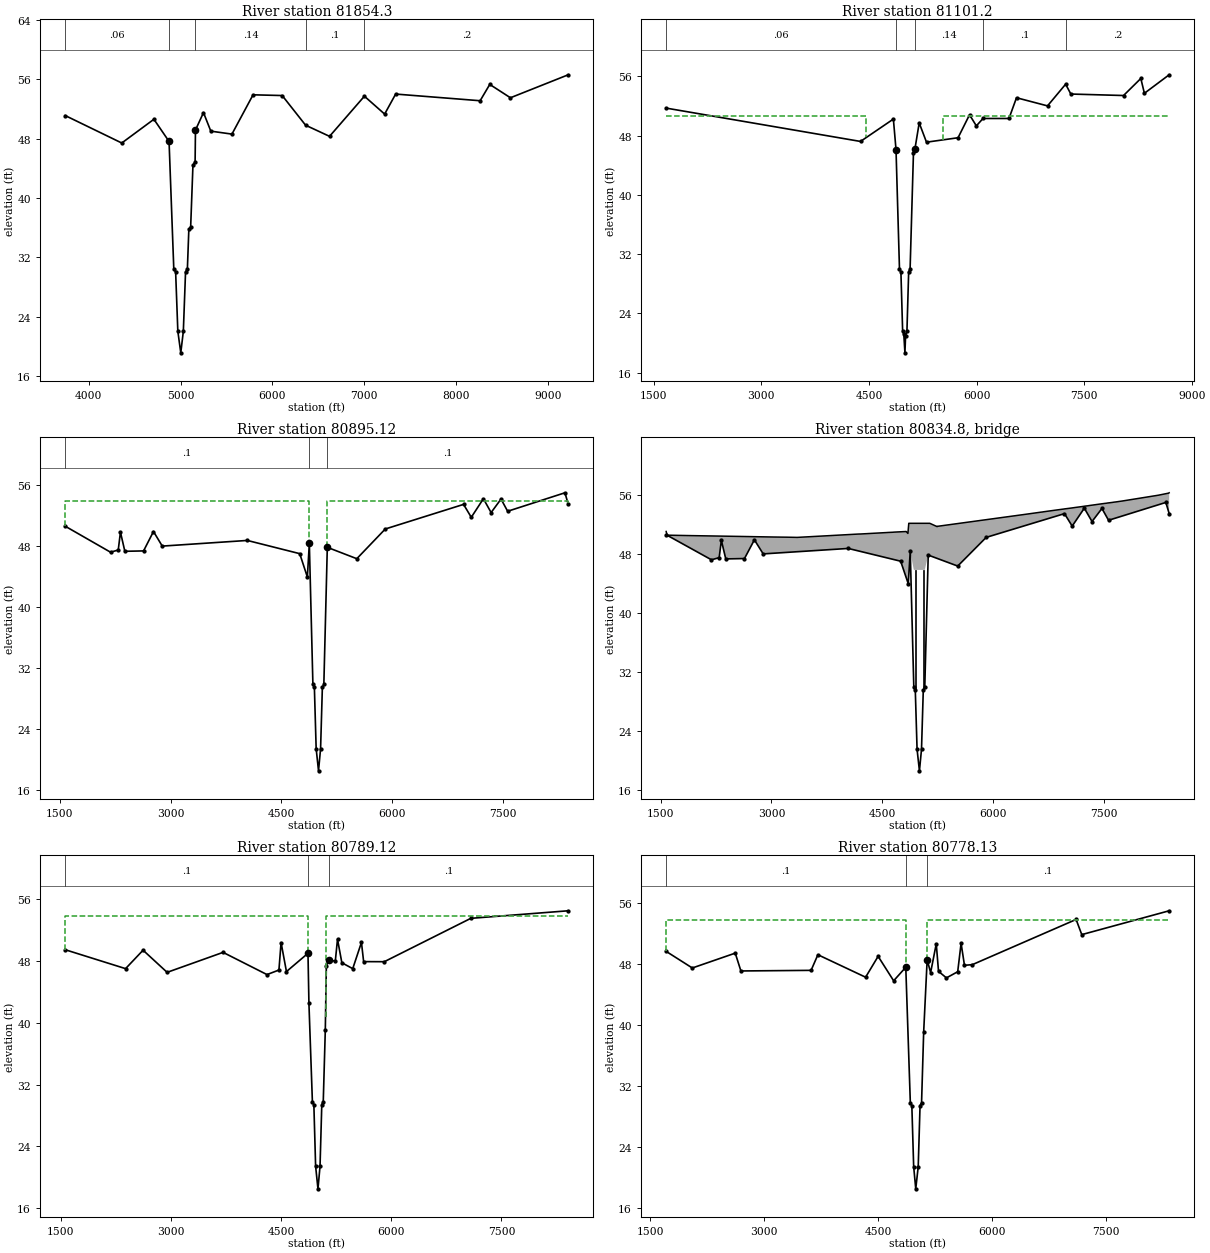
Type RM Length L Ch R = 1 ,81854.3 ,760.9,753.09,754.03
BEGIN DESCRIPTION:
Cross Section 83638.5
USACE Sims Bayou Rectification
Reach 7b Bathurst Drive to Robin Boulevard
File No. HSC 409-33
END DESCRIPTION:
XS GIS Cut Line= 6
     3105746.746    13791561.044      3105616.12     13790386.17
      3105503.95     13789990.89      3105263.57     13789405.98
      3105156.74     13789066.79     3105317.822    13786174.248
#Sta/Elev= 30
  3743.9    51.1  4359.4    47.4  4709.4    50.6 4874.43   47.61    4926   30.42
    4946   30.02    4970   22.02 5002.15   19.11    5030   22.02    5054   30.02
    5074   30.42 5089.84   35.74 5109.84   36.14  5134.7   44.43 5158.16   44.89
    5162   49.14  5249.3    51.5  5329.3      49  5559.3    48.6  5789.3    53.9
  6106.7    53.8  6361.5    49.8  6622.3    48.3  7001.8   53.71  7222.3    51.3
  7342.3      54  8262.3    53.1  8367.3    55.3  8592.3    53.5    9222    56.6
#Mann= 5 ,-1 , 0
  3743.9     .06       0 4874.43    .035       0    5162     .14       0
  6361.5      .1       0  7001.8      .2       0
Bank Sta=4874.43,5162
XS Rating Curve= 0 ,0
Exp/Cntr=0.3,0.1

Type RM Length L Ch R = 1 ,81101.2 ,209.87,206.11,202.54
BEGIN DESCRIPTION:
Cross Section 82886.0 - Interpolated
USACE Sims Bayou Rectification
Reach 7b Bathurst Drive to Robin Boulevard
File No. HSC 409-33
END DESCRIPTION:
XS GIS Cut Line= 6
     3106561.546    13793513.319      3106511.85     13791922.98
      3106378.69     13790333.49      3105829.45     13788486.01
      3105487.11     13786886.37      3105466.26    13786623.402
#Sta/Elev= 30
    1673    51.7  4382.6    47.2    4841   50.22 4877.71    46.1 4926.05   29.98
 4946.05   29.58 4970.05   21.58 4985.96   21.24    5002   18.66 5011.24   20.99
 5030.05   21.58 5054.05   29.58 5074.05   29.98 5120.89    45.6    5142   46.22
    5201    49.7  5302.8    47.1  5742.8    47.7  5902.8    50.8  5997.8    49.3
  6090.9    50.3  6452.8    50.3  6557.8    53.1  6990.2      52  7242.9   54.93
  7315.2    53.6  8050.2    53.4    8291    55.7    8341    53.7  8686.3    56.2
#Mann= 5 ,-1 , 0
    1673     .06       0 4877.71    .035       0    5142     .14       0
  6090.9      .1       0  7242.9      .2       0
#XS Ineff= 2 , 0
       0    4465    50.6  5532.3       0    50.6
Permanent Ineff=
       F       F
Bank Sta=4877.71,5142
XS Rating Curve= 0 ,0
Exp/Cntr=0.5,0.3

Type RM Length L Ch R = 1 ,80895.12,105.89,106,105.97
BEGIN DESCRIPTION:
USACE Sims Bayou Rectification
Reach 7b Bathurst Drive to Robin Boulevard
File No. HSC 409-33
END DESCRIPTION:
XS GIS Cut Line= 6
     3107562.253    13793388.224     3107423.411    13792922.434
     3107077.251    13791860.844     3106441.411    13789816.314
     3106229.451    13789168.474     3105529.058     13786895.78
#Sta/Elev= 30
 1576.32   50.56  2188.9   47.16 2293.11   47.45 2322.89   49.79 2382.44   47.28
 2635.54   47.33 2769.54   49.87 2888.64   47.96 4038.93    48.7 4747.94   46.97
 4851.13   43.91 4877.71   48.31 4926.05   29.86 4946.05   29.46 4970.05   21.46
    5002   18.54 5030.05   21.46 5054.05   29.46 5074.05   29.86 5120.89    47.8
 5519.83   46.31  5905.1    50.2 6963.88   53.42 7068.24   51.73  7232.2   54.16
 7336.54   52.35 7470.69   54.12 7560.12   52.52 8335.19   54.94 8379.91   53.43
#Mann= 3 ,-1 , 0
 1576.32      .1       0 4877.71    .035       0 5120.89      .1       0
#XS Ineff= 2 , 0
       0 4877.71    53.8 5120.89       0    53.8
Permanent Ineff=
       F       F
Bank Sta=4877.71,5120.89
XS Rating Curve= 0 ,0
Exp/Cntr=0.5,0.3

Type RM Length L Ch R = 3 ,80834.8 ,,,
BEGIN DESCRIPTION:
ALMEDA ROAD
END DESCRIPTION:
Bridge Culvert--1,0,-1,-1, 0
Deck Dist Width WeirC Skew NumUp NumDn MinLoCord MaxHiCord MaxSubmerge Is_Ogee
10,86,2.6,0, 62, 61, , , 0.95, 0, 1,1,,
 1576.32    1578    1598    1600    1863  1984.3  2579.3  3040.1  3190.1  3200.1
  3348.3  3715.1  4170.1  4192.6  4202.6    4566    4581    4646    4651    4786
    4811    4816    4821    4822    4846 4857.76 4877.71 5142.24    5241  5244.4
  6428.5  6643.5  6668.5  6678.5  6823.5  6949.4  6969.4  7009.4  7039.4  7069.4
  7104.4  7164.4  7179.4  7229.4  7239.4  7274.4  7299.4  7414.4  7464.4  7509.4
  7519.4  7534.4  7544.4  7584.4  7609.4  7634.4  7659.4  7679.4  7749.4  8233.2
  8371.2 8379.91
      51    50.9    50.4    50.5   50.45   50.43   50.33   50.25   50.23   50.23
    50.2    50.4   50.65   50.66   50.66   50.86   50.87    50.9   50.91   50.98
   50.99      51      51      51   50.74   52.11   52.11   52.11   51.66    51.7
   53.32   53.62   53.65   53.67   53.87   54.04   54.07   54.12   54.16    54.2
   54.25   54.33   54.35   54.42   54.44   54.48   54.52   54.68   54.75   54.81
   54.82   54.84   54.86   54.91   54.94   54.98   55.01   55.04   55.14   55.92
    56.2   56.25
                                                                                
                                                                                
                                                   45.79   45.79
                                                                                
                                                                                
                                                                                
                
  1561.2    1578    1598    1600    1863  1984.3  2579.3  3040.1  3190.1  3200.1
  3348.3  3715.1  4170.1  4192.6  4202.6    4566    4581    4646    4651    4786
    4811    4816    4821    4822    4846 4857.76 5142.24    5241  5244.4  6428.5
  6643.5  6668.5  6678.5  6823.5  6949.4  6969.4  7009.4  7039.4  7069.4  7104.4
  7164.4  7179.4  7229.4  7239.4  7274.4  7299.4  7414.4  7464.4  7509.4  7519.4
  7534.4  7544.4  7584.4  7609.4  7634.4  7659.4  7679.4  7749.4  8233.2  8371.2
 8409.68
      51    50.9    50.4    50.5   50.45   50.43   50.33   50.25   50.23   50.23
    50.2    50.4   50.65   50.66   50.66   50.86   50.87    50.9   50.91   50.98
   50.99      51      51      51   50.74   52.11   52.11   51.66    51.7   53.32
   53.62   53.65   53.67   53.87   54.04   54.07   54.12   54.16    54.2   54.25
   54.33   54.35   54.42   54.44   54.48   54.52   54.68   54.75   54.81   54.82
   54.84   54.86   54.91   54.94   54.98   55.01   55.04   55.14   55.92    56.2
   56.25
                                                                                
                                                                                
                                           45.75   45.75
                                                                                
                                                                                
                                                                                
        
Pier Skew, UpSta & Num, DnSta & Num=  ,4945.67, 4 ,4945.67, 4 , 3 , 3 , 0 ,,
       3       3    7.29    7.29
      29   39.47   39.47      52
       3       3    7.29    7.29
      29   39.47   39.47      52
Pier Skew, UpSta & Num, DnSta & Num=  ,5054.33, 4 ,5054.33, 4 , 3 , 3 , 0 ,,
       3       3    7.29    7.29
      29   39.47   39.47      52
       3       3    7.29    7.29
      29   39.47   39.47      52
BR Coef=-1 , 1 , 0 ,1.25, 0 ,,,0.8,0,2,0,
WSPro=,,,, 1 ,,,, 0 ,,,, 0 ,,,,-1 ,-1 ,-1 , 0 , 0 , 0 , 0 , 0
BR U #Sta/Elev= 30
 1576.32   50.56  2188.9   47.16 2293.11   47.45 2322.89   49.79 2382.44   47.28
 2635.54   47.33 2769.54   49.87 2888.64   47.96 4038.93    48.7 4747.94   46.97
 4851.13   43.91 4877.71   48.31 4926.05   29.86 4946.05   29.46 4970.05   21.46
    5002   18.54 5030.05   21.46 5054.05   29.46 5074.05   29.86 5120.89    47.8
 5519.83   46.31  5905.1    50.2 6963.88   53.42 7068.24   51.73  7232.2   54.16
 7336.54   52.35 7470.69   54.12 7560.12   52.52 8335.19   54.94 8379.91   53.43
BR U #Mann= 3
 1576.32      .1 4877.71    .015 5120.89      .1
BC Design=,, 0 ,, 0 ,,,,,,
BC HTab HWMax=54.94
BC Use User HTab Curves=0
BC User HTab FreeFlow(D)= 0

Type RM Length L Ch R = 1 ,80789.12,12.16,10.99,9.84
BEGIN DESCRIPTION:
USACE Sims Bayou Rectification
Reach 7b Bathurst Drive to Robin Boulevard
File No. HSC 409-33
END DESCRIPTION:
XS GIS Cut Line= 6
     3107664.307    13793359.242     3107531.781    13792914.637
     3107185.621    13791853.047     3106549.781    13789808.517
     3106337.821    13789160.677     3105617.861    13786823.907
#Sta/Elev= 30
  1561.2   49.47 2382.44   47.02 2620.65   49.41 2948.19   46.54 3709.87   49.13
 4307.92   46.25 4470.46   46.84 4499.72    50.4 4572.88   46.64 4866.01   49.01
 4878.96   42.51 4926.05    29.8 4946.05    29.4 4970.05    21.4 5001.97   18.48
 5030.05    21.4 5054.05    29.4 5074.05    29.8 5101.92   39.09 5116.25    47.4
 5148.87   48.12  5238.2      48 5267.98   50.84 5327.32   47.78  5475.5   47.02
 5594.05   50.42 5623.69   47.93 5905.23   47.92 7083.11   53.54 8409.68   54.52
#Mann= 3 ,-1 , 0
  1561.2      .1       0 4866.01    .015       0 5148.87      .1       0
#XS Ineff= 2 , 0
       0 4866.01    53.8  5104.7       0    53.8
Permanent Ineff=
       F       F
Bank Sta=4866.01,5148.87
XS Rating Curve= 0 ,0
Exp/Cntr=0.5,0.3

Type RM Length L Ch R = 1 ,80778.13,12.93,13.03,13
BEGIN DESCRIPTION:
USACE Sims Bayou Rectification
Reach 7b Bathurst Drive to Robin Boulevard
File No. HSC 409-33
END DESCRIPTION:
XS GIS Cut Line= 6
     3107634.017    13793208.518     3106897.909    13790907.268
     3106781.679    13790503.868     3106388.529    13789249.228
     3106059.069    13788233.458     3105650.849    13786889.268
#Sta/Elev= 30
 1710.98   49.64 2055.13   47.46 2620.62   49.41 2695.03   47.07 3619.32   47.15
 3708.94    49.2 4337.11   46.25 4502.04   48.99 4706.42   45.78  4866.2   47.56
 4926.05   29.79 4946.05   29.39 4970.05   21.39 4997.56   18.47 5030.05   21.39
 5054.05   29.39 5074.05   29.79 5101.92   39.08  5147.7   48.54 5193.28   46.85
 5267.61   50.64 5297.35   47.02 5401.42   46.16 5549.98   46.97 5594.54    50.7
  5639.1   47.81 5743.06    47.9 7109.08   53.83  7183.8   51.84 8334.53   54.97
#Mann= 3 ,-1 , 0
 1710.98      .1       0  4866.2    .015       0  5147.7      .1       0
#XS Ineff= 2 , 0
       0  4866.2    53.8  5147.7       0    53.8
Permanent Ineff=
       F       F
Bank Sta=4866.2,5147.7
XS Rating Curve= 0 ,0
Exp/Cntr=0.5,0.3