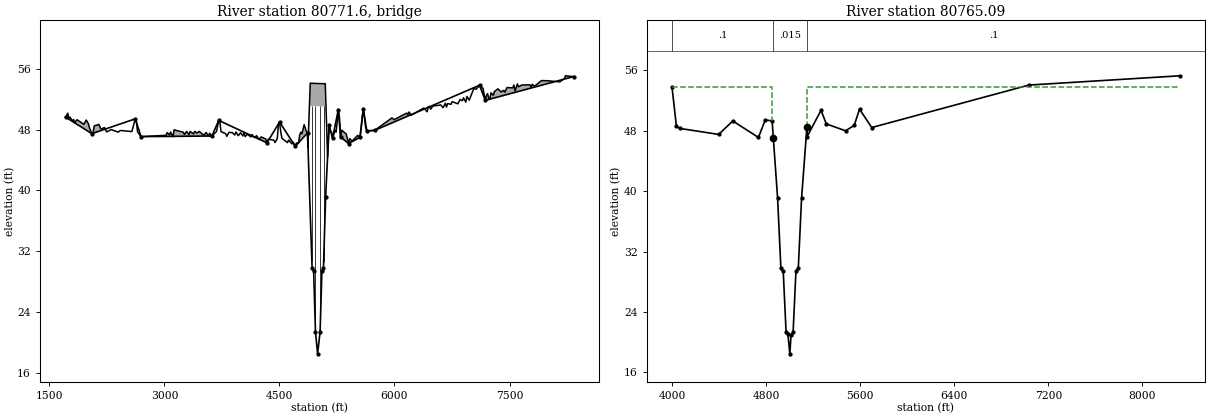
HEC-RAS study C100-00-00.prj: C100-00-00

--- C100-00-00.g01 (geometry) --- (continued)

Type RM Length L Ch R = 3 ,80771.6 ,,,
BEGIN DESCRIPTION:
36" PIPE D/S OF ALMEDA ROAD
END DESCRIPTION:
Bridge Culvert--1,0,-1,-1, 0
Deck Dist Width WeirC Skew NumUp NumDn MinLoCord MaxHiCord MaxSubmerge Is_Ogee
5,3,2.6,0, 194, 92, , , 0.95, 0, 1,1,,
 1710.98 1740.91 1755.87 1770.83 1800.76 1815.72 1830.68 1860.61 1950.39 1980.31
 2010.24  2025.2 2055.13 2070.01 2084.89 2144.42 2174.18 2218.82 2248.59 2308.11
  2397.4 2427.16 2575.98 2620.62  2635.5 2650.38 2695.03 3022.42  3037.3 3067.07
 3081.95 3111.71 3126.59 3245.87 3260.81 3290.68 3320.56 3335.49 3380.31 3395.25
 3425.12    3455 3514.75 3544.63  3574.5 3589.44 3619.32 3679.07 3708.94 3723.88
 3738.82 3798.57 3813.51 3843.39  3888.2 3918.08 3933.01 3962.89 3992.77 4022.64
 4037.58 4052.52 4082.39 4127.21  4142.2 4172.19 4202.17 4232.16 4262.15 4322.12
 4337.11 4352.11 4427.07 4442.07 4472.05 4487.04 4502.04 4517.03 4532.02 4604.98
 4619.47 4662.95 4677.44 4706.42 4720.91 4749.89 4764.39 4778.88 4793.37 4822.35
 4847.07  4866.2  4870.9 4875.67  4889.5    4895    4896 4901.49    4910    4926
    4946  4963.5    4965    4970    5030    5035  5036.5    5054 5054.19  5097.8
 5123.53  5128.3  5147.7 5163.54 5178.41 5193.28 5223.01 5237.88 5252.75 5267.61
 5282.48 5297.35 5312.22 5371.68 5401.42 5416.29 5446.02 5520.28 5549.98 5564.84
 5579.69 5594.54 5624.24  5639.1 5743.06    5966 5995.75 6159.37 6174.24 6189.12
 6218.87 6382.06 6426.46 6441.27 6456.07 6470.87 6500.48 6604.09  6633.7  6663.3
  6678.1 6692.91 6737.31 6752.12 6826.13 6855.73 6885.34 6900.14 6929.74 6944.69
 6974.58 7034.36 7064.25 7109.08 7153.91  7183.8 7198.75 7213.69 7228.63 7243.58
 7258.52 7288.41 7303.36 7348.19 7393.02 7422.91 7437.86 7467.75 7542.47 7557.41
 7572.36 7602.25 7617.19 7662.03 7766.64 7781.58 7796.53 7826.41 7916.08 8005.75
 8155.19 8214.97 8229.92 8334.53
   49.64   50.15   49.48   49.63   49.11   49.33    48.9    49.3   48.69   49.26
   48.76   48.19   47.46   47.59   48.47   48.68   48.07   48.26   47.69      48
   47.66   47.88   47.73   49.41   49.03   47.69   47.07   47.24   47.61    47.3
   47.67   47.04   47.96   47.65   47.37   47.75   47.32   47.75   47.43   47.76
   47.54   47.76   47.25   47.62   47.14   47.52   47.15   47.73    49.2   48.98
   47.73   47.46   47.11   47.64   47.58   47.28   47.68   47.19   47.58   47.16
   47.57   47.07   47.39   47.03   47.35   46.94    47.2    46.7   47.03   46.75
   46.25   46.73    46.6   46.29    46.8    48.7   48.99   47.72   46.86   46.28
   46.61   46.11   46.36   45.78   46.22   46.25   47.32   47.65   47.43   48.64
   47.85   47.56   45.62   46.88   50.75   52.29   52.57    54.1    54.1   54.09
   54.08   54.08   54.08   54.07   54.05   54.05   54.05   54.04   54.04   54.04
   45.88   44.37   48.54   47.79   47.72   46.85    47.9   47.66   48.92   50.64
   49.64   47.02   47.92    47.4   46.16   46.81   46.48   47.23   46.97   48.14
   49.74    50.7   48.29   47.81    47.9   49.53   49.31   50.16   49.97   50.31
   49.89   50.83   50.34      51   51.05   50.68   51.09   51.24   50.88   51.46
   50.96   51.42   51.32   51.67   51.39   51.97   51.79   52.18    51.6   52.36
   51.87    53.4    53.3   53.83   53.43   51.84    52.5   52.73   52.11   52.04
   52.83   52.52   53.01   53.36   52.95   53.16   52.94   53.53   53.49   53.87
   53.06   54.01   53.63   53.87   53.89   53.58   53.96    53.7   54.45   54.42
   54.28   54.71   55.08   54.97
                                                                                
                                                                                
                                                                                
                                                                                
                                                                                
                                                                                
                                                                                
                                                                                
                                                                                
                           43.99   47.75   49.29   49.57    51.1    51.1   51.09
   51.08   51.08   51.08   51.07   51.05   51.05   51.05   51.04   51.04   51.04
    42.7
                                                                                
                                                                                
                                                                                
                                                                                
                                                                                
                                                                                
                                                                                
                                
    4000 4037.65 4067.52 4082.46 4112.34 4322.24 4337.23 4382.21 4397.21  4412.2
 4442.19 4502.16 4517.15 4546.64  4604.6 4677.06 4706.04 4735.02 4792.99 4836.46
 4849.15  4851.7 4868.88  4870.9 4875.67  4889.5    4895    4896 4901.49    4910
    4926    4946  4963.5    4965    4970    5030    5035  5036.5    5054 5054.19
  5097.8 5123.53  5128.3  5147.7 5148.67 5163.54 5237.87 5267.61 5282.48 5312.21
  5475.7 5549.96 5594.52 5639.08 5698.49 5728.19 5743.04 5772.75  5817.3 5832.15
 5876.75  5906.5 5921.38 5951.13 6040.38 6099.88  6144.5 6174.25 6337.58 6396.79
  6426.4 6589.22 6618.83 6678.04 6707.64 6737.24 7004.54 7034.43 7064.32  7124.1
 7198.82 7437.94 7512.67  7557.5 7572.45 7602.33 7826.51  7856.4 7886.29 7931.12
 7946.07 8319.69
    53.8   48.59   48.29   48.58   48.26   47.89   47.48   47.75    47.5    47.9
   47.78   49.27   49.28   48.28   48.25   47.35   47.63    47.1   49.41   49.16
   48.43    49.3   45.01   45.62   46.88   50.75   52.29   52.57    54.1    54.1
   54.09   54.08   54.08   54.08   54.07   54.05   54.05   54.05   54.04   54.04
   54.04   45.88   44.37   48.54   47.21   48.19   49.44   50.69   50.65   48.89
   47.98    48.7   50.85   48.96   48.41    48.9   48.69   49.35   49.18   49.48
   49.75   49.31   49.97   49.75   50.57   50.47   50.89   50.52   51.15   51.37
   51.17   51.96   51.66    52.1    51.9    52.4   53.18   54.03   53.73   54.14
   53.36   54.15   53.93   54.21   53.79    54.3   53.93   54.62   54.39   54.73
   54.48   55.26
                                                                                
                                                                                
                                   43.99   47.75   49.29   49.57    51.1    51.1
   51.09   51.08   51.08   51.08   51.07   51.05   51.05   51.05   51.04   51.04
   51.04    42.7
                                                                                
                                                                                
                                                                                
                                                                                
                
Pier Skew, UpSta & Num, DnSta & Num=  ,4923.1, 2 ,4923.1, 2 , 0 , 0 , 0 ,,
     1.4     1.4
   33.38    52.1
     1.4     1.4
   33.38    52.1
Pier Skew, UpSta & Num, DnSta & Num=  ,4967.3, 2 ,4967.3, 2 , 0 , 0 , 0 ,,
     1.4     1.4
   28.08   52.08
     1.4     1.4
   28.08   52.08
Pier Skew, UpSta & Num, DnSta & Num=  ,5033.5, 2 ,5033.5, 2 , 0 , 0 , 0 ,,
     1.4     1.4
   25.69   52.04
     1.4     1.4
   25.69   52.04
Pier Skew, UpSta & Num, DnSta & Num=  ,5076.2, 2 ,5076.2, 2 , 0 , 0 , 0 ,,
     1.4     1.4
   20.12   52.06
     1.4     1.4
   20.12   52.06
BR Coef=-1 , 1 , 0 ,1.25, 0 ,,,0.8,0,2,0,
WSPro=,,,, 1 ,,,, 0 ,,,, 0 ,,,,-1 ,-1 ,-1 , 0 , 0 , 0 , 0 , 0
BC Design=,, 0 ,, 0 ,,,,,,
BC HTab HWMax=55.08
BC Use User HTab Curves=0
BC User HTab FreeFlow(D)= 0

Type RM Length L Ch R = 1 ,80765.09,32.95,33,32.94
BEGIN DESCRIPTION:
USACE Sims Bayou Rectification
Reach 7b Bathurst Drive to Robin Boulevard
File No. HSC 409-33
END DESCRIPTION:
XS GIS Cut Line= 6
     3106949.153    13791027.019     3106799.244    13790516.459
     3106703.514    13790227.589     3106406.094    13789261.819
     3106076.634    13788246.049     3105668.404    13786901.849
#Sta/Elev= 30
    4000    53.8 4037.65   48.59 4067.52   48.29 4397.21    47.5 4517.15   49.28
 4735.02    47.1 4792.99   49.41  4851.7    49.3  4861.8   47.01 4898.18   39.07
 4926.05   29.78 4946.05   29.38 4970.05   21.38 4985.93   21.04 5001.97   18.46
 5012.38   20.92 5030.05   21.38 5054.05   29.38 5074.05   29.78 5101.92   39.07
  5147.7   48.54 5148.67   47.21 5267.61   50.69 5312.21   48.89  5475.7   47.98
 5549.96    48.7 5594.52   50.85 5698.49   48.41 7034.43   54.03 8319.69   55.26
#Mann= 3 ,-1 , 0
    4000      .1       0  4861.8    .015       0  5147.7      .1       0
#XS Ineff= 2 , 0
       0  4851.7    53.8  5147.7       0    53.8
Permanent Ineff=
       F       F
Bank Sta=4861.8,5147.7
XS Rating Curve= 0 ,0
Exp/Cntr=0.5,0.3