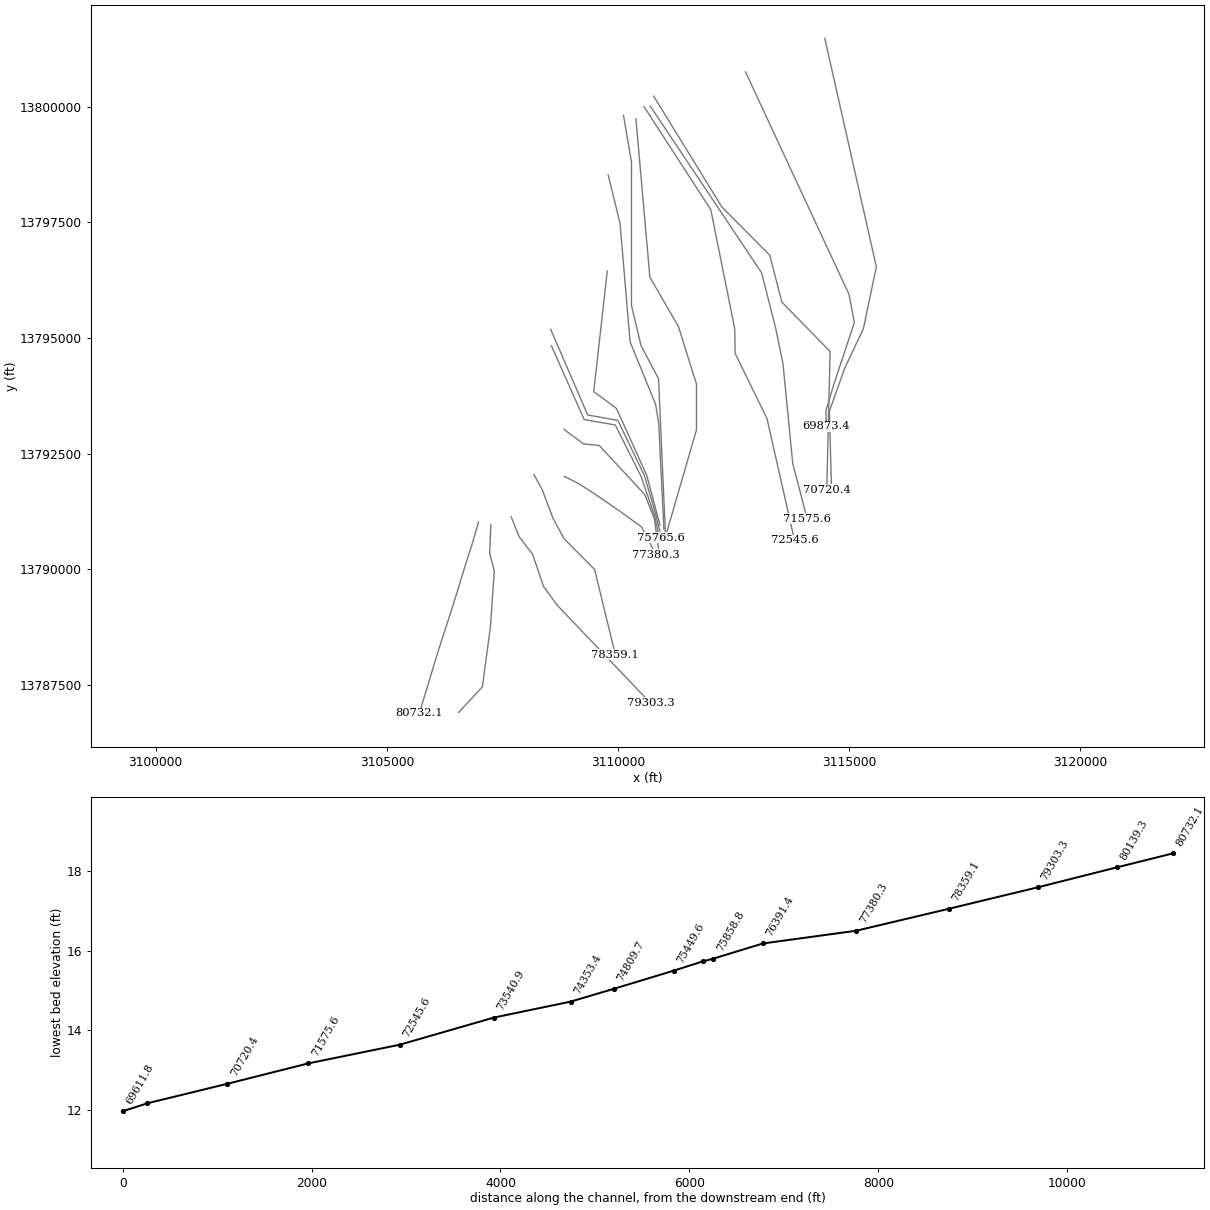
HEC-RAS study C100-00-00.prj: C100-00-00

--- C100-00-00.g01 (geometry) --- (continued)

Type RM Length L Ch R = 3 ,80749.6 ,,,
BEGIN DESCRIPTION:
MISSOURI PACIFIC RAILROAD
END DESCRIPTION:
Bridge Culvert--1,0,-1,-1, 0
Deck Dist Width WeirC Skew NumUp NumDn MinLoCord MaxHiCord MaxSubmerge Is_Ogee
10,16,2.6,0, 194, 193, , , 0.95, 0, 1,1,,
    4000 4037.65  4178.3  4188.3  4203.3  4243.3  4263.3  4293.3  4313.3  4363.3
  4425.3  4460.3  4475.3  4495.3  4505.3  4510.3  4520.3  4530.3  4540.3  4555.3
  4565.3  4575.3  4590.3  4600.3  4615.3  4625.3  4635.3  4650.3  4660.3  4665.3
  4670.3  4695.3  4720.3  4740.3  4745.3  4755.3  4765.3  4775.3  4790.3  4800.3
  4815.3 4849.15 4851.61  4851.7  4851.8  4851.9    4852    4853    4862    4878
    4880    4887    4906    4908    4926    4934    4936    4946    4953    4955
    4970    4981    4983    5008    5011    5030    5037    5039    5054    5065
    5067    5074    5093    5095    5113    5121    5123    5138    5147  5147.7
  5147.8  5147.9 5147.99  5148.1  5149.5  5164.5  5169.5  5174.5  5184.5  5199.5
  5224.5  5229.5  5244.5  5259.5  5274.5  5279.5  5309.5  5319.5  5324.5  5329.5
  5339.5  5359.5  5379.5  5384.9  5404.9  5424.9  5454.9  5474.9  5479.9  5489.9
  5499.9  5529.9  5544.9  5569.9  5574.9  5579.9  5584.9  5589.9  5609.9  5659.9
  5679.9  5792.6  6107.6  6202.6  6207.6  6212.6  6222.6  6247.6  6292.6  6307.6
  6327.6  6342.6  6357.6  6372.6  6392.6  6402.6  6412.6  6447.6  6467.6    6484
    6499    6519    6539    6559    6569    6604    6619    6634    6654    6669
    6689    6729  6750.5  6775.5  6790.5  6850.5  6860.5  6885.5  6910.5  6955.5
  6965.5    7000    7007  7032.5    7047    7127    7152    7172    7197    7222
    7252    7267    7307    7317  7382.5    7417    7432    7462    7497    7522
    7547    7572    7597    7617    7642    7672    7692    7727    7767    7777
    7802    7882  8314.4  8327.3
    53.8    53.8    53.8    53.8    53.8    53.8    53.8    53.8    53.8    53.8
    53.8    53.8    53.8    53.8    53.8    53.8    53.8    53.8    53.8    53.8
    53.8    53.8    53.8    53.8    53.8    53.8    53.8    53.8    53.8    53.8
    53.8    53.8    53.8    53.8    53.8    53.8    53.8    53.8    53.8    53.8
    53.8    53.8    53.8    53.8    53.8    53.8    53.8    53.8    53.8    53.8
    53.8    53.8    53.8    53.8    53.8    53.8    53.8    53.8    53.8    53.8
    53.8    53.8    53.8    53.8    53.8    53.8    53.8    53.8    53.8    53.8
    53.8    53.8    53.8    53.8    53.8    53.8    53.8    53.8    53.8    53.8
    53.8    53.8    53.8    53.8    53.8    53.8    53.8    53.8    53.8    53.8
    53.8    53.8    53.8    53.8    53.8    53.8    53.8    53.8    53.8    53.8
    53.8    53.8    53.8    53.8    53.8    53.8    53.8    53.8    53.8    53.8
    53.8    53.8    53.8    53.8    53.8    53.8    53.8    53.8    53.8    53.8
    53.8    53.8    53.8    53.8    53.8    53.8    53.8    53.8    53.8    53.8
    53.8    53.8    53.8    53.8    53.8    53.8    53.8    53.8    53.8    53.8
    53.8    53.8    53.8    53.8    53.8    53.8    53.8    53.8    53.8    53.8
    53.8    53.8    53.8    53.8    53.8    53.8    53.8    53.8    53.8    53.8
    53.8    53.8    53.8    53.8   53.81   53.85   53.87   53.88   53.89   53.91
   53.93   53.93   53.96   53.96      54   54.03   54.05   54.08   54.11   54.13
   54.16   54.18   54.21   54.23   54.25   54.28    54.3   54.33   54.37   54.38
   54.41   54.51      55      55
                                                                                
                                                                                
                                                                                
                                                                                
           48.43    49.3    49.3    49.3    49.3    49.3    49.3    49.3    49.3
    49.3    49.3    49.3    49.3    49.3    49.3    49.3    49.3    49.3    49.3
    49.3    49.3    49.3    49.3    49.3    49.3    49.3    49.3    49.3    49.3
    49.3    49.3    49.3    49.3    49.3    49.3    49.3    49.3    49.3    49.3
    49.3    49.3    49.3
                                                                                
                                                                                
                                                                                
                                                                                
                                                                                
                                                                                
                                                                                
                                                                                
                                                                                
                                                                                
                                
    4000  4148.3  4178.3  4188.3  4203.3  4243.3  4263.3  4293.3  4313.3  4363.3
  4425.3  4460.3  4475.3  4495.3  4505.3  4510.3  4520.3  4530.3  4540.3  4555.3
  4565.3  4575.3  4590.3  4600.3  4615.3  4625.3  4635.3  4650.3  4660.3  4665.3
  4670.3  4695.3  4720.3  4740.3  4745.3  4755.3  4765.3  4775.3  4790.3  4800.3
  4815.3 4851.61  4851.7  4851.8  4851.9    4852    4853    4862    4878    4880
    4887    4906    4908    4926    4934    4936    4946    4953    4955    4970
    4981    4983    5008    5011    5030    5037    5039    5054    5065    5067
    5074    5093    5095    5113    5121    5123    5138    5147  5147.7  5147.8
  5147.9 5147.99  5148.1  5149.5  5164.5  5169.5  5174.5  5184.5  5199.5  5224.5
  5229.5  5244.5  5259.5  5274.5  5279.5  5309.5  5319.5  5324.5  5329.5  5339.5
  5359.5  5379.5  5384.9  5404.9  5424.9  5454.9  5474.9  5479.9  5489.9  5499.9
  5529.9  5544.9  5569.9  5574.9  5579.9  5584.9  5589.9  5609.9  5659.9  5679.9
  5792.6  6107.6  6202.6  6207.6  6212.6  6222.6  6247.6  6292.6  6307.6  6327.6
  6342.6  6357.6  6372.6  6392.6  6402.6  6412.6  6447.6  6467.6    6484    6499
    6519    6539    6559    6569    6604    6619    6634    6654    6669    6689
    6729  6750.5  6775.5  6790.5  6850.5  6860.5  6885.5  6910.5  6955.5  6965.5
    7000    7007  7032.5    7047    7127    7152    7172    7197    7222    7252
    7267    7307    7317  7382.5    7417    7432    7462    7497    7522    7547
    7572    7597    7617    7642    7672    7692    7727    7767    7777    7802
    7882  8314.4  8327.3
    53.8    53.8    53.8    53.8    53.8    53.8    53.8    53.8    53.8    53.8
    53.8    53.8    53.8    53.8    53.8    53.8    53.8    53.8    53.8    53.8
    53.8    53.8    53.8    53.8    53.8    53.8    53.8    53.8    53.8    53.8
    53.8    53.8    53.8    53.8    53.8    53.8    53.8    53.8    53.8    53.8
    53.8    53.8    53.8    53.8    53.8    53.8    53.8    53.8    53.8    53.8
    53.8    53.8    53.8    53.8    53.8    53.8    53.8    53.8    53.8    53.8
    53.8    53.8    53.8    53.8    53.8    53.8    53.8    53.8    53.8    53.8
    53.8    53.8    53.8    53.8    53.8    53.8    53.8    53.8    53.8    53.8
    53.8    53.8    53.8    53.8    53.8    53.8    53.8    53.8    53.8    53.8
    53.8    53.8    53.8    53.8    53.8    53.8    53.8    53.8    53.8    53.8
    53.8    53.8    53.8    53.8    53.8    53.8    53.8    53.8    53.8    53.8
    53.8    53.8    53.8    53.8    53.8    53.8    53.8    53.8    53.8    53.8
    53.8    53.8    53.8    53.8    53.8    53.8    53.8    53.8    53.8    53.8
    53.8    53.8    53.8    53.8    53.8    53.8    53.8    53.8    53.8    53.8
    53.8    53.8    53.8    53.8    53.8    53.8    53.8    53.8    53.8    53.8
    53.8    53.8    53.8    53.8    53.8    53.8    53.8    53.8    53.8    53.8
    53.8    53.8    53.8   53.81   53.85   53.87   53.88   53.89   53.91   53.93
   53.93   53.96   53.96      54   54.03   54.05   54.08   54.11   54.13   54.16
   54.18   54.21   54.23   54.25   54.28    54.3   54.33   54.37   54.38   54.41
   54.51      55      55
                                                                                
                                                                                
                                                                                
                                                                                
           49.29   49.29   49.29   49.29   49.29   49.29   49.29   49.29   49.29
   49.29   49.29   49.29   49.29   49.29   49.29   49.29   49.29   49.29   49.29
   49.29   49.29   49.29   49.29   49.29   49.29   49.29   49.29   49.29   49.29
   49.29   49.29   49.29   49.29   49.29   49.29   49.29   49.29   49.29   49.29
   49.29   49.29
                                                                                
                                                                                
                                                                                
                                                                                
                                                                                
                                                                                
                                                                                
                                                                                
                                                                                
                                                                                
                        
Pier Skew, UpSta & Num, DnSta & Num=  ,4879, 2 ,4879, 2 , 0 , 0 , 0 ,,
     1.8     1.8
   42.22    50.3
     1.8     1.8
   42.21   50.29
Pier Skew, UpSta & Num, DnSta & Num=  ,4907, 2 ,4907, 2 , 0 , 0 , 0 ,,
     1.8     1.8
   34.14    50.3
     1.8     1.8
   34.13   50.29
Pier Skew, UpSta & Num, DnSta & Num=  ,4935, 2 ,4935, 2 , 0 , 0 , 0 ,,
     1.8     1.8
    28.1    50.3
     1.8     1.8
   28.09   50.29
Pier Skew, UpSta & Num, DnSta & Num=  ,4954, 2 ,4954, 2 , 0 , 0 , 0 ,,
     1.8     1.8
   25.14    50.3
     1.8     1.8
   25.13   50.29
Pier Skew, UpSta & Num, DnSta & Num=  ,4982, 2 ,4982, 2 , 0 , 0 , 0 ,,
     1.8     1.8
   20.12    50.3
     1.8     1.8
   20.11   50.29
Pier Skew, UpSta & Num, DnSta & Num=  ,5009.5, 2 ,5009.5, 2 , 0 , 0 , 0 ,,
     2.8     2.8
   20.12    50.3
     2.8     2.8
   20.11   50.29
Pier Skew, UpSta & Num, DnSta & Num=  ,5038, 2 ,5038, 2 , 0 , 0 , 0 ,,
     1.8     1.8
   22.44    50.3
     1.8     1.8
   22.43   50.29
Pier Skew, UpSta & Num, DnSta & Num=  ,5066, 2 ,5066, 2 , 0 , 0 , 0 ,,
     1.8     1.8
    28.1    50.3
     1.8     1.8
   28.09   50.29
Pier Skew, UpSta & Num, DnSta & Num=  ,5094, 2 ,5094, 2 , 0 , 0 , 0 ,,
     1.8     1.8
   34.44    50.3
     1.8     1.8
   34.43   50.29
Pier Skew, UpSta & Num, DnSta & Num=  ,5122, 2 ,5122, 2 , 0 , 0 , 0 ,,
     1.8     1.8
   42.32    50.3
     1.8     1.8
   42.31   50.29
BR Coef=-1 , 0 , 0 ,, 0 ,,,0.8,-1,,0,
WSPro=,,,, 1 ,,,, 0 ,,,, 0 ,,,,-1 ,-1 ,-1 , 0 , 0 , 0 , 0 , 0
BR D #Sta/Elev= 175
    4000   53.78  4148.3   47.08  4178.3   46.68  4188.3   47.08  4203.3   47.18
  4243.3   46.88  4263.3   46.98  4293.3   46.48  4313.3   46.58  4363.3   46.78
  4425.3   46.58  4460.3   47.08  4475.3   48.88  4495.3   49.18  4505.3   46.78
  4510.3   46.58  4520.3   46.58  4530.3   46.28  4540.3   46.48  4555.3   45.98
  4565.3   46.48  4575.3   46.18  4590.3   46.38  4600.3   45.98  4615.3   46.48
  4625.3   46.18  4635.3   46.28  4650.3   45.78  4660.3   46.38  4665.3   46.38
  4670.3   46.68  4695.3   45.98  4720.3   47.08  4740.3   46.78  4745.3   46.98
  4755.3   47.78  4765.3   47.58  4775.3   47.88  4790.3   47.48  4800.3   48.38
  4815.3   48.88 4851.61   49.28  4851.7   49.28  4865.9    47.9 4877.27   46.01
 4926.05   29.75 4946.05   29.35 4970.05   21.35 4985.93   21.01 4989.24   20.69
  4991.5   20.11 4995.89   18.66 4996.44   18.54 4997.16   18.46 5002.37   18.44
 5003.14   18.49 5003.78   18.59 5008.59   20.15 5011.21   20.76 5013.65   20.99
 5030.05   21.35 5054.05   29.35 5074.05   29.75 5121.18   45.46  5147.7   48.52
  5149.5   47.58  5164.5   48.18  5169.5   48.08  5174.5   48.38  5184.5   47.68
  5199.5   47.18  5224.5   48.48  5229.5   48.48  5244.5   50.38  5259.5   50.18
  5274.5   48.28  5279.5   47.98  5309.5   47.68  5319.5   47.98  5324.5   47.68
  5329.5   47.88  5339.5   47.38  5359.5   46.88  5379.5   47.48  5384.9   46.98
  5404.9   46.38  5424.9   47.18  5454.9   46.48  5474.9   47.28  5479.9   47.08
  5489.9   47.18  5499.9   46.78  5529.9   47.38  5544.9   47.88  5569.9   50.58
  5574.9   50.68  5579.9   50.48  5584.9   49.98  5589.9   49.08  5609.9   47.88
  5659.9   47.48  5679.9   47.78  5792.6   48.28  6107.6   49.58  6202.6   49.78
  6207.6   49.68  6212.6   49.78  6222.6   49.48  6247.6   49.98  6292.6   49.88
  6307.6   50.28  6327.6   50.08  6342.6   50.68  6357.6   50.68  6372.6   50.28
  6392.6   50.68  6402.6   50.68  6412.6   50.18  6447.6   50.88  6467.6   50.58
    6484   50.98    6499   51.08    6519   50.78    6539   51.18    6559   51.08
    6569   50.88    6604   51.38    6619   50.98    6634   51.18    6654   51.38
    6669   50.98    6689   51.48    6729   51.28  6750.5   51.68  6775.5   51.18
  6790.5   51.48  6850.5   51.78  6860.5   52.08  6885.5   51.68  6910.5   52.18
  6955.5   52.48  6965.5   52.48    7000   53.31    7007   53.48  7032.5   53.35
    7047   53.28    7127   53.58    7152   52.78    7172   52.68    7197   52.28
    7222   52.78    7252   52.58    7267   53.08    7307   53.08    7317   53.48
  7382.5   53.48    7417   53.48    7432   53.18    7462   53.78    7497   53.38
    7522   53.98    7547   53.38    7572   53.98    7597   53.58    7617   54.08
    7642   53.68    7672   53.88    7692   53.48    7727   53.88    7767   53.88
    7777   54.08    7802   53.58    7882   54.48  8314.4   54.97  8327.3   54.98
BR D #Mann= 4
    4000      .1  4865.9    .015  5147.7      .1  8314.4      .2
BC Design=,, 0 ,, 0 ,,,,,,
BC HTab HWMax=55.26
BC Use User HTab Curves=0
BC User HTab FreeFlow(D)= 0

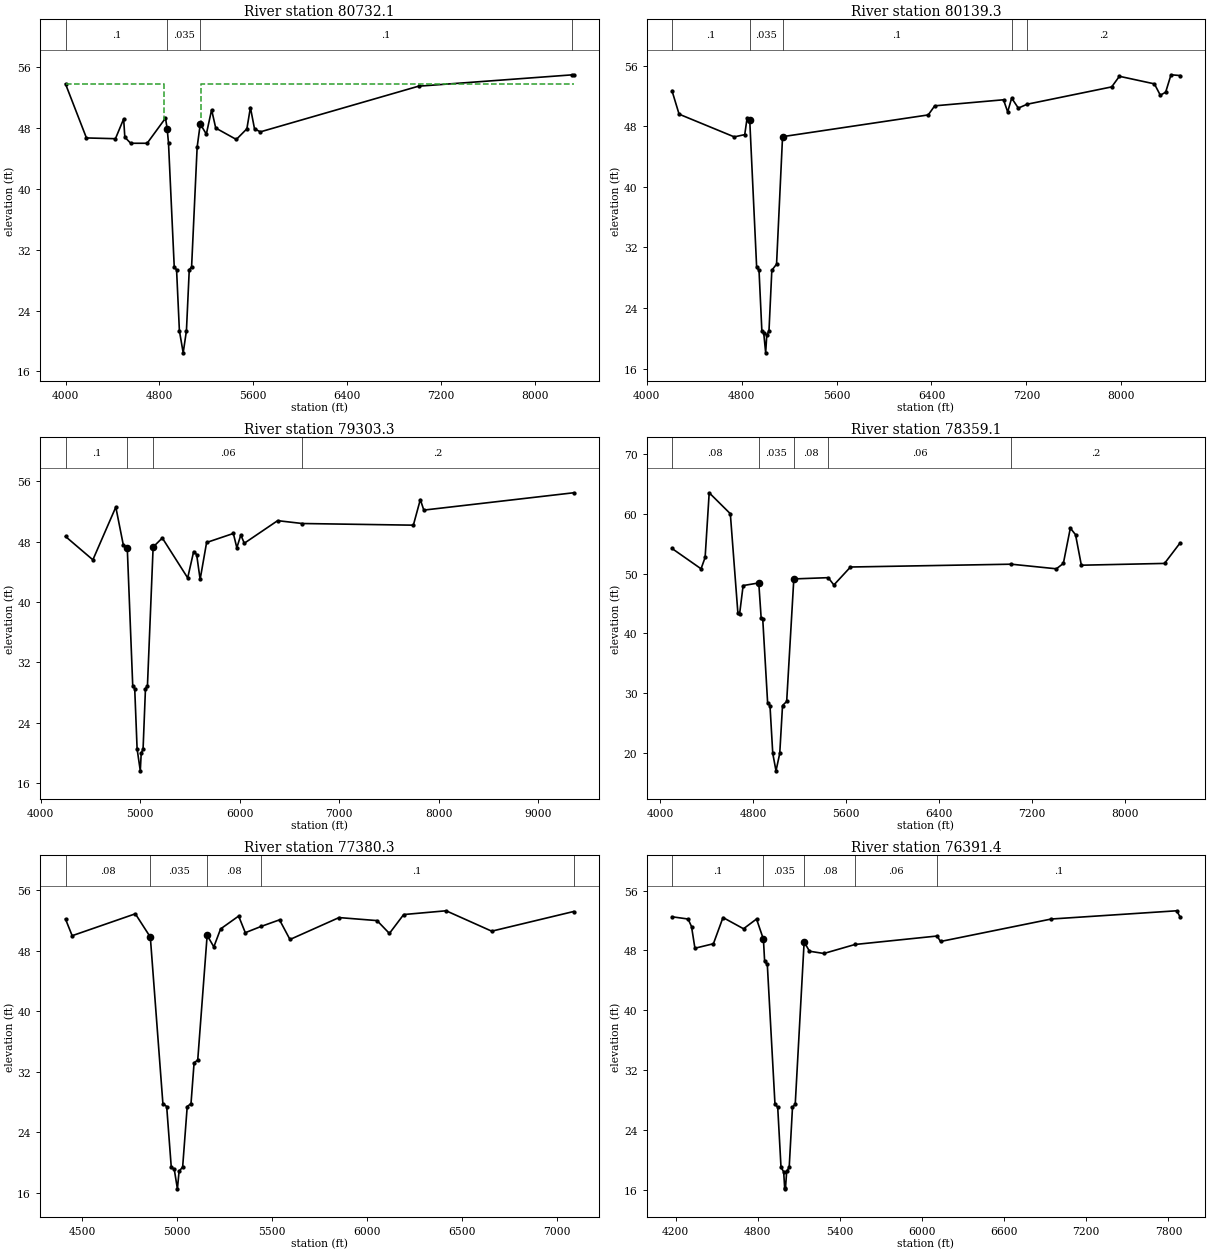
Type RM Length L Ch R = 1 ,80732.1 ,520.73,592.77,662.39
BEGIN DESCRIPTION:
Downstream Section of Bridge/Culvert/Weir
USACE Sims Bayou Rectification
Reach 7b Bathurst Drive to Robin Boulevard
File No. HSC 409-33
END DESCRIPTION:
XS GIS Cut Line= 6
     3106983.451     13791026.31      3106831.71     13790505.07
      3106735.98      13790216.2      3106438.56     13789250.43
       3106109.1     13788234.66      3105700.87     13786890.46
#Sta/Elev= 30
    4000   53.78  4178.3   46.68  4425.3   46.58  4495.3   49.18  4505.3   46.78
  4555.3   45.98  4695.3   45.98 4851.61   49.28  4865.9    47.9 4877.27   46.01
 4926.05   29.75 4946.05   29.35 4970.05   21.35 5002.37   18.44 5030.05   21.35
 5054.05   29.35 5074.05   29.75 5121.18   45.46  5147.7   48.52  5199.5   47.18
  5244.5   50.38  5279.5   47.98  5454.9   46.48  5544.9   47.88  5574.9   50.68
  5609.9   47.88  5659.9   47.48    7007   53.48  8314.4   54.97  8327.3   54.98
#Mann= 4 ,-1 , 0
    4000      .1       0  4865.9    .035       0  5147.7      .1       0
  8314.4      .2       0
#XS Ineff= 2 , 0
       0    4842    53.8    5156       0    53.8
Permanent Ineff=
       F       F
Bank Sta=4865.9,5147.7
XS Rating Curve= 0 ,0
Exp/Cntr=0.5,0.3

Type RM Length L Ch R = 1 ,80139.3 ,779.76,836.04,890.49
BEGIN DESCRIPTION:
Cross Section 81887.2
USACE Sims Bayou Rectification
Reach 7b Bathurst Drive to Robin Boulevard
File No. HSC 409-33
END DESCRIPTION:
XS GIS Cut Line= 6
      3107248.46     13790964.68      3107223.61      13790351.8
        3107323.     13789962.52      3107240.18     13788765.71
      3107066.25     13787465.36      3106552.73     13786910.44
#Sta/Elev= 30
  4212.2    52.7  4272.2    49.6  4737.2    46.6  4825.6    46.9  4845.6    49.1
 4867.71   48.82    4926   29.39    4946   28.99    4970   20.99 4986.11   20.66
 5002.09   18.09 5011.26   20.41    5030   20.99    5054   28.99 5093.88    29.8
 5144.39   46.63  6372.4    49.5  6427.1    50.7  7007.1    51.5  7042.1    49.9
  7075.8   51.72  7132.1    50.4  7205.6   50.91    7919    53.2    7984    54.6
    8279    53.6    8329    52.1    8374    52.5    8419    54.8    8495    54.7
#Mann= 5 ,-1 , 0
  4212.2      .1       0 4867.71    .035       0 5144.39      .1       0
  7075.8     .14       0  7205.6      .2       0
Bank Sta=4867.71,5144.39
XS Rating Curve= 0 ,0
Exp/Cntr=0.3,0.1

Type RM Length L Ch R = 1 ,79303.3 ,1028.96,944.15,904.09
BEGIN DESCRIPTION:
Cross Section 81060.8
USACE Sims Bayou Rectification
Reach 7b Bathurst Drive to Robin Boulevard
File No. HSC 409-33
END DESCRIPTION:
XS GIS Cut Line= 6
      3107686.64     13791140.59      3107861.36      13790703.8
      3108151.25     13790331.09      3108391.44     13789627.08
      3108689.61     13789221.24      3110702.24     13787113.36
#Sta/Elev= 30
  4250.6    48.7  4525.6    45.6    4756    52.6    4831    47.6 4871.25   47.15
    4926    28.9    4946    28.5    4970    20.5 5002.04   17.59 5011.28   19.92
    5030    20.5    5054    28.5    5074    28.9    5131    47.3  5223.2    48.5
  5478.2    43.2  5538.2    46.7  5568.2    46.3  5603.2      43  5668.2    47.9
    5937    49.1    5972    47.2    6012    48.9    6047    47.8    6382    50.8
  6630.1   50.42  7745.6    50.2  7815.6    53.6  7850.6    52.2  9355.1    54.5
#Mann= 4 ,-1 , 0
  4250.6      .1       0 4871.25    .035       0    5131     .06       0
  6630.1      .2       0
Bank Sta=4871.25,5131
XS Rating Curve= 0 ,0
Exp/Cntr=0.3,0.1

Type RM Length L Ch R = 1 ,78359.1 ,884.37,978.81,1067
BEGIN DESCRIPTION:
Cross Section 80105.4
USACE Sims Bayou Rectification
Reach 7b Bathurst Drive to Robin Boulevard
File No. HSC 409-33
END DESCRIPTION:
XS GIS Cut Line= 6
      3108178.93     13792052.23      3108358.31     13791726.69
      3108590.22     13791113.78      3108830.41     13790666.53
        3109493.     13789999.79      3109940.26     13788161.09
#Sta/Elev= 30
  4103.5    54.2  4353.5    50.8  4388.5    52.7  4423.5    63.5  4605.2      60
  4670.2    43.4  4685.2    43.3  4715.2      48 4849.69   48.44    4870   42.64
    4884   42.36    4926   28.36    4946   27.96    4970   19.96 4997.84   17.05
    5030   19.96    5054   27.96 5089.62   28.64 5151.02   49.11  5446.6   49.32
  5495.5    48.1  5638.2    51.1  7020.6   51.57  7408.2    50.8  7468.2    51.7
  7528.2    57.6  7572.9    56.5  7622.9    51.4  8337.9    51.7  8471.1    55.1
#Mann= 5 ,-1 , 0
  4103.5     .08       0 4849.69    .035       0 5151.02     .08       0
  5446.6     .06       0  7020.6      .2       0
Bank Sta=4849.69,5151.02
XS Rating Curve= 0 ,0
Exp/Cntr=0.3,0.1

Type RM Length L Ch R = 1 ,77380.3 ,908.81,988.93,1018.99
BEGIN DESCRIPTION:
Cross Section 79119.3
USACE Sims Bayou Rectification
Reach 7b Bathurst Drive to Robin Boulevard
File No. HSC 409-33
END DESCRIPTION:
XS GIS Cut Line= 6
      3108839.37      13792010.8      3109153.42     13791850.92
      3109501.29      13791627.3      3110056.21      13791246.3
      3110511.75     13790915.01       3110818.2     13790318.67
#Sta/Elev= 30
  4413.7    52.2  4448.7      50  4781.1    52.9 4859.92   49.82    4926   27.79
    4946   27.39    4970   19.39 4985.95   19.07 5002.39    16.5 5011.23   18.82
    5030   19.39    5054   27.39    5074   27.79 5090.13   33.17 5109.41   33.56
 5158.91   50.06    5194   48.52  5229.6    50.9  5324.6    52.6  5359.6    50.4
  5441.9   51.22  5539.6    52.1  5594.6    49.5  5852.7    52.4  6052.7      52
  6117.7    50.3  6192.7    52.8    6416    53.3    6656    50.6  7086.5    53.2
#Mann= 5 ,-1 , 0
  4413.7     .08       0 4859.92    .035       0 5158.91     .08       0
  5441.9      .1       0  7086.5      .2       0
Bank Sta=4859.92,5158.91
XS Rating Curve= 0 ,0
Exp/Cntr=0.3,0.1

Type RM Length L Ch R = 1 ,76391.4 ,539.36,525.27,555.63
BEGIN DESCRIPTION:
Cross Section 78128.1
USACE Sims Bayou Rectification
Reach 7b Bathurst Drive to Robin Boulevard
File No. HSC 409-33
END DESCRIPTION:
XS GIS Cut Line= 6
     3108830.267     13793026.82      3109252.81      13792712.3
      3109592.39     13792679.17      3110578.01     13791619.01
      3110785.07     13791097.22     3110896.743    13790296.902
#Sta/Elev= 30
  4173.6    52.5  4291.3    52.2  4316.3    51.2  4341.3    48.3  4476.3    48.9
  4546.3    52.4  4696.3    50.9  4791.3    52.2 4841.62    49.5 4850.47   46.53
 4870.02   46.14    4926   27.48    4946   27.08    4970   19.08 4989.64   18.44
 4996.84   16.29 5002.37   16.18 5011.61   18.51    5030   19.08    5054   27.08
    5074   27.48 5138.98   49.14  5178.1    47.9  5283.1    47.6  5510.5    48.8
  6109.9   49.93  6135.2    49.2  6944.2    52.2  7860.5    53.3  7884.7    52.5
#Mann= 5 ,-1 , 0
  4173.6      .1       0 4841.62    .035       0 5138.98     .08       0
  5510.5     .06       0  6109.9      .1       0
Bank Sta=4841.62,5138.98
XS Rating Curve= 0 ,0
Exp/Cntr=0.5,0.3

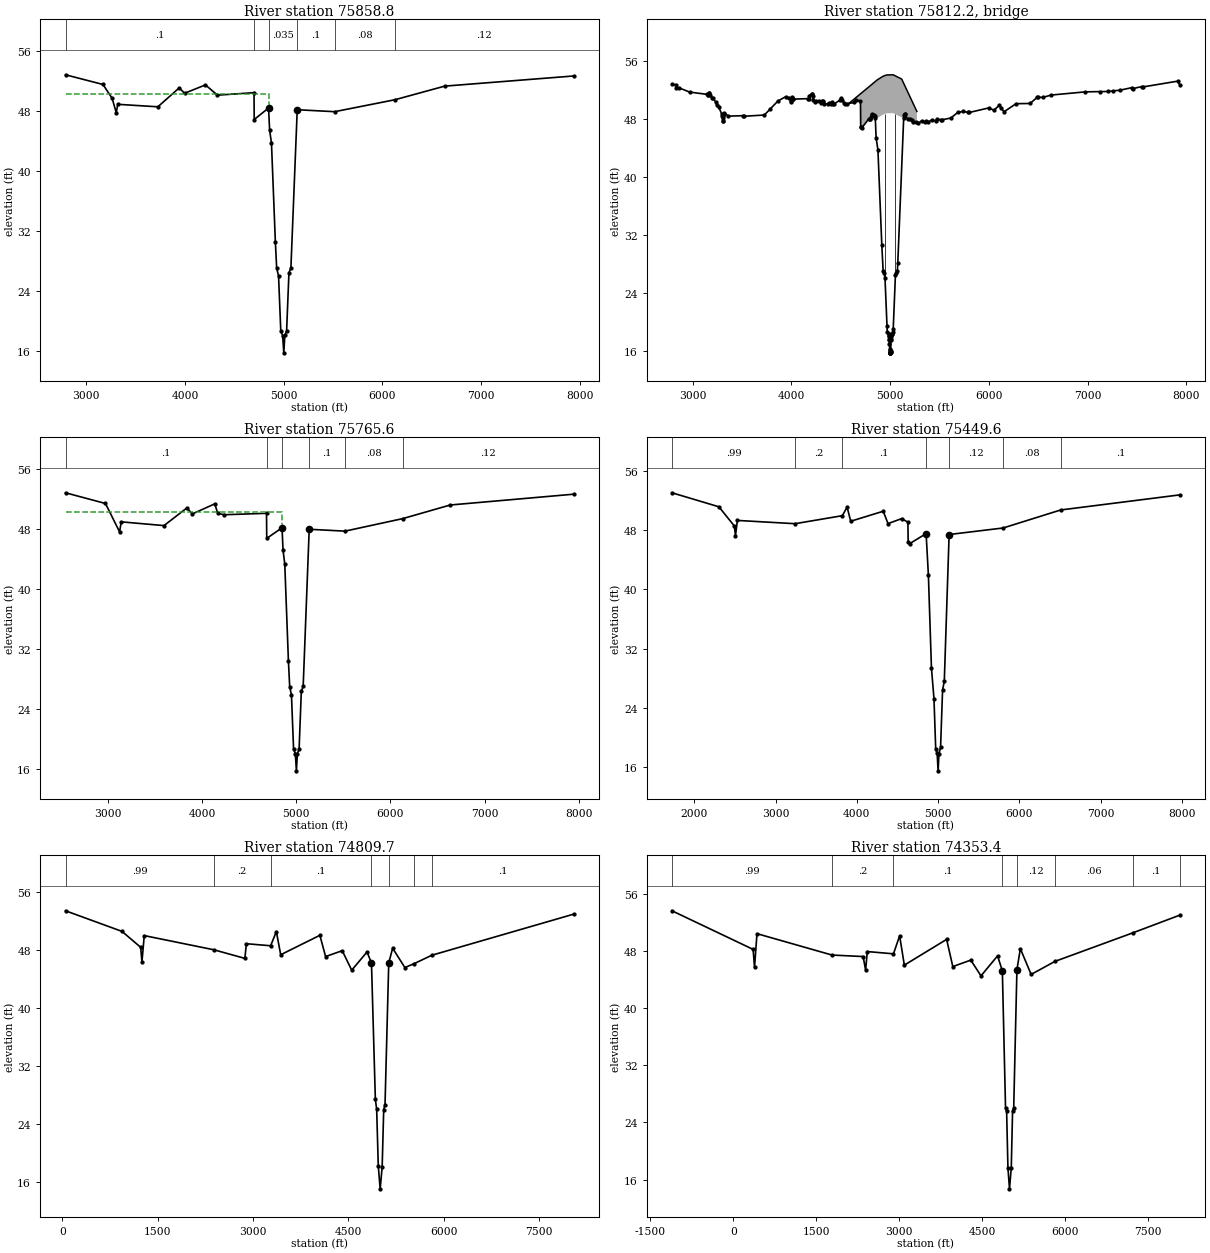
Type RM Length L Ch R = 1 ,75858.8 ,111.4,111.72,110.91
BEGIN DESCRIPTION:
Interpolated cross section, 0.1 ' from us face of Orem Bridge
USACE Sims Bayou Rectification
Reach 7b Bathurst Drive to Robin Boulevard
File No. HSC 409-33
END DESCRIPTION:
XS GIS Cut Line= 6
  3108559.04749813794831.5807824 3109267.879741713793238.8132986
 3109939.754710313793121.6255409 3110497.046574713792012.2507911
 3110796.525634613791139.8548981 3110907.577249713790593.4107811
#Sta/Elev= 30
 2789.59   52.79 3169.27    51.5 3262.21   49.65 3303.51   47.75 3319.01   48.86
 3725.41   48.53 3941.83   51.05  3995.4   50.33  4207.1   51.44 4329.36   50.08
 4699.27   50.41 4701.43   46.84 4846.74   48.37 4857.58   45.39 4876.05   43.75
 4915.45   30.61 4928.96   27.04 4947.86   26.05 4970.54   18.69 4989.11    18.1
 5001.14    15.8 5011.31   18.11 5029.48   18.69 5053.19   26.46 5072.95   27.08
 5137.14   48.14 5515.91   47.88 6127.01   49.47 6630.96   51.28 7936.45   52.63
#Mann= 6 ,-1 , 0
 2789.59      .1       0 4699.27     .05       0 4846.74    .035       0
 5137.14      .1       0 5515.91     .08       0 6127.01     .12       0
#XS Ineff= 2 , 0
       0 4846.74   50.21 5137.14       0   47.39
Permanent Ineff=
       F       F
Bank Sta=4846.74,5137.14
XS Rating Curve= 0 ,0
Exp/Cntr=0.5,0.3

Type RM Length L Ch R = 3 ,75812.2 ,,,
BEGIN DESCRIPTION:
West Orem Drive
END DESCRIPTION:
Bridge Culvert--1,0,-1,-1, 0
Deck Dist Width WeirC Skew NumUp NumDn MinLoCord MaxHiCord MaxSubmerge Is_Ogee
9.4,93,2.6,0, 15, 15, , , 0.95, 0, 0,0,,
 4582.91 4772.36 4813.19 4835.59  4841.2 4852.59 4862.09  4870.5 4924.38 4944.65
 4969.66 5030.35 5116.91 5147.43 5270.78
   50.14   52.27   52.73   52.99   53.05   53.18   53.29   53.38   53.84   53.96
   54.05   54.07   53.48   52.59   49.02
   46.14      10      10   48.34   47.77    47.9   48.01    48.1   48.56   48.68
   48.77   48.79    48.2   47.11   45.02
 4582.91 4772.36 4813.19 4835.59  4841.2 4852.59 4862.09  4870.5 4924.38 4944.65
 4969.66 5030.35 5116.91 5147.43 5270.78
   50.14   52.27   52.73   52.99   53.05   53.18   53.29   53.38   53.84   53.96
   54.05   54.07   53.48   52.59   49.02
   46.14      10      10   48.34   47.77    47.9   48.01    48.1   48.56   48.68
   48.77   48.79    48.2   47.11   45.02
Pier Skew, UpSta & Num, DnSta & Num=  ,4948.15, 4 ,4948.15, 4 , 3 , 3 , 0 ,,
    3.16    3.16    3.64    3.64
      10   44.62   44.62      52
    3.16    3.16    3.64    3.64
      10   44.62   44.62      52
Pier Skew, UpSta & Num, DnSta & Num=  ,5051.86, 4 ,5051.86, 4 , 3 , 3 , 0 ,,
    3.16    3.16    3.64    3.64
      10   44.62   44.62      52
    3.16    3.16    3.64    3.64
      10   44.62   44.62      52
BR Coef=-1 , 1 , 0 ,1.25, 0 ,,,0.8,0,1.2,0,
WSPro=,,,, 1 ,,,, 0 ,,,, 0 ,,,,-1 ,-1 ,-1 , 0 , 0 , 0 , 0 , 0
BR U #Sta/Elev= 170
 2789.59   52.79 2829.17    52.7 2834.34   52.31 2859.77   52.28 2967.97   51.69
 3143.45   51.38 3153.47   51.33 3158.94   51.26 3164.11   51.52 3169.27    51.5
 3174.43   51.24 3196.81   50.89 3205.41   50.84 3230.76   50.36 3241.56   49.96
 3262.21   49.65 3294.91   48.64 3298.35   48.38 3303.51   47.75 3305.23   47.75
 3308.05   48.07  3310.4   48.41 3313.84   48.73 3315.56   48.73 3319.01   48.86
 3362.03   48.38 3511.77   48.44 3516.93   48.36 3725.41   48.53 3785.94   49.38
 3864.53   50.48 3941.83   51.05 3979.91   50.89  3995.4   50.33 3997.12   50.46
 4000.56   50.84 4005.73   50.98 4016.05   50.73 4019.12   50.72 4168.82    50.8
 4176.11   50.79 4181.28   51.21  4207.1   51.44 4208.89   51.39 4215.77    51.1
 4222.65   50.65 4236.42   50.36 4250.99   50.44 4281.17   50.47 4296.66   50.16
 4306.99   50.27 4313.87   50.52 4319.04    50.5 4322.48   50.27 4329.36   50.08
 4372.39   50.04 4377.55   50.19 4398.21   50.07 4405.57    50.2 4408.54   50.28
 4415.42    50.2 4420.58   49.98 4430.91   50.04 4494.59   50.61 4499.76   50.87
 4514.14    50.6 4531.35   50.21 4538.23      50 4560.61   50.07 4638.06   50.27
 4650.11    50.6 4699.27   50.41 4701.43   46.84 4708.63   46.86 4713.79   46.77
 4784.35   48.02 4791.24   47.93 4794.68      48 4805.01   48.21  4811.9   48.52
 4817.05   48.61 4837.71   48.51 4846.74   48.37 4849.21   48.19 4857.58   45.39
 4876.05   43.75 4915.45   30.61 4928.96   27.04 4938.88   26.84 4947.86   26.05
 4967.57   19.47 4970.54   18.69 4985.04    18.4 4985.55   18.36 4988.77   18.13
 4989.11    18.1 4991.02   17.67 4991.15   17.63 4993.13   17.02 4995.39   16.26
 4995.91   16.14 4996.59   16.03 4998.66   15.87 4999.47   15.83 5000.35   15.81
 5001.14    15.8 5002.19    15.8 5002.98   15.82 5003.78   15.93 5003.99   15.96
 5004.33   16.06 5008.93   17.58 5009.26   17.66 5011.23   18.09 5011.31   18.11
 5013.44   18.32 5013.72   18.34 5015.63    18.4 5029.48   18.69  5031.1    19.1
 5053.19   26.46 5055.97   26.74 5072.95   27.08 5077.11   28.13 5137.14   48.14
 5142.87   48.49 5151.53   48.66  5151.7   48.65 5177.03   47.94  5196.1   47.97
 5219.83   47.84 5234.06   47.63 5262.52   47.56 5284.07   47.39 5319.76   47.74
 5352.66   47.59 5362.15   47.65 5381.12   47.52 5419.07   47.84 5461.78   47.75
 5476.01   47.93 5515.91   47.88 5523.45   47.87 5615.42   48.12 5683.83   48.88
  5739.9   49.02 5791.78   48.91 5801.07   48.88 5999.88   49.51 6050.85    49.2
 6106.93   49.87 6127.01   49.47  6152.8   48.97 6275.15   50.09 6417.88   50.12
 6489.25   50.96 6494.31   50.96 6550.42   50.97 6630.96   51.28  6977.6   51.72
 7122.06   51.75 7203.22   51.77 7253.38   51.84  7329.3   51.95  7447.9    52.3
 7462.13   52.18 7547.52   52.44 7561.76    52.4 7911.78   53.19 7936.45   52.63
BR U #Mann= 8
 2789.59      .1 4699.27     .05 4846.74    .035 4928.96    .015 5072.95    .035
 5137.14      .1 5515.91     .08 6127.01     .12
BR D #Sta/Elev= 172
  2547.4   52.84 2591.67   52.73 2597.45   52.27 2625.89   52.23  2746.9   51.62
 2943.15   51.24 2954.36   51.18 2960.48   51.11 2966.26   51.43 2972.03   51.41
  2977.8   51.12 3002.83   50.76 3012.45   50.72  3040.8   50.21 3052.88   49.81
 3075.97   49.58 3112.55   48.61 3116.39   48.33 3122.16   47.62 3124.09   47.63
 3127.24   48.03 3129.87   48.43 3133.72    48.8 3135.64    48.8 3139.49   48.96
 3187.61   48.38 3355.08   48.41 3360.85   48.32 3594.01   48.46 3661.71   49.26
  3749.6   50.28 3836.05   50.81 3878.64   50.66 3895.96   50.02 3897.89   50.17
 3901.74   50.62 3907.52   50.79 3919.06    50.5 3922.49   50.49 4089.92    50.6
 4098.07   50.59 4103.85   51.08 4132.73   51.36 4134.73    51.3 4142.42   50.96
 4150.12   50.43 4165.52   50.09 4181.81   50.18 4215.57   50.25 4232.89   49.91
 4244.44   50.05 4252.14   50.35 4257.92   50.33 4261.77   50.07 4269.46   49.85
 4317.59   49.85 4323.36   50.04 4346.46   49.92 4354.69   50.08 4358.01   50.17
 4365.71   50.07 4371.48   49.81 4383.03   49.87 4454.25   50.49 4460.03   50.79
 4476.12   50.46 4495.36   49.99 4503.06   49.74 4528.09    49.8 4614.71   49.98
 4628.18   50.36 4683.16    50.1 4685.58   46.75 4693.63   46.75  4699.4   46.63
 4778.32   47.92 4786.02    47.8 4789.87   47.87 4801.42   48.09 4809.13   48.44
 4814.89   48.53  4814.9   48.53 4837.99   48.36 4848.09   48.17 4850.54   47.96
 4850.55   47.96 4858.82   45.19  4877.1   43.33  4916.1   30.33 4929.48   26.96
  4939.3   26.76 4948.19   25.87 4967.69   19.36 4970.63   18.62 4984.99   18.33
 4985.49    18.3 4988.68   18.07 4989.02   18.04 4990.91   17.62 4991.04   17.58
    4993   16.99 4995.23   16.24 4995.75   16.11 4996.42      16 4998.47   15.81
 4999.27   15.77 5000.14   15.74 5000.92   15.73 5002.16   15.73 5002.94   15.75
 5003.74   15.86 5003.95   15.89 5004.29   15.99 5008.88   17.51 5009.21   17.59
 5011.18   18.02 5011.26   18.04 5013.38   18.25 5013.66   18.27 5015.57   18.33
 5029.39   18.62 5031.01   19.01 5053.05   26.35 5055.82   26.67 5072.76   27.01
 5076.91      28 5136.82   47.97 5142.56   48.39 5151.26    48.6 5151.42   48.59
 5176.84   47.95 5195.98   47.99 5219.78   47.85 5234.06   47.61 5262.61   47.54
 5284.24   47.35 5320.04   47.63 5353.06   47.44 5362.58    47.5 5381.62   47.34
 5419.69   47.71 5462.54   47.59 5476.82   47.79 5516.86   47.72 5524.42    47.7
  5616.7   47.97 5685.34    48.7 5741.59   48.85 5793.65   48.76 5802.97   48.74
 6002.45   49.39 6053.59   49.11 6109.85   49.76    6130   49.39 6155.88   48.93
 6278.64   50.02 6421.85   50.09 6493.46    50.9 6498.53    50.9 6554.83   50.91
 6635.64   51.21 6983.44   51.64 7128.39   51.67 7209.82   51.69 7260.15   51.76
 7336.31   51.87 7455.32   52.25  7469.6   52.11 7555.27   52.39 7569.55   52.34
 7920.75   53.17 7945.51   52.65
BR D #Mann= 8
  2547.4      .1 4683.16     .05 4848.09    .035 4929.48    .015 5072.76    .035
 5136.82      .1 5516.86     .08    6130     .12
BC Design=,, 0 ,, 0 ,,,,,,
BC HTab HWMax=53.19
BC Use User HTab Curves=0
BC User HTab FreeFlow(D)= 0

Type RM Length L Ch R = 1 ,75765.6 ,390.8,304.85,216.05
BEGIN DESCRIPTION:
Interpolated cross section 0.1 from DS face of Orem Bridge
USACE Sims Bayou Rectification
Reach 7b Bathurst Drive to Robin Boulevard
File No. HSC 409-33
END DESCRIPTION:
XS GIS Cut Line= 6
  3108542.57902713795189.4882031 3109343.509183613793337.3373798
 3109994.550860613793221.8861671 3110570.071691113792029.1779227
 3110814.863196313791193.2402901 3110937.070957113790684.0411772
#Sta/Elev= 30
  2547.4   52.84 2972.03   51.41 3122.16   47.62 3139.49   48.96 3594.01   48.46
 3836.05   50.81 3895.96   50.02 4132.73   51.36 4165.52   50.09 4232.89   49.91
 4683.16    50.1 4685.58   46.75 4848.09   48.17 4858.82   45.19  4877.1   43.33
  4916.1   30.33 4929.48   26.96 4948.19   25.87 4970.63   18.62 4989.02   18.04
 5000.92   15.73 5011.26   18.04 5029.39   18.62 5053.05   26.35 5072.76   27.01
 5136.82   47.97 5516.86   47.72    6130   49.39 6635.64   51.21 7945.51   52.65
#Mann= 6 ,-1 , 0
  2547.4      .1       0 4683.16     .05       0 4848.09    .035       0
 5136.82      .1       0 5516.86     .08       0    6130     .12       0
#XS Ineff= 2 , 0
       0 4848.09   50.21 5136.82       0   47.39
Permanent Ineff=
       F       F
Bank Sta=4848.09,5136.82
XS Rating Curve= 0 ,0
Exp/Cntr=0.5,0.3

Type RM Length L Ch R = 1 ,75449.6 ,772.64,639.87,559.63
BEGIN DESCRIPTION:
INTERPOLATED
USACE Sims Bayou Rectification
Reach 7b Bathurst Drive to Robin Boulevard
File No. HSC 409-33
END DESCRIPTION:
XS GIS Cut Line= 6
  3109766.89481913796447.1963176 3109473.850130313793841.9098615
 3109716.630156613793664.7799664 3109965.100132113793478.4299454
 3110619.420017613792037.2799406 3110907.391226513790957.3801975
#Sta/Elev= 30
 1726.17   53.01 2303.21   51.12 2494.17   48.52 2507.24   47.19 2530.79   49.28
 3240.45   48.84 3822.36   49.92 3880.54   51.08 3925.11   49.17 4325.33   50.52
 4383.81   48.85 4553.84   49.53 4628.55   49.03 4631.84   46.42 4650.63   46.15
 4852.68    47.5 4880.69   41.91 4918.33   29.36 4949.29   25.25 4970.96   18.39
 4988.37   17.87 5000.19    15.5 5011.09    17.8 5030.69    18.7 5055.32   26.44
 5076.26   27.56 5135.73   47.38    5800   48.26 6507.73   50.69 7976.22   52.73
#Mann= 7 ,-1 , 0
 1726.17     .99       0 3240.45      .2       0 3822.36      .1       0
 4852.68    .035       0 5135.73     .12       0    5800     .08       0
 6507.73      .1       0
Bank Sta=4852.68,5135.73
XS Rating Curve= 0 ,0
Exp/Cntr=0.3,0.1

Type RM Length L Ch R = 1 ,74809.7 ,459.61,456.27,453.63
BEGIN DESCRIPTION:
INTERPOLATED
USACE Sims Bayou Rectification
Reach 7b Bathurst Drive to Robin Boulevard
File No. HSC 409-33
END DESCRIPTION:
XS GIS Cut Line= 6
     3109786.303    13798522.536 3110042.896471713797477.8060642
 3110260.314421513794918.8655091 3110812.253458913793567.3869088
  3110879.46042313793159.8793901     3110992.149    13790865.303
#Sta/Elev= 30
   51.61   53.36  939.45   50.52 1233.25   48.33 1253.37   46.31 1289.59   49.94
 2381.48   47.99 2871.28    46.8 2895.42   48.82  3276.8   48.54 3366.31    50.5
 3434.89    47.3 4050.66   49.98 4140.65   47.05 4402.25   47.86 4551.16   45.17
 4792.64   47.69 4862.04   46.14 4922.86   27.39 4943.59   25.99 4968.99   18.18
  4998.7   15.04 5030.04   18.07  5054.3   25.96 5074.92   26.66  5133.5   46.18
  5194.7    48.2 5386.73   45.54 5526.62   46.05 5812.94   47.24 8038.85   52.89
#Mann= 7 ,-1 , 0
   51.61     .99       0 2381.48      .2       0  3276.8      .1       0
 4862.04    .035       0  5133.5      .1       0 5526.62     .08       0
 5812.94      .1       0
Bank Sta=4862.04,5133.5
XS Rating Curve= 0 ,0
Exp/Cntr=0.3,0.1

Type RM Length L Ch R = 1 ,74353.4 ,833.64,812.46,809.69
BEGIN DESCRIPTION:
Cross Section 75983.2
USACE Sims Bayou Rectification
Reach 7a Robin Boulevard to SH-288
File No. HSC 409-31
END DESCRIPTION:
XS GIS Cut Line= 6
      3110118.03     13799812.35      3110290.86     13798798.94
      3110290.86     13795703.74      3110495.18     13794840.89
      3110876.17     13794120.32      3111025.26     13790761.78
#Sta/Elev= 30
 -1107.7    53.6   360.3    48.2   385.3    45.7   430.3    50.4  1786.8   47.41
  2350.3    47.2  2395.3    45.3  2425.3    47.9  2899.1   47.58  3010.3    50.1
  3095.5      46  3860.5    49.6  3972.3    45.8  4297.3    46.7  4482.3    44.5
  4782.3    47.3 4868.52   45.19    4926   26.03 4945.59   25.63 4969.59   17.63
 4997.67   14.72 5029.59   17.63 5053.59   25.63    5074   26.03 5131.96   45.35
  5194.1    48.3  5389.1    44.7  5821.9   46.53  7223.9    50.5  8082.2      53
#Mann= 8 ,-1 , 0
 -1107.7     .99       0  1786.8      .2       0  2899.1      .1       0
 4868.52    .035       0 5131.96     .12       0  5821.9     .06       0
  7223.9      .1       0  8082.2      .2       0
Bank Sta=4868.52,5131.96
XS Rating Curve= 0 ,0
Exp/Cntr=0.3,0.1

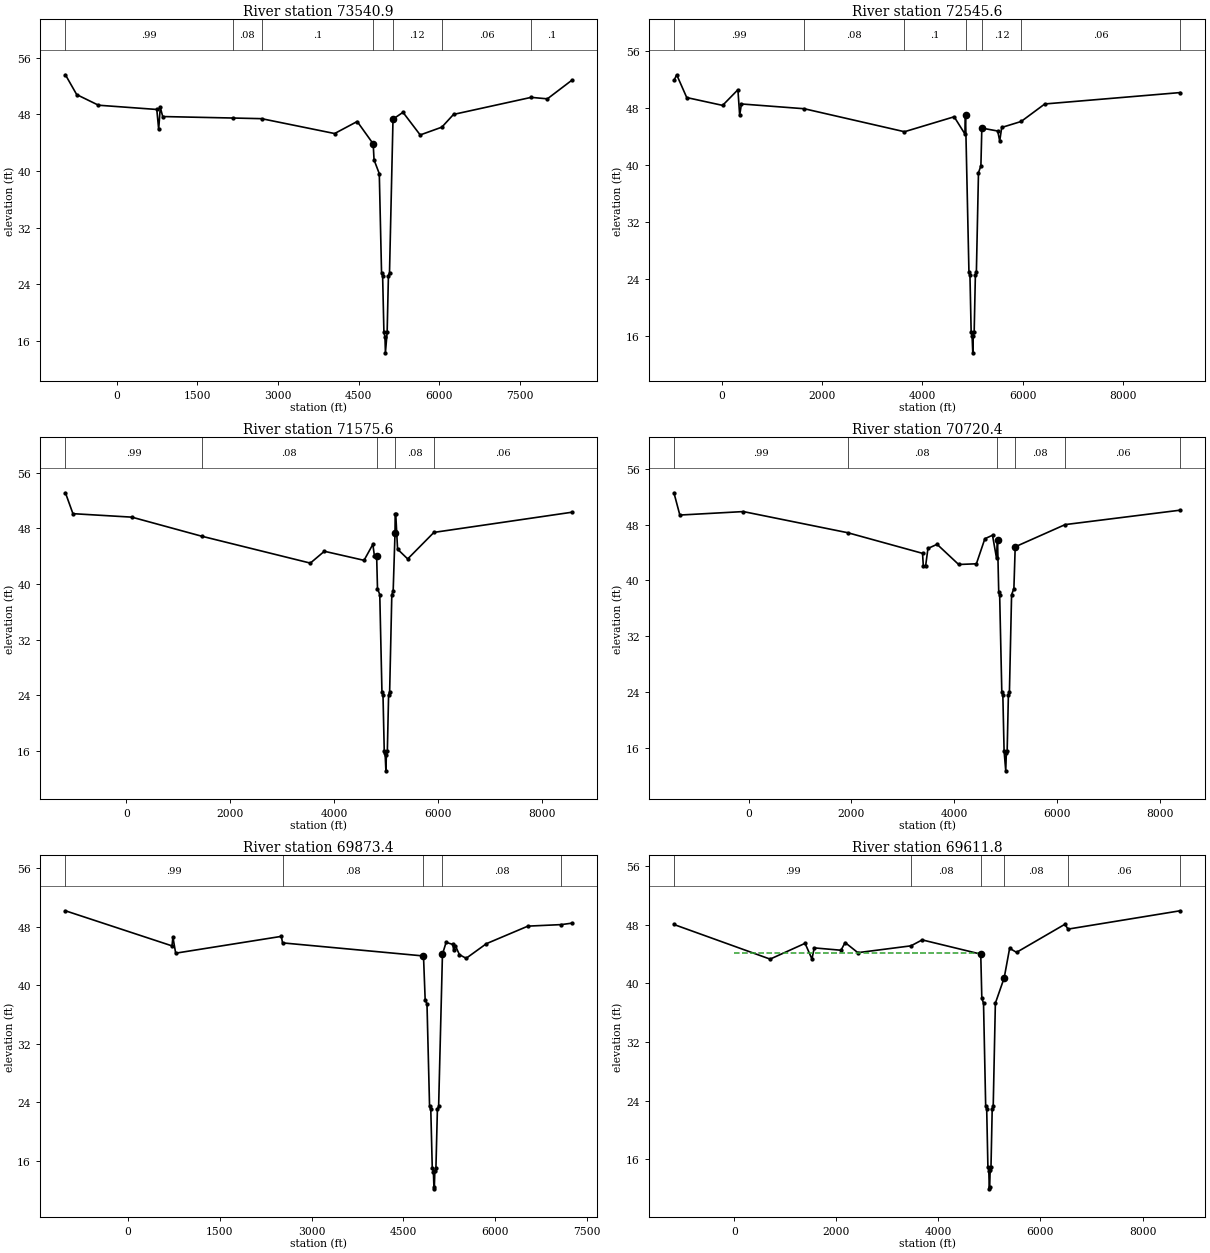
Type RM Length L Ch R = 1 ,73540.9 ,981.57,995.3,1008.08
BEGIN DESCRIPTION:
Cross Section 75099.2
USACE Sims Bayou Rectification
Reach 7a Robin Boulevard to SH-288
File No. HSC 409-31
END DESCRIPTION:
XS GIS Cut Line= 6
     3110386.359     13799736.29      3110688.32     13796315.18
      3111306.86     13795246.73      3111696.14     13794004.36
      3111696.14     13793014.61     3111018.897    13790685.432
#Sta/Elev= 30
  -952.2    53.6  -742.2    50.8  -337.2    49.3     747    48.7     782    45.9
     812      49     857    47.7  2165.9   47.49  2695.2    47.4  4053.5    45.3
  4473.2      47 4770.83   43.84 4786.49   41.58    4884   39.63    4926   25.63
    4946   25.23    4970   17.23 4989.55   16.58 4997.89   14.32    5030   17.23
    5054   25.23    5074   25.63 5139.08   47.33  5324.7    48.3  5644.7    45.1
  6046.9    46.2  6264.4      48    7709   50.41  8009.4    50.2  8459.6    52.8
#Mann= 7 ,-1 , 0
  -952.2     .99       0  2165.9     .08       0  2695.2      .1       0
 4770.83    .035       0 5139.08     .12       0  6046.9     .06       0
    7709      .1       0
Bank Sta=4770.83,5139.08
XS Rating Curve= 0 ,0
Exp/Cntr=0.3,0.1

Type RM Length L Ch R = 1 ,72545.6 ,971.48,970.09,960.99
BEGIN DESCRIPTION:
Cross Section 74118.1
USACE Sims Bayou Rectification
Reach 7a Robin Boulevard to SH-288
File No. HSC 409-31
END DESCRIPTION:
XS GIS Cut Line= 6
      3110560.17      13800000.4      3112006.49     13797772.27
      3112524.38     13795197.03      3112532.66     13794666.96
      3113220.11     13793263.08      3113816.45      13790633.4
#Sta/Elev= 30
    -953    51.9    -898    52.7    -698    49.5      17    48.4     322    50.6
     357      47     392    48.6  1643.5   47.93  3641.3    44.7  4631.3    46.8
    4845   44.39 4857.31   47.06    4926   24.95    4946   24.55    4970   16.55
 4988.46   16.03 5002.44   13.64 5011.15   15.96    5030   16.55    5054   24.55
    5074   24.95    5116   38.95 5164.14   39.91 5182.67   45.21    5499    44.8
    5539    43.4    5579    45.3  5966.2   46.14  6437.5    48.6  9133.9    50.2
#Mann= 7 ,-1 , 0
    -953     .99       0  1643.5     .08       0  3641.3      .1       0
 4857.31    .035       0 5182.67     .12       0  5966.2     .06       0
  9133.9      .2       0
Bank Sta=4857.31,5182.67
XS Rating Curve= 0 ,0
Exp/Cntr=0.3,0.1

Type RM Length L Ch R = 1 ,71575.6 ,754.56,855.13,995.21
BEGIN DESCRIPTION:
Cross Section 73146.6
USACE Sims Bayou Rectification
Reach 7a Robin Boulevard to SH-288
File No. HSC 409-31
END DESCRIPTION:
XS GIS Cut Line= 6
      3110695.19     13800012.67      3113104.15     13796410.41
       3113410.6     13795209.46      3113567.97     13794439.19
      3113778.73     13792288.63      3114089.77     13791097.22
#Sta/Elev= 30
 -1172.1    53.1 -1027.1    50.1   107.9    49.6    1450   46.87  3546.4      43
  3816.4    44.7  4580.9    43.4  4750.9    45.7  4780.9      44 4823.46   44.09
 4840.06   39.35    4884   38.47    4926   24.47    4946   24.07    4970   16.07
 4986.09   15.74 5002.04   13.17 5011.17   15.49    5030   16.07    5054   24.07
    5074   24.47    5116   38.47    5142   38.99 5177.68   47.33  5180.9      50
    5192      50    5227      45    5422    43.6  5927.1   47.41  8579.2    50.3
#Mann= 5 ,-1 , 0
 -1172.1     .99       0    1450     .08       0 4823.46    .035       0
 5177.68     .08       0  5927.1     .06       0
Bank Sta=4823.46,5177.68
XS Rating Curve= 0 ,0
Exp/Cntr=0.3,0.1

Type RM Length L Ch R = 1 ,70720.4 ,970.6,847.04,623.59
BEGIN DESCRIPTION:
Cross Section 72138.2
USACE Sims Bayou Rectification
Reach 7a Robin Boulevard to SH-288
File No. HSC 409-31
END DESCRIPTION:
XS GIS Cut Line= 6
     3110770.189    13800226.572      3112246.73     13797830.43
      3113283.25     13796786.59      3113543.12     13795776.81
      3114586.71     13794708.37     3114514.109    13791723.387
#Sta/Elev= 30
 -1454.1    52.6 -1339.1    49.4  -104.1    49.9  1929.3   46.86  3383.5    43.9
  3398.5    42.1  3443.5    42.1  3488.5    44.6  3666.2    45.2  4086.2    42.3
  4431.2    42.4  4596.2      46  4744.8    46.5    4823   43.21  4842.8   45.77
    4866   38.31    4884   37.95    4926   23.95    4946   23.55    4970   15.55
 5002.37   12.66 5013.89    15.2    5030   15.55    5054   23.55    5074   23.95
    5116   37.95 5161.07   38.85 5186.59   44.84  6158.8   48.03  8395.3    50.1
#Mann= 6 ,-1 , 0
 -1454.1     .99       0  1929.3     .08       0    4823    .035       0
 5186.59     .08       0  6158.8     .06       0  8395.3      .2       0
Bank Sta=4842.8,5186.59
XS Rating Curve= 0 ,0
Exp/Cntr=0.3,0.1

Type RM Length L Ch R = 1 ,69873.4 ,315.64,261.64,229.24
BEGIN DESCRIPTION:
Cross Section 71307.0 - Interpolated
USACE Sims Bayou Rectification
Reach 7a Robin Boulevard to SH-288
File No. HSC 409-31
END DESCRIPTION:
XS GIS Cut Line= 6
      3112757.35     13800749.16       3114996.9     13795939.15
      3115110.08     13795333.31      3114664.02     13793988.48
      3114497.58     13793435.91      3114504.24     13793089.71
#Sta/Elev= 30
 -1018.7    50.2   721.3    45.4   736.3    46.6   781.3    44.4  2506.3    46.7
  2526.1   45.81    4827   44.02 4854.16   38.05    4884   37.45    4926   23.45
    4946   23.05    4970   15.05 4988.69   14.53 4998.04   12.17 5004.11   12.39
 5012.18    14.6    5030   15.05    5054   23.05    5074   23.45 5136.41   44.26
  5196.1   45.88  5303.4    45.6  5318.4    44.9  5348.4    45.4  5413.4    44.2
  5523.4    43.7  5853.7    45.7  6531.2    48.1  7076.8   48.31  7244.5    48.5
#Mann= 5 ,-1 , 0
 -1018.7     .99       0  2526.1     .08       0    4827    .035       0
 5136.41     .08       0  7076.8     .06       0
Bank Sta=4827,5136.41
XS Rating Curve= 0 ,0
Exp/Cntr=0.3,0.1

Type RM Length L Ch R = 1 ,69611.8 ,35.1,35.99,33.85
BEGIN DESCRIPTION:
TIMBER BRIDGE DELETED MAY 2014 WPM Upstream Section of Bridge/Culvert/Weir
USACE Sims Bayou Rectification
Reach 7a Robin Boulevard to SH-288
File No. HSC 409-31
END DESCRIPTION:
XS GIS Cut Line= 6
      3114471.46    13801475.043      3115586.89     13796536.93
      3115305.78     13795200.22      3114903.36     13794349.06
       3114571.9     13793424.04     3114613.913     13791859.12
#Sta/Elev= 30
 -1184.2   48.01   700.8   43.29  1385.8   45.44  1520.8   43.31  1565.8   44.82
  2090.8    44.5  2170.8   45.55  2420.8   44.17  3461.6    45.1  3681.6   45.91
 4829.57   43.97 4850.66   37.94    4884   37.28    4926   23.28    4946   22.88
    4970   14.88  4987.2   14.47 4997.65   11.97 5004.13   12.18 5013.64   14.52
    5030   14.88    5054   22.88    5074   23.28    5116   37.28 5289.08   40.74
  5395.6   44.77  5530.6   44.21  6478.6   48.04    6540   47.38    8737   49.88
#Mann= 6 ,-1 , 0
 -1184.2     .99       0  3461.6     .08       0 4829.57    .035       0
 5289.08     .08       0    6540     .06       0    8737      .2       0
#XS Ineff= 2 , 0
       0  4816.2   44.12 5395.75       0   44.22
Permanent Ineff=
       F       F
Bank Sta=4829.57,5289.08
XS Rating Curve= 0 ,0
Exp/Cntr=0.3,0.1