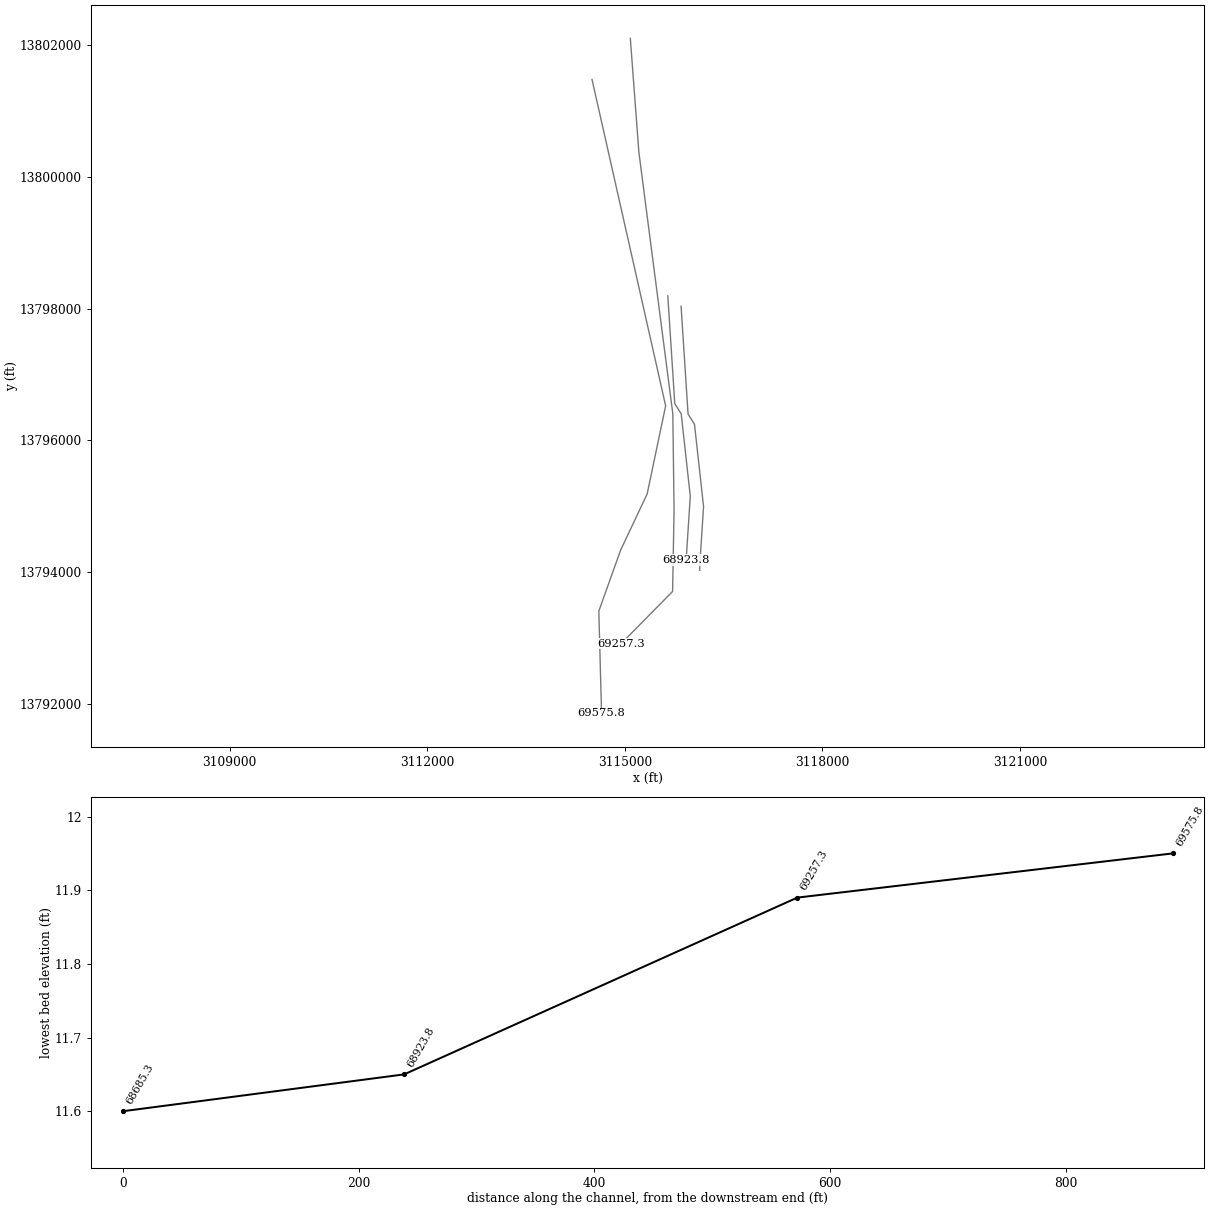
HEC-RAS study C100-00-00.prj: C100-00-00

--- C100-00-00.g01 (geometry) --- (continued)

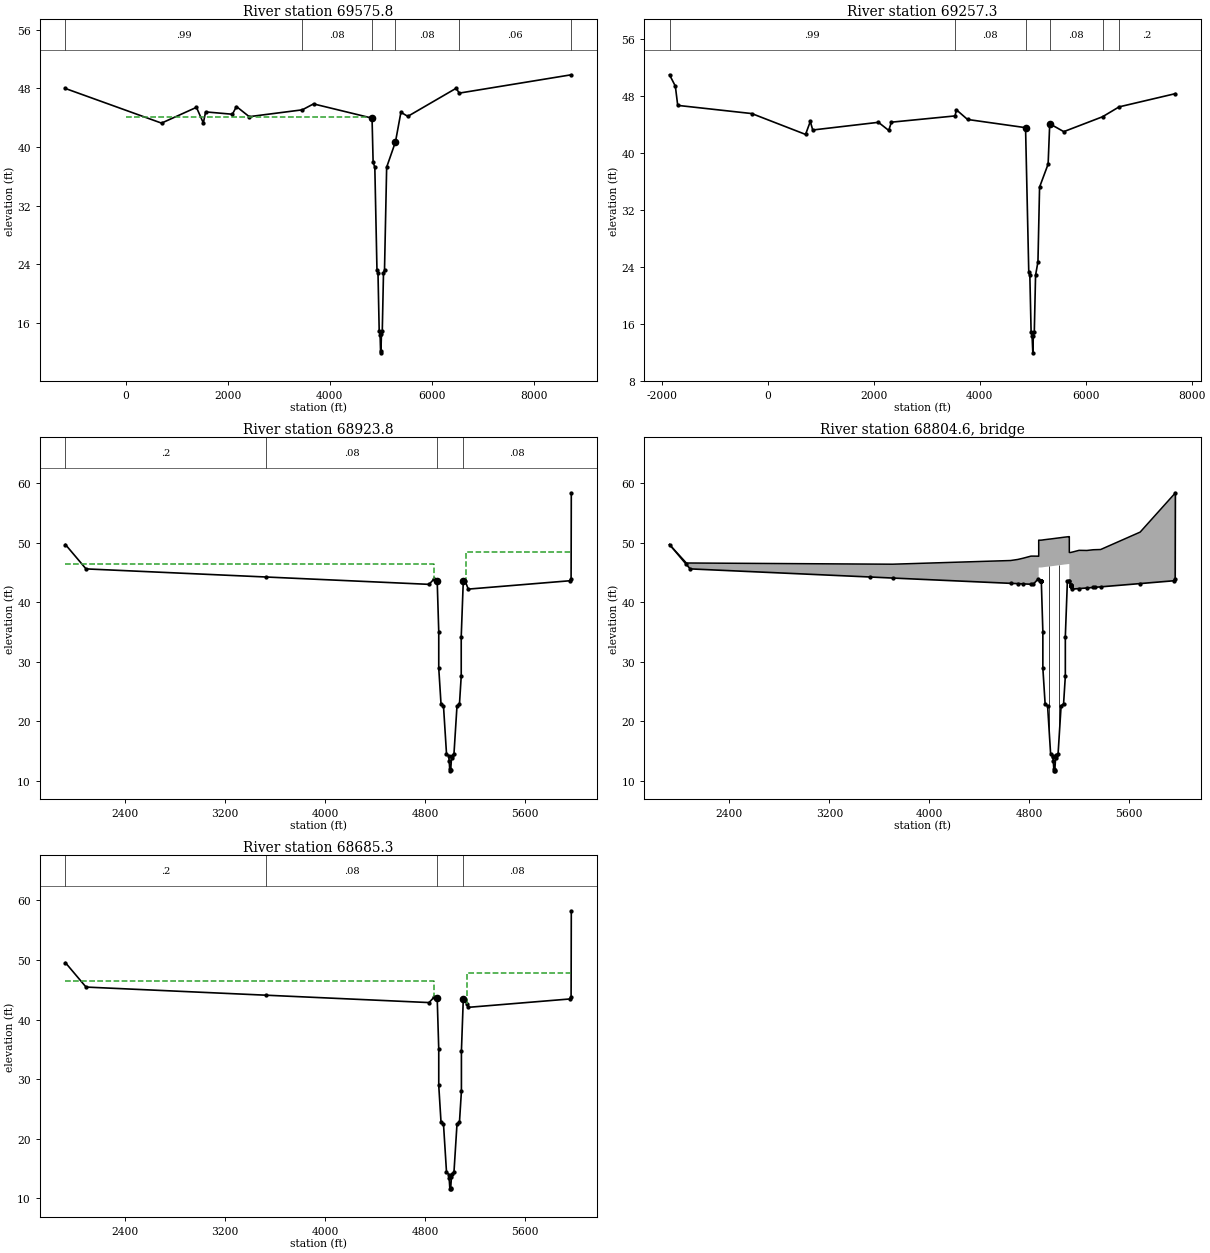
Type RM Length L Ch R = 1 ,69575.8 ,280.11,318.47,471.78
BEGIN DESCRIPTION:
Downstream Section of Bridge/Culvert/Weir
USACE Sims Bayou Rectification
Reach 7a Robin Boulevard to SH-288
File No. HSC 409-31
END DESCRIPTION:
XS GIS Cut Line= 6
     3114500.394    13801476.336      3115618.79     13796525.15
      3115337.68     13795188.44      3114935.26     13794337.28
       3114603.8     13793412.26     3114645.445    13791860.747
#Sta/Elev= 30
 -1184.2   47.99   700.8   43.27  1385.8   45.42  1520.8   43.29  1565.8    44.8
  2090.8   44.48  2170.8   45.53  2420.8   44.15  3461.6   45.08  3681.6   45.89
 4829.57   43.95 4850.66   37.92    4884   37.26    4926   23.26    4946   22.86
    4970   14.86  4987.2   14.45 4997.65   11.95 5004.13   12.16 5013.64    14.5
    5030   14.86    5054   22.86    5074   23.26    5116   37.26 5289.08   40.72
  5395.6   44.75  5530.6   44.19  6478.6   48.02    6540   47.36    8737   49.86
#Mann= 6 ,-1 , 0
 -1184.2     .99       0  3461.6     .08       0 4829.57    .035       0
 5289.08     .08       0    6540     .06       0    8737      .2       0
#XS Ineff= 2 , 0
       0  4816.2   44.12 5395.75       0   44.22
Permanent Ineff=
       F       F
Bank Sta=4829.57,5289.08
XS Rating Curve= 0 ,0
Exp/Cntr=0.3,0.1

Type RM Length L Ch R = 1 ,69257.3 ,313.22,333.46,282.56
BEGIN DESCRIPTION:
Cross Section 70603.0 - Interpolated
USACE Sims Bayou Rectification
Reach 7a Robin Boulevard to SH-288
File No. HSC 409-31
END DESCRIPTION:
XS GIS Cut Line= 6
     3115082.237    13802099.668      3115212.01     13800373.43
      3115727.72      13796403.9      3115746.54     13794933.86
      3115724.13     13793710.14       3114940.7    13792916.993
#Sta/Elev= 30
 -1855.1   50.96 -1745.1   49.37 -1700.1   46.66  -302.2   45.51   712.8   42.58
   802.8   44.41   847.8    43.2  2087.8   44.28  2282.8   43.14  2332.8    44.3
  3535.5   45.18  3557.8   46.05  3770.6   44.68 4864.98   43.53    4926   23.19
    4946   22.79    4970   14.79 4988.31   14.28 5002.46   11.89  5011.3   14.21
    5030   14.79    5054   22.79 5099.09   24.68 5129.63   35.18 5291.09   38.41
  5321.3   44.08  5586.3   42.97  6317.7   45.06  6630.5   46.45  7693.3   48.31
#Mann= 6 ,-1 , 0
 -1855.1     .99       0  3535.5     .08       0 4864.98    .035       0
  5321.3     .08       0  6317.7     .06       0  6630.5      .2       0
Bank Sta=4864.98,5321.3
XS Rating Curve= 0 ,0
Exp/Cntr=0.5,0.3

Type RM Length L Ch R = 1 ,68923.8 ,228.07,238.57,241.39
BEGIN DESCRIPTION:
Upstream Section of Bridge/Culvert/Weir
USACE Sims Bayou Rectification
Reach 7a Robin Boulevard to SH-288
File No. HSC 409-31
END DESCRIPTION:
XS GIS Cut Line= 6
      3115651.37     13798193.59      3115757.55     13796557.28
      3115855.01      13796404.6      3115992.92     13795154.37
      3115937.64     13794305.89      3115934.25     13794187.82
#Sta/Elev= 30
  1921.3   49.71  2086.3   45.61  3522.7   44.25  4830.4   43.01  4870.4   43.91
  4885.4   43.51  4895.6   43.61 4908.05   35.08 4908.05   28.94    4926   22.96
    4946   22.56    4970   14.56 4987.12   14.16 4991.51   13.34 4995.91   11.88
 5001.98   11.65 5003.49   11.76 5010.18   13.81 5012.39   14.12    5030   14.56
    5054   22.56    5074   22.96 5087.83   27.57 5087.83   34.22  5104.4   43.61
  5120.4   43.51  5144.1   42.21  5954.1   43.61  5966.8   43.91  5968.4   58.41
#Mann= 4 ,-1 , 0
  1921.3      .2       0  3522.7     .08       0  4895.6    .035       0
  5104.4     .08       0
#XS Ineff= 2 , 0
       0  4873.5    46.4 5123.91       0   48.37
Permanent Ineff=
       F       F
Bank Sta=4895.6,5104.4
XS Rating Curve= 0 ,0
Exp/Cntr=0.5,0.3

Type RM Length L Ch R = 3 ,68804.6 ,,,
BEGIN DESCRIPTION:
HWY 288
Structure ID: C00-33
END DESCRIPTION:
Bridge Culvert--1,0,-1,-1, 0
Deck Dist Width WeirC Skew NumUp NumDn MinLoCord MaxHiCord MaxSubmerge Is_Ogee
2.56,236,2.6,0, 53, 54, , , 0.95, 0, 1,1,,
  1921.3  2056.4  2086.3  3522.7  3706.4  4650.5    4708  4750.6  4813.1  4830.4
  4870.4 4874.85 4874.85  4890.2 4890.31  4892.2 4892.31  4892.4  4892.5  4895.6
 4896.47 4905.17 4917.35 4939.97 4963.81 4965.29 5034.71 5036.19 5060.03 5082.65
 5094.83 5103.53  5104.4  5115.4 5119.75 5119.75 5129.91  5130.4  5132.3 5132.39
  5132.5  5132.6  5135.4  5144.1  5197.4  5260.9  5310.7  5324.1  5370.3  5686.4
  5954.1  5966.8  5968.4
    49.7    46.6    46.6   46.42    46.4   47.02    47.2   47.41   47.76   47.76
   47.75   47.74   50.44   50.44   50.44   50.44   50.44   50.44   50.44   50.45
   50.45   50.47   50.51   50.57   50.63   50.63   50.82   50.82   50.89   50.95
   50.98      51      51   51.03   51.03   48.37   48.37   48.37   48.38   48.38
   48.38   48.38    48.4   48.44   48.73   48.71   48.83   48.84   48.87    51.8
   58.07   58.36    58.4
                                                                                
                   45.84   45.84   45.84   45.84   45.84   45.84   45.84   45.85
   45.85   45.87   45.91   45.97   46.03   46.03   46.22   46.22   46.29   46.35
   46.38    46.4    46.4   46.43   46.43
                                                                                
                        
  1921.3  2056.4  2086.3  3522.7  3706.4  4650.5    4708  4750.6  4813.1  4830.4
  4870.4 4874.85 4874.85 4890.09  4890.2 4890.31  4892.2 4892.31  4892.4  4892.5
  4895.6 4896.47 4905.17 4917.35 4939.97 4963.81 4965.29 5034.71 5036.19 5060.03
 5082.65 5094.83 5103.53  5104.4  5115.4 5119.75 5119.75 5129.91  5130.4  5132.3
 5132.39  5132.5  5132.6  5135.4  5144.1  5197.4  5260.9  5310.7  5324.1  5370.3
  5686.4  5954.1  5966.8  5968.4
    49.7    46.6    46.6   46.42    46.4   47.02    47.2   47.41   47.76   47.76
   47.75   47.74   50.44   50.44   50.44   50.44   50.44   50.44   50.44   50.44
   50.45   50.45   50.47   50.51   50.57   50.63   50.63   50.82   50.82   50.89
   50.95   50.98      51      51   51.03   51.03   48.37   48.37   48.37   48.38
   48.38   48.38   48.38    48.4   48.44   48.73   48.71   48.83   48.84   48.87
    51.8   58.07   58.36    58.4
                                                                                
                   45.69   45.69   45.69   45.69   45.69   45.69   45.69   45.69
    45.7    45.7   45.72   45.76   45.82   45.88   45.88   46.07   46.07   46.14
    46.2   46.23   46.25   46.25   46.28   46.28
                                                                                
                                
Pier Skew, UpSta & Num, DnSta & Num=  ,4960.4, 2 ,4960.4, 2 , 0 , 0 , 0 ,,
     1.4     1.4
   12.98   47.05
     1.4     1.4
   12.83    46.9
Pier Skew, UpSta & Num, DnSta & Num=  ,5040.4, 2 ,5040.4, 2 , 0 , 0 , 0 ,,
     1.4     1.4
   17.93   47.27
     1.4     1.4
   17.78   47.12
BR Coef= 1 , 1 , 0 ,1.25, 0 ,,,0.8,0,2,0,
WSPro=,,,, 1 ,,,, 0 ,,,, 0 ,,,,-1 ,-1 ,-1 , 0 , 0 , 0 , 0 , 0
BR U #Sta/Elev= 62
  1921.3   49.71  2056.4   46.35  2086.3   45.61  3522.7   44.25  3706.4   44.07
  4650.5   43.18    4708   43.13  4750.6   43.09  4813.1   43.03  4830.4   43.01
  4870.4   43.91  4885.4   43.51 4890.09   43.56  4890.2   43.56 4890.31   43.56
  4892.2   43.58 4892.31   43.58  4892.4   43.58  4892.5   43.58  4895.6   43.61
 4908.05   35.08 4908.05   28.94    4926   22.96    4946   22.56    4970   14.56
 4987.12   14.16 4989.25   13.92 4991.51   13.34 4995.91   11.88 4997.57   11.66
 5001.98   11.65 5003.49   11.76 5010.18   13.81 5012.39   14.12 5015.03   14.26
    5030   14.56    5054   22.56    5074   22.96 5087.83   27.57 5087.83   34.22
  5104.4   43.61  5115.4   43.61  5120.4   43.51 5129.69   42.86  5129.8   42.85
 5129.91   42.84  5130.4   42.81  5132.3   42.77 5132.39   42.77  5132.5   42.77
  5132.6   42.77  5135.4   42.71  5144.1   42.21  5197.4    42.3  5260.9    42.4
  5310.7   42.49  5324.1   42.51  5370.3   42.59  5686.4   43.14  5954.1   43.61
  5966.8   43.91  5968.4   58.41
BR U #Mann= 4
  1921.3      .2  3522.7     .08  4895.6    .015  5104.4     .08
BR D #Sta/Elev= 54
  1921.3   49.55  2056.4   46.19  2086.3   45.45  3522.7   44.09  3706.4   43.91
  4650.5   43.02    4708   42.97  4750.6   42.93  4813.1   42.87  4830.4   42.85
  4870.4   43.75  4895.6   43.61 4908.05   35.08 4908.05   28.94    4926   22.86
    4946   22.46    4970   14.46 4985.96   14.17 4988.25   13.99 4990.93   13.49
 4995.92   11.82 4996.82   11.65  5002.4    11.6 5003.51   11.69 5009.32   13.54
 5012.41   14.06 5015.01    14.2    5030   14.46    5054   22.46    5074   22.86
 5089.37   27.98 5089.37    34.7  5104.4   43.45  5115.4   43.45  5120.4   43.35
 5129.69    42.7  5129.8   42.69 5129.91   42.68  5130.4   42.65  5132.3   42.61
 5132.39   42.61  5132.5   42.61  5132.6   42.61  5135.4   42.55  5144.1   42.05
  5197.4   42.14  5260.9   42.24  5310.7   42.33  5324.1   42.35  5370.3   42.43
  5686.4   42.98  5954.1   43.45  5966.8   43.75  5968.4   58.25
BR D #Mann= 4
  1921.3      .2  3522.7     .08  4895.6    .015  5104.4     .08
BC Design=,, 0 ,, 0 ,,,,,,
BC HTab HWMax=58.41
BC Use User HTab Curves=0
BC User HTab FreeFlow(D)= 0

Type RM Length L Ch R = 1 ,68685.3 ,446.95,318.43,220.31
BEGIN DESCRIPTION:
Downstream Section of Bridge/Culvert/Weir
USACE Sims Bayou Rectification
Reach 7a Robin Boulevard to SH-288
File No. HSC 409-31
END DESCRIPTION:
XS GIS Cut Line= 6
      3115852.94     13798035.79      3115959.13     13796399.48
      3116056.59      13796246.8       3116194.5     13794996.57
      3116139.22     13794148.09      3116135.83     13794030.01
#Sta/Elev= 30
  1921.3   49.55  2086.3   45.45  3522.7   44.09  4830.4   42.85  4870.4   43.75
  4895.6   43.61 4908.05   35.08 4908.05   28.94    4926   22.86    4946   22.46
    4970   14.46 4988.25   13.99 4990.93   13.49 4996.82   11.65  5002.4    11.6
 5003.51   11.69 5009.32   13.54 5012.41   14.06    5030   14.46    5054   22.46
    5074   22.86 5089.37   27.98 5089.37    34.7  5104.4   43.45  5120.4   43.35
  5130.4   42.65  5144.1   42.05  5954.1   43.45  5966.8   43.75  5968.4   58.25
#Mann= 4 ,-1 , 0
  1921.3      .2       0  3522.7     .08       0  4895.6    .035       0
  5104.4     .08       0
#XS Ineff= 2 , 0
       0  4870.4    46.4 5132.39       0   47.87
Permanent Ineff=
       F       F
Bank Sta=4895.6,5104.4
XS Rating Curve= 0 ,0
Exp/Cntr=0.5,0.3