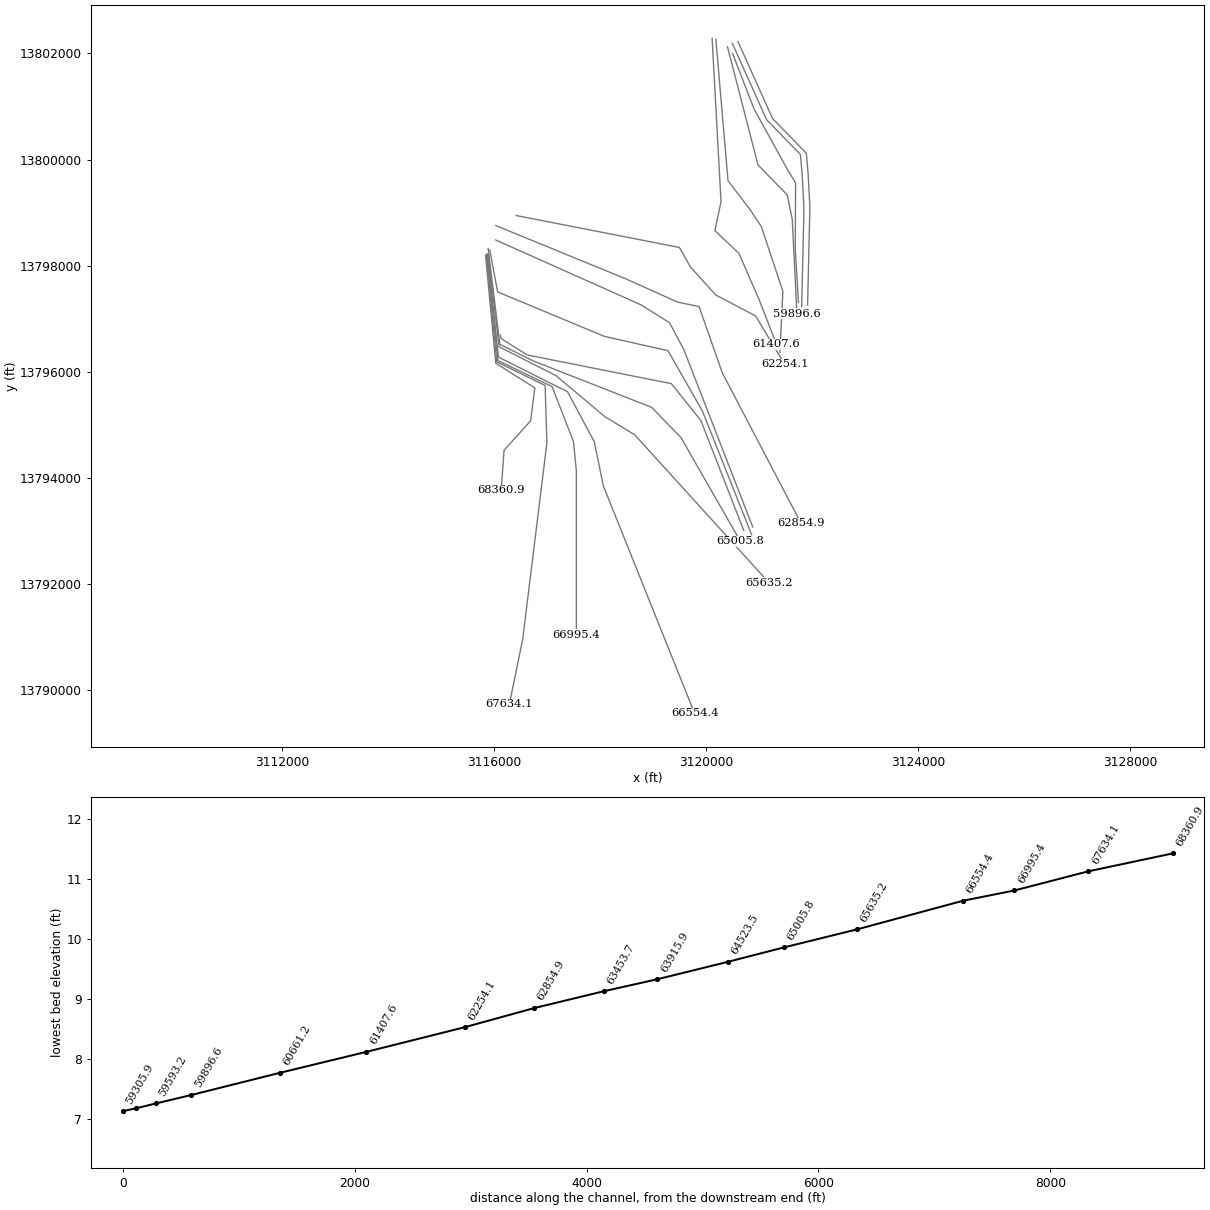
HEC-RAS study C100-00-00.prj: C100-00-00

--- C100-00-00.g01 (geometry) --- (continued)

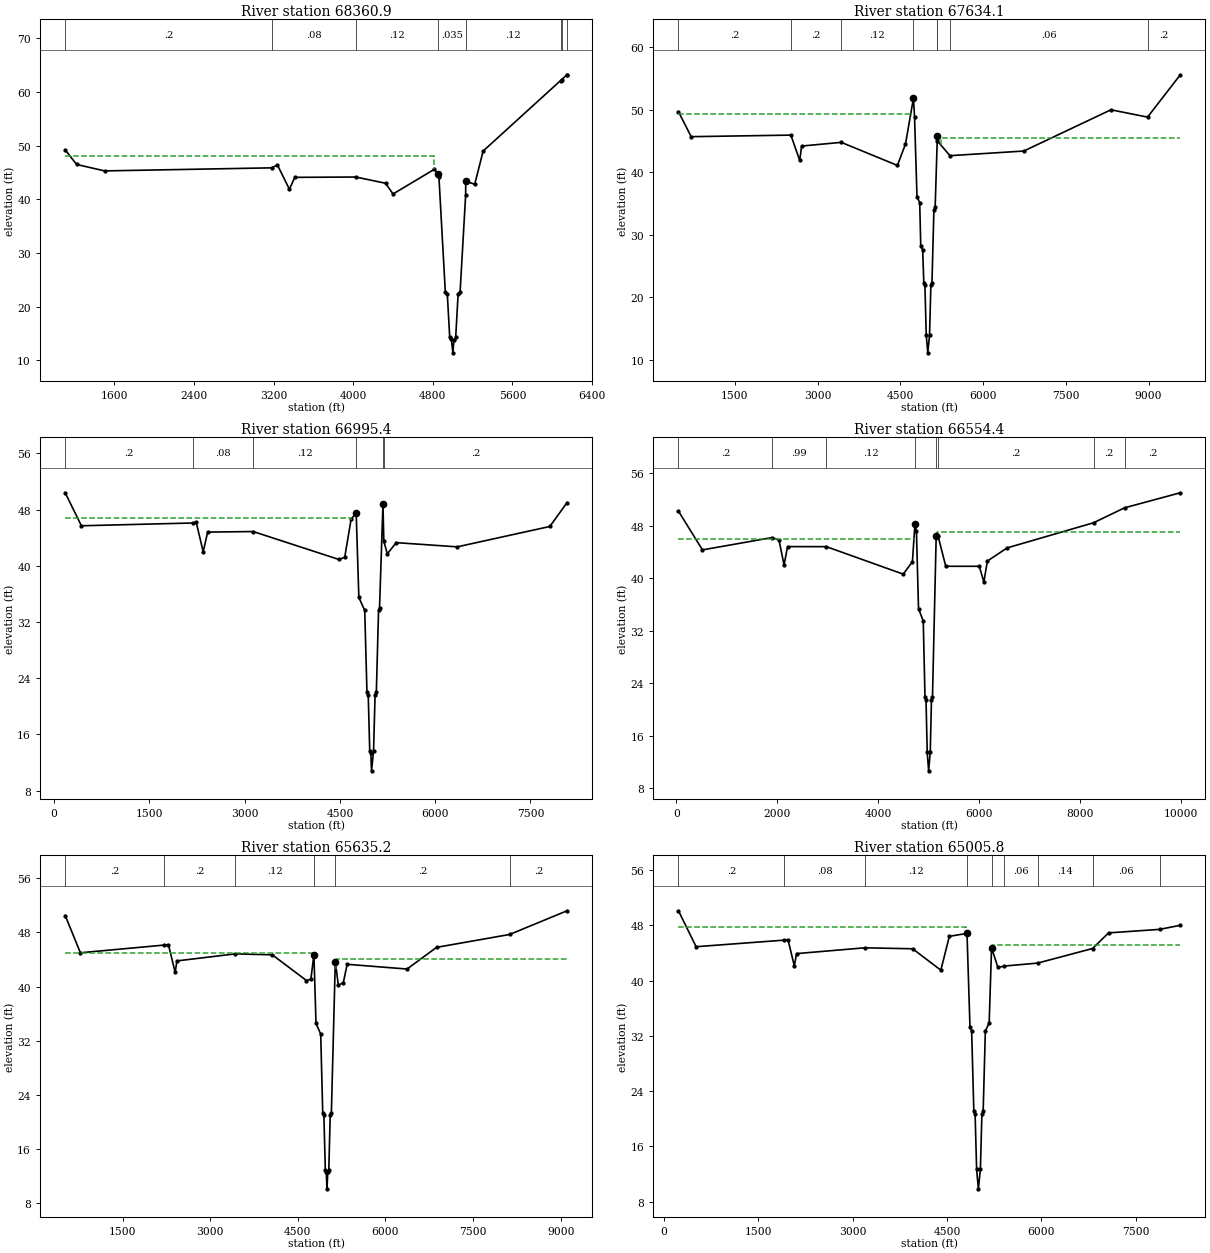
Type RM Length L Ch R = 1 ,68360.9 ,574.5,726.75,817.26
BEGIN DESCRIPTION:
Cross Section 69745.6-Interpolated
USACE Sims Bayou Rectification
Reach 7a Robin Boulevard to SH-288
File No. HSC 409-31
END DESCRIPTION:
XS GIS Cut Line= 6
      3115838.62     13798194.05       3116030.9     13796162.86
      3116767.96     13795697.06      3116686.97     13795076.14
      3116187.53      13794522.7      3116133.54     13793766.79
#Sta/Elev= 30
    1107    49.2  1222.3    46.5  1502.3    45.3  3180.5   45.87  3239.2    46.4
  3359.2    41.9  3414.2    44.1  4027.2   44.16  4325.4      43  4400.4      41
  4815.9    45.6  4850.9    44.7 4861.59   44.16    4926   22.69    4946   22.29
    4970   14.29 4985.96      14    5002   11.42 5011.24   13.75    5030   14.29
    5054   22.29    5074   22.69    5130   40.83  5130.9    43.4  5220.9    42.8
  5305.9      49    6084   62.13  6093.8   62.29  6148.6    63.2  6148.7    63.2
#Mann= 8 ,-1 , 0
    1107      .2       0  3180.5     .08       0  4027.2     .12       0
  4850.9    .035       0  5130.9     .12       0    6084     .08       0
  6093.8     .06       0  6148.6      .2       0
#XS Ineff= 2 , 0
       0    4815      48               0
Permanent Ineff=
       F       F
Bank Sta=4850.9,5130.9
XS Rating Curve= 0 ,0
Exp/Cntr=0.3,0.1

Type RM Length L Ch R = 1 ,67634.1 ,591.06,638.76,667.95
BEGIN DESCRIPTION:
Cross Section 69001.8
USACE Sims Bayou Rectification
Reach 6 Downstream of Cullen to SH-288
File No. HSC 409-16
END DESCRIPTION:
XS GIS Cut Line= 6
      3115853.41     13798198.98      3116050.62     13796187.51
      3116961.56     13795744.41      3116995.32     13794664.16
      3116539.59     13790967.69       3116286.4     13789735.53
#Sta/Elev= 30
   478.1    49.7   708.1    45.7  2515.9   45.95  2676.2    41.9  2711.2    44.2
  3429.7   44.79  4447.3    41.1  4593.1    44.5  4738.1   51.84  4757.8   48.92
  4802.2   36.12 4851.65   35.13  4870.4   28.28    4905   27.59    4926   22.36
    4946   21.96    4970   13.96    4998  11.122 5030.09   13.99    5054   21.96
    5074   22.36 5108.79   33.96 5131.76   34.42 5171.64   45.81  5173.2      45
  5400.3   42.66  6738.2    43.4  8318.4      50    8982   48.83  9576.3    55.6
#Mann= 8 ,-1 , 0
   478.1      .2       0  2515.9      .2       0  3429.7     .12       0
  4738.1    .035       0 5171.64     .06       0  5173.2     .12       0
  5400.3     .06       0    8982      .2       0
#XS Ineff= 2 , 0
       0    4677    49.4    5240       0    45.5
Permanent Ineff=
       F       F
Bank Sta=4738.1,5171.64
XS Rating Curve= 0 ,0
Exp/Cntr=0.3,0.1

Type RM Length L Ch R = 1 ,66995.4 ,425.18,441.01,474.16
BEGIN DESCRIPTION:
Cross Section 68357.1-Interpolated
USACE Sims Bayou Rectification
Reach 6 Downstream of Cullen to SH-288
File No. HSC 409-16
END DESCRIPTION:
XS GIS Cut Line= 6
      3115863.27      13798218.7      3116070.34     13796212.16
      3117091.92     13795724.06      3117496.88     13794684.68
      3117550.87     13794131.25      3117550.87     13791052.23
#Sta/Elev= 30
     176    50.4     431    45.7  2190.3    46.1  2238.2    46.2  2348.2      42
  2418.2    44.8  3135.1   44.88  4485.9    40.9  4575.9    41.2  4675.9    46.6
  4756.4   47.55  4798.6   35.49  4891.2   33.64    4926   22.04    4946   21.64
    4970   13.64  4986.9  13.302    4998  10.802    5030   13.64    5054   21.64
    5074   22.04  5108.8   33.64  5123.8   33.94 5178.02   48.78  5191.9    43.5
  5246.9    41.7  5386.9    43.3  6346.9    42.7  7804.6    45.6    8076      49
#Mann= 6 ,-1 , 0
     176      .2       0  2190.3     .08       0  3135.1     .12       0
  4756.4    .035       0 5178.02     .06       0  5191.9      .2       0
#XS Ineff= 2 , 0
       0    4675   46.75 5178.02       0      46
Permanent Ineff=
       F       F
Bank Sta=4756.4,5178.02
XS Rating Curve= 0 ,0
Exp/Cntr=0.3,0.1

Type RM Length L Ch R = 1 ,66554.4 ,753.37,919.21,1048.81
BEGIN DESCRIPTION:
Cross Section 67910.5
USACE Sims Bayou Rectification
Reach 6 Downstream of Cullen to SH-288
File No. HSC 409-16
END DESCRIPTION:
XS GIS Cut Line= 6
      3115876.59     13798211.31      3116082.64      13796276.7
      3117383.53     13795626.26       3117889.9     13794681.04
      3118058.69     13793853.98      3119780.33     13789566.75
#Sta/Elev= 30
    44.8    50.2   519.8    44.3  1897.4   46.17  2035.3    45.8  2135.3      42
  2205.3    44.8    2973   44.79  4494.8    40.6  4677.1    42.5  4727.1    48.3
 4756.24   47.18  4797.7   35.34  4891.2   33.47    4926   21.87    4946   21.47
    4970   13.47    4998  10.632    5030   13.47    5054   21.47    5074   21.87
  5147.8   46.47 5182.29   46.47  5337.1    41.8  6001.2    41.8  6091.2    39.4
  6161.2    42.6  6551.2    44.6  8263.1   48.43    8877   50.71  9981.2      53
#Mann= 8 ,-1 , 0
    44.8      .2       0  1897.4     .99       0    2973     .12       0
  4727.1    .035       0  5147.8     .12       0 5182.29      .2       0
  8263.1      .2       0    8877      .2       0
#XS Ineff= 2 , 0
       0    4705      46    5162       0    47.1
Permanent Ineff=
       F       F
Bank Sta=4727.1,5147.8
XS Rating Curve= 0 ,0
Exp/Cntr=0.3,0.1

Type RM Length L Ch R = 1 ,65635.2 ,625.23,629.38,658.12
BEGIN DESCRIPTION:
Cross Section 66905.0
USACE Sims Bayou Rectification
Reach 6 Downstream of Cullen to SH-288
File No. HSC 409-16
END DESCRIPTION:
XS GIS Cut Line= 6
      3115884.47     13798227.09      3116095.66     13796472.27
      3117164.11     13795930.08      3118092.44     13795153.65
      3118649.45     13794816.07      3121181.28     13792031.06
#Sta/Elev= 30
   517.4    50.5   777.4      45  2214.8   46.14  2284.9    46.2  2399.9    42.1
  2429.9    43.8  3428.5   44.84    4063    44.7    4648    40.9  4723.2    41.1
  4775.3   44.73 4810.73    34.6  4891.2   32.99    4926   21.39    4946   20.99
    4970   12.99  4986.9  12.652    4998  10.152  5013.1  12.652    5030   12.99
    5054   20.99    5074   21.39 5140.95   43.71  5193.2    40.2  5278.2    40.6
  5344.6    43.3  6369.6    42.6  6874.6    45.8  8124.7    47.7  9108.4    51.2
#Mann= 6 ,-1 , 0
   517.4      .2       0  2214.8      .2       0  3428.5     .12       0
  4775.3    .035       0 5140.95      .2       0  8124.7      .2       0
#XS Ineff= 2 , 0
       0  4775.3      45    5158       0    44.1
Permanent Ineff=
       F       F
Bank Sta=4775.3,5140.95
XS Rating Curve= 0 ,0
Exp/Cntr=0.3,0.1

Type RM Length L Ch R = 1 ,65005.8 ,448.5,482.3,552.09
BEGIN DESCRIPTION:
Cross Section 66238.1-Interpolated
USACE Sims Bayou Rectification
Reach 6 Downstream of Cullen to SH-288
File No. HSC 409-16
END DESCRIPTION:
XS GIS Cut Line= 6
     3115887.099    13798322.086      3116107.62     13796519.92
      3116727.47       13796210.       3118968.2     13795332.61
      3119521.63     13794765.67      3120644.77    13792806.711
#Sta/Elev= 30
   236.3    50.1   516.3    44.9  1914.5   45.85  1976.1    45.9  2076.1    42.1
  2111.1    43.9  3192.9   44.74  3954.1    44.6  4402.1    41.5  4537.1    46.4
 4817.46   46.83 4864.94   33.21  4891.2   32.69    4926   21.09    4946   20.69
    4970   12.69    4998   9.852    5030   12.69    5054   20.69    5074   21.09
  5108.8   32.69 5169.47    33.9  5207.4   44.74  5308.1    41.9  5412.3    42.1
  5940.3   42.53  6810.7   44.64  7065.4    46.9  7877.2   47.41  8204.4      48
#Mann= 9 ,-1 , 0
   236.3      .2       0  1914.5     .08       0  3192.9     .12       0
 4817.46    .035       0  5207.4     .12       0  5412.3     .06       0
  5940.3     .14       0  6810.7     .06       0  7877.2      .2       0
#XS Ineff= 2 , 0
       0    4800    47.8  5207.4       0    45.1
Permanent Ineff=
       F       F
Bank Sta=4817.46,5207.4
XS Rating Curve= 0 ,0
Exp/Cntr=0.3,0.1

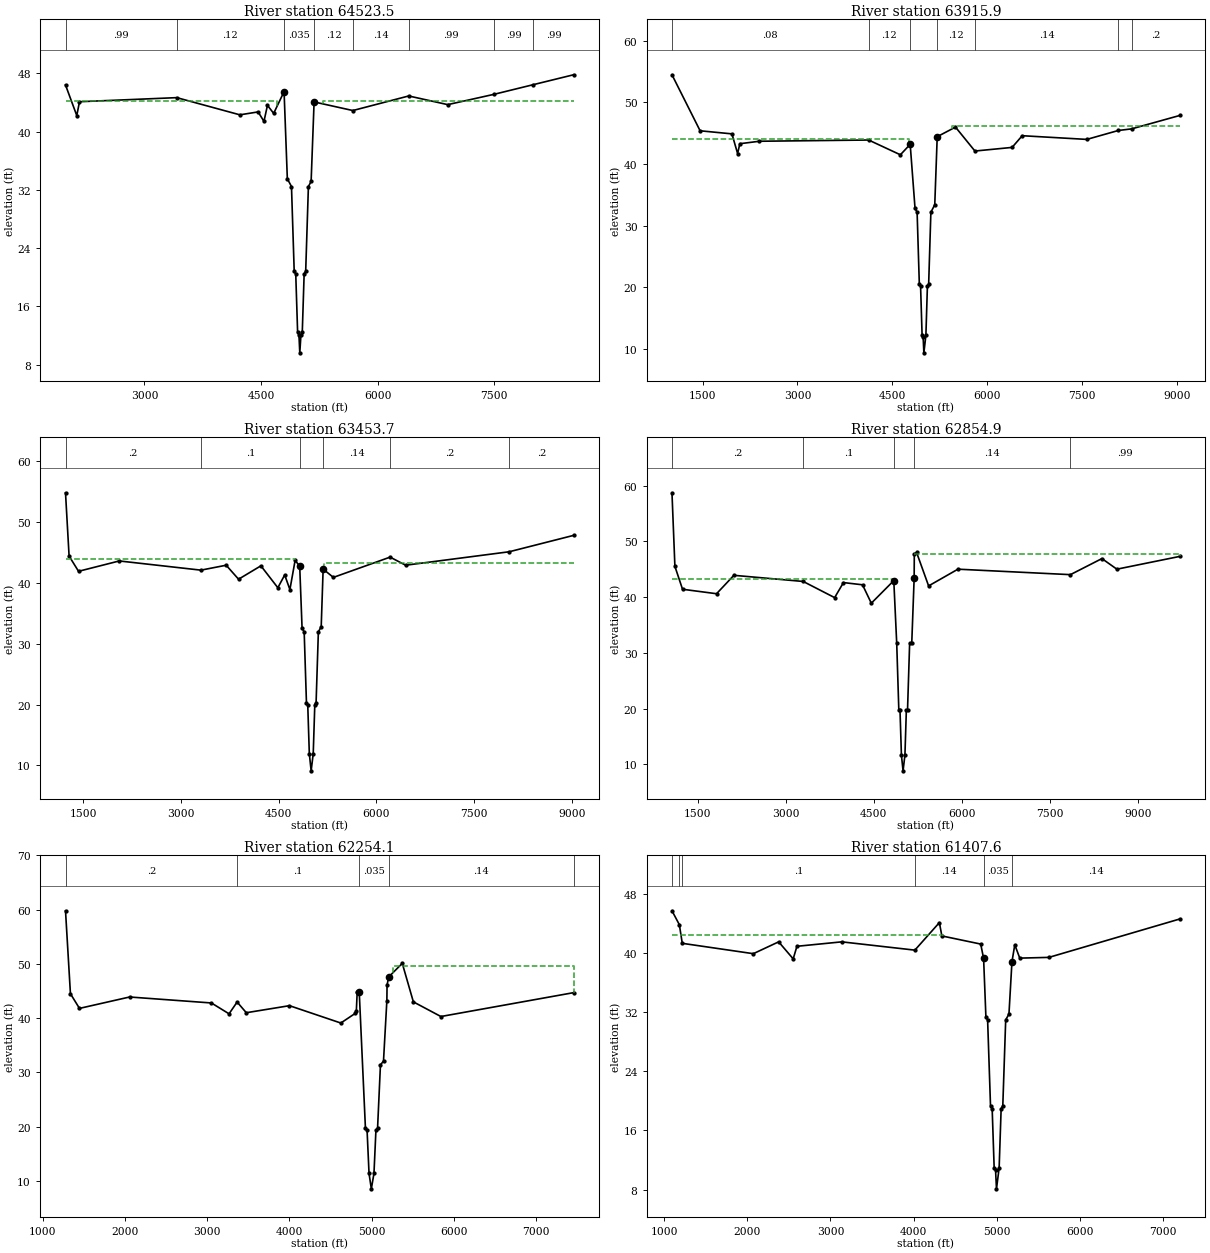
Type RM Length L Ch R = 1 ,64523.5 ,609.36,607.54,610.41
BEGIN DESCRIPTION:
Cross Section 65743.9
USACE Sims Bayou Rectification
Reach 6 Downstream of Cullen to SH-288
File No. HSC 409-16
END DESCRIPTION:
XS GIS Cut Line= 6
      3116120.38     13796691.93      3116128.86     13796629.51
      3116623.98     13796318.29      3119341.48     13795778.17
      3119898.48     13795086.14      3120708.67     13793010.04
#Sta/Elev= 30
  1984.2    46.4  2129.2    42.2  2164.2    44.1  3415.3   44.66    4227    42.3
    4462    42.7    4537    41.4    4582    43.6    4662    42.5  4795.9   45.49
 4837.81   33.52  4891.2   32.45    4926   20.85    4946   20.45    4970   12.45
  4986.9  12.112    4998   9.612  5013.1  12.112    5030   12.45    5054   20.45
    5074   20.85  5108.8   32.45 5143.78   33.15    5182   44.07  5680.4   42.89
  6399.2   44.89    6901    43.7    7494   45.11  8000.8   46.44  8519.6    47.8
#Mann= 8 ,-1 , 0
  1984.2     .99       0  3415.3     .12       0  4795.9    .035       0
    5182     .12       0  5680.4     .14       0  6399.2     .99       0
    7494     .99       0  8000.8     .99       0
#XS Ineff= 2 , 0
       0    4702    44.2    5300       0    44.2
Permanent Ineff=
       F       F
Bank Sta=4795.9,5182
XS Rating Curve= 0 ,0
Exp/Cntr=0.3,0.1

Type RM Length L Ch R = 1 ,63915.9 ,605.89,462.28,294.9
BEGIN DESCRIPTION:
Cross Section 65113.1-Interpolated
USACE Sims Bayou Rectification
Reach 6 Downstream of Cullen to SH-288
File No. HSC 409-16
END DESCRIPTION:
XS GIS Cut Line= 6
     3115916.999    13798296.954      3116066.05     13797505.84
      3118077.31     13796668.94      3119278.66     13796398.98
      3119926.58     13795265.11     3120856.854     13792932.29
#Sta/Elev= 30
  1015.5    54.5  1460.5    45.4  1963.3    44.9  2053.3    41.7  2088.3    43.3
  2398.3    43.7  4124.6    43.9  4626.7    41.5  4781.7    43.2  4858.2   32.82
  4891.2   32.16    4926   20.56    4946   20.16    4970   12.16  4986.9  11.822
    4998   9.322    5030   12.16    5054   20.16    5074   20.56  5108.8   32.16
 5170.31   33.39    5209   44.44    5498      46  5805.2   42.11    6393    42.7
    6553    44.6    7574      44  8073.1   45.45  8281.6   45.71  9047.7    47.9
#Mann= 7 ,-1 , 0
  1015.5     .08       0  4124.6     .12       0  4781.7    .035       0
    5209     .12       0  5805.2     .14       0  8073.1     .06       0
  8281.6      .2       0
#XS Ineff= 2 , 0
       0    4765    44.1    5450       0    46.1
Permanent Ineff=
       F       F
Bank Sta=4781.7,5209
XS Rating Curve= 0 ,0
Exp/Cntr=0.3,0.1

Type RM Length L Ch R = 1 ,63453.7 ,465.34,598.71,706.26
BEGIN DESCRIPTION:
Cross Section 64485.9
USACE Sims Bayou Rectification
Reach 6 Downstream of Cullen to SH-288
File No. HSC 409-16
END DESCRIPTION:
XS GIS Cut Line= 5
      3116029.67     13798484.04       3118767.6     13797263.51
      3119307.72     13796925.93      3119577.78     13796419.57
      3120877.46     13793077.55
#Sta/Elev= 30
  1229.5    54.8  1284.5    44.4  1429.5    41.9  2054.5    43.6    3307   42.09
  3694.5    42.9  3884.5    40.6  4227.2    42.8  4487.2    39.2  4592.2    41.3
  4672.2    38.9  4752.2    43.7 4822.56   42.74  4858.7   32.59  4891.2   31.94
    4926   20.34    4946   19.94    4970   11.96    4998   9.122    5030   11.94
    5054   19.94    5074   20.34  5108.8   31.94 5152.46   32.82    5182   42.26
  5339.1    40.9  6209.5   44.23    6448    42.9  8036.4   45.11  9023.8    47.8
#Mann= 6 ,-1 , 0
  1229.5      .2       0    3307      .1       0 4822.56    .035       0
    5182     .14       0  6209.5      .2       0  8036.4      .2       0
#XS Ineff= 2 , 0
       0  4752.2   43.97    5188       0   43.22
Permanent Ineff=
       F       F
Bank Sta=4822.56,5182
XS Rating Curve= 0 ,0
Exp/Cntr=0.3,0.1

Type RM Length L Ch R = 1 ,62854.9 ,694.79,600.87,530.43
BEGIN DESCRIPTION:
Cross Section 63915.5
USACE Sims Bayou Rectification
Reach 6 Downstream of Cullen to SH-288
File No. HSC 409-16
END DESCRIPTION:
XS GIS Cut Line= 6
      3116030.46      13798756.1      3118480.66       13797753.
      3119459.63     13797314.15      3119864.72     13797229.75
      3120303.58     13795980.72      3121788.92     13793145.07
#Sta/Elev= 30
  1059.3    58.7  1109.3    45.5  1239.3    41.4  1819.3    40.6  2114.3    43.9
  3295.7    42.8  3831.9    39.9  3981.9    42.6  4306.9    42.2  4456.9    38.9
    4840   42.95    4890   31.68    4926   19.68    4946   19.68    4970   11.68
    4998   8.842    5030   11.68    5054   19.68    5074   19.68    5110   31.68
    5146   31.68    5187   43.37  5189.7    47.7  5228.5      48  5433.5      42
  5933.5      45  7850.6   44.02  8387.4    46.9  8642.4      45  9718.5    47.3
#Mann= 5 ,-1 , 0
  1059.3      .2       0  3295.7      .1       0    4840    .035       0
    5187     .14       0  7850.6     .99       0
#XS Ineff= 2 , 0
       0    4840    43.2    5193       0   47.74
Permanent Ineff=
       F       F
Bank Sta=4840,5187
XS Rating Curve= 0 ,0
Exp/Cntr=0.3,0.1

Type RM Length L Ch R = 1 ,62254.1 ,839.93,846.53,858.45
BEGIN DESCRIPTION:
Cross Section 62975.7
USACE Sims Bayou Rectification
Reach 6 Downstream of Cullen to SH-288
File No. HSC 409-16
END DESCRIPTION:
XS GIS Cut Line= 6
     3116416.526    13798944.817      3119493.39     13798343.76
      3119703.25     13797973.88      3120178.53     13797449.42
      3120932.44     13797051.99     3121478.579    13796141.753
#Sta/Elev= 30
  1276.7    59.8  1336.7    44.5  1446.7    41.8  2056.7    43.9  3051.7    42.8
  3266.7    40.8  3364.8   42.97  3476.7      41  4001.7    42.3  4626.7    39.1
  4804.3    40.9 4815.45   41.32 4825.74   44.75 4851.03   44.75    4926   19.76
    4946   19.36    4970   11.36    4998   8.522    5030   11.36    5054   19.36
    5074   19.76  5108.8   31.36 5146.03    32.1    5187   43.24  5189.3    46.1
  5209.3    47.6  5374.5    50.1  5509.5      43  5844.5    40.3  7458.5    44.7
#Mann= 5 ,-1 , 0
  1276.7      .2       0  3364.8      .1       0 4851.03    .035       0
  5209.3     .14       0  7458.5      .2       0
#XS Ineff= 2 , 0
       0 4851.03   44.75    5260       0   49.54
Permanent Ineff=
       F       F
Bank Sta=4851.03,5209.3
XS Rating Curve= 0 ,0
Exp/Cntr=0.3,0.1

Type RM Length L Ch R = 1 ,61407.6 ,793.17,746.33,703.36
BEGIN DESCRIPTION:
Cross Section 62059.0-Interpolated
USACE Sims Bayou Rectification
Reach 6 Downstream of Cullen to SH-288
File No. HSC 409-16
END DESCRIPTION:
XS GIS Cut Line= 6
     3120110.962    13802282.611      3120279.08     13799206.03
      3120163.37     13798660.54        3120615.     13798234.76
      3120992.96     13797370.86     3121324.878    13796521.138
#Sta/Elev= 30
  1092.2    45.7  1181.1   43.82  1216.2    41.3  2071.2    39.9  2376.2    41.5
  2551.2    39.2  2596.2    40.9  3136.2    41.5  4015.5   40.38  4310.6    44.1
  4340.6    42.3  4808.2    41.2  4842.9   39.26 4870.54   31.37  4891.2   30.95
    4926   19.35    4946   18.95    4970   10.95  4986.9  10.612    4998   8.112
    5030   10.95    5054   18.95    5074   19.35  5108.8   30.95 5148.15   31.74
    5184   38.79  5218.2    41.1  5278.2    39.3  5628.9    39.4  7206.9    44.6
#Mann= 6 ,-1 , 0
  1092.2      .2       0  1181.1      .1       0  1216.2      .1       0
  4015.5     .14       0  4842.9    .035       0    5184     .14       0
#XS Ineff= 2 , 0
       0    4355    42.4               0
Permanent Ineff=
       F       F
Bank Sta=4842.9,5184
XS Rating Curve= 0 ,0
Exp/Cntr=0.3,0.1

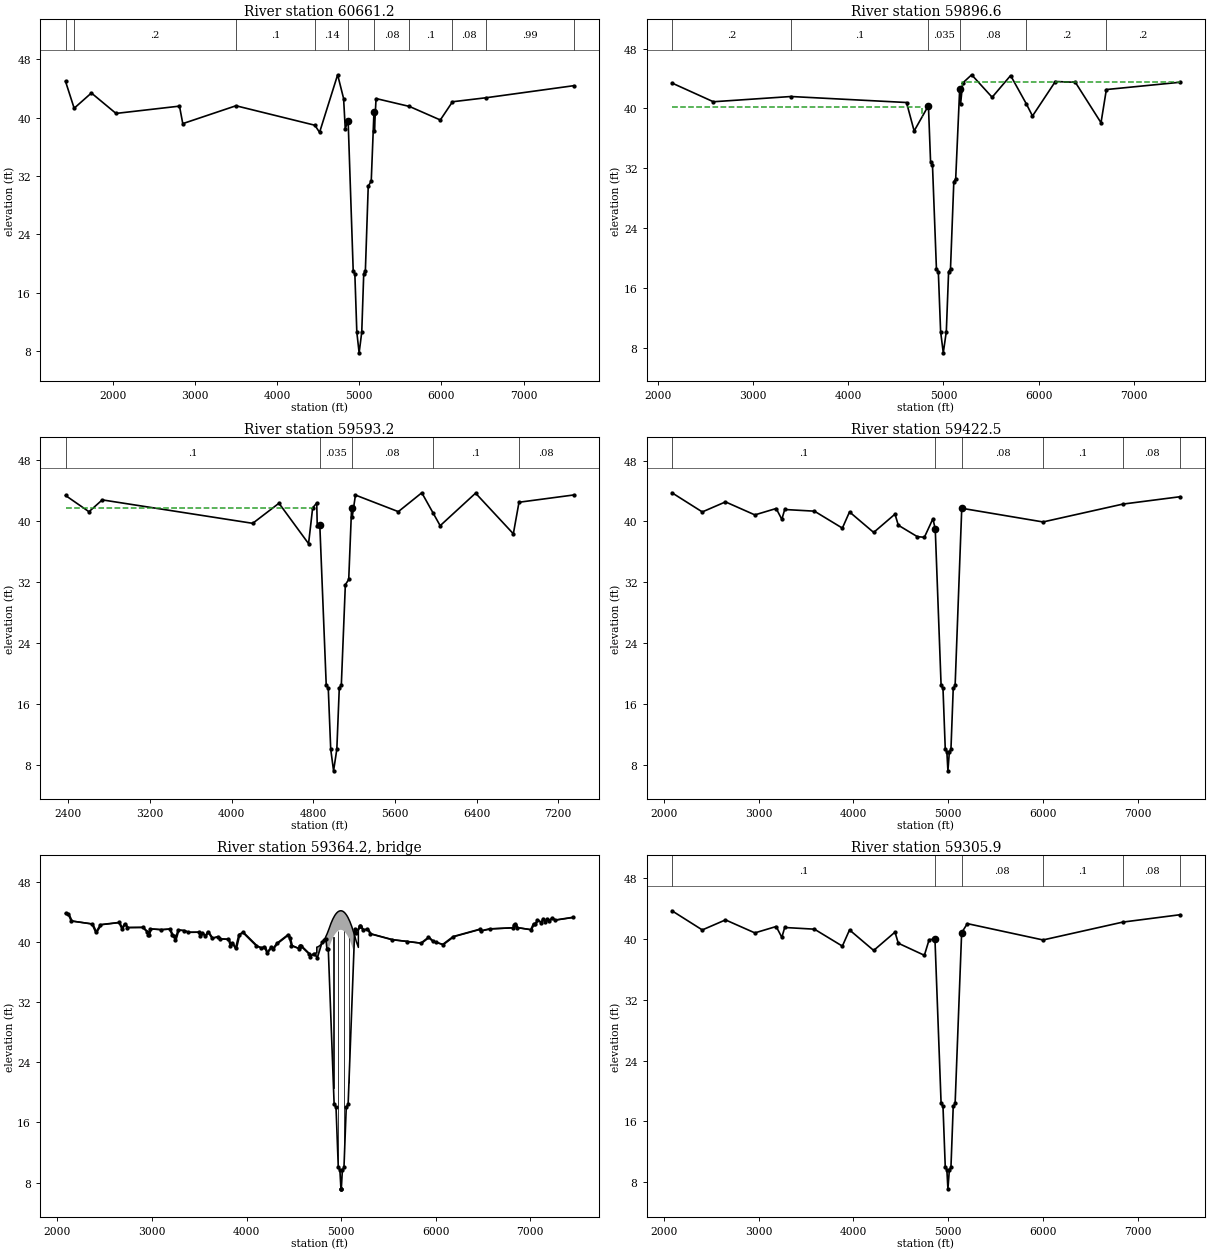
Type RM Length L Ch R = 1 ,60661.2 ,741.42,764.63,800.16
BEGIN DESCRIPTION:
Cross Section 61295.5
USACE Sims Bayou Rectification
Reach 6 Downstream of Cullen to SH-288
File No. HSC 409-16
END DESCRIPTION:
XS GIS Cut Line= 6
     3120182.059    13802263.758      3120411.11     13799598.99
       3120812.7     13799074.88      3121037.32     13798741.35
      3121445.72     13797516.16     3121389.431    13796362.377
#Sta/Elev= 30
    1424      45  1529.3   41.31    1739    43.4  2038.7    40.6  2811.5    41.6
  2851.5    39.2    3499   41.65    4459   38.98  4516.5      38  4736.5    45.9
    4809   42.64    4829   38.52 4864.21    39.6    4926      19    4946    18.6
    4970    10.6    4998   7.762    5030    10.6    5054    18.6    5074      19
  5108.8    30.6 5145.53   31.34  5178.6   40.79    5184   38.25    5204   42.64
  5609.7   41.56  5986.2    39.7  6134.5    42.2  6543.6   42.75    7608    44.4
#Mann= 10 ,-1 , 0
    1424     .99       0  1529.3      .2       0    3499      .1       0
    4459     .14       0 4864.21    .035       0  5178.6     .08       0
  5609.7      .1       0  6134.5     .08       0  6543.6     .99       0
    7608      .2       0
Bank Sta=4864.21,5178.6
XS Rating Curve= 0 ,0
Exp/Cntr=0.3,0.1

Type RM Length L Ch R = 1 ,59896.6 ,336.54,303.43,218.57
BEGIN DESCRIPTION:
Cross Section 60511.7
USACE Sims Bayou Rectification
Reach 6 Downstream of Cullen to SH-288
File No. HSC 409-16
END DESCRIPTION:
XS GIS Cut Line= 5
      3120400.88       13802125.      3120976.06     13799898.48
       3121527.4     13799333.53      3121622.69     13798874.08
      3121710.06     13797096.26
#Sta/Elev= 30
  2147.3    43.4  2582.3    40.9  3397.3    41.6  4611.9    40.8  4691.9      37
 4841.99   40.38  4864.4   32.91 4884.34   32.52    4926   18.63    4946   18.23
    4970   10.23    4998   7.392    5030   10.23    5054   18.23    5074   18.63
  5108.8   30.23  5128.5   30.62 5170.44   42.61    5180   40.59  5201.9    43.4
  5296.3    44.5  5511.3    41.5  5705.5    44.4  5869.4   40.65  5935.5      39
  6175.5    43.6  6385.5    43.5  6655.5    38.1  6711.6   42.53  7485.5    43.5
#Mann= 6 ,-1 , 0
  2147.3      .2       0  3397.3      .1       0 4841.99    .035       0
 5170.44     .08       0  5869.4      .2       0  6711.6      .2       0
#XS Ineff= 2 , 0
       0    4772   40.15  5198.5       0    43.5
Permanent Ineff=
       F       F
Bank Sta=4841.99,5170.44
XS Rating Curve= 0 ,0
Exp/Cntr=0.3,0.1

Type RM Length L Ch R = 1 ,59593.2 ,243.1,170.67,143.61
BEGIN DESCRIPTION:
Cross Section 60206.0 - Interpolated
USACE Sims Bayou Rectification
Reach 6 Downstream of Cullen to SH-288
File No. HSC 409-16
END DESCRIPTION:
XS GIS Cut Line= 6
     3120496.816    13801998.687      3120902.15     13800952.29
      3121551.93     13799775.23      3121685.08     13799562.19
      3121679.76     13798294.59     3121740.222    13797303.769
#Sta/Elev= 30
  2371.3   43.31  2601.3   41.18  2731.3   42.73  4205.7   39.66    4463   42.29
    4753      37    4793   41.67    4833   42.33    4838   39.34 4863.31   39.39
    4926   18.49    4946   18.09    4970   10.09    4998   7.252    5030   10.09
    5054   18.09    5074   18.49 5113.39   31.62 5146.49   32.31 5174.42   41.62
    5180   40.44  5212.5   43.36  5632.5   41.19  5862.5   43.66  5972.5   41.03
  6042.5   39.35  6389.5   43.61  6759.5   38.29    6815   42.42  7349.5   43.37
#Mann= 5 ,-1 , 0
  2371.3      .1       0 4863.31    .035       0 5174.42     .08       0
  5972.5      .1       0    6815     .08       0
#XS Ineff= 2 , 0
       0    4793   41.71    5213       0   43.35
Permanent Ineff=
       F       F
Bank Sta=4863.31,5174.42
XS Rating Curve= 0 ,0
Exp/Cntr=0.5,0.3

Type RM Length L Ch R = 1 ,59422.5 ,114.31,116.56,114.91
BEGIN DESCRIPTION:
Upstream Section of Bridge/Culvert/Weir
USACE Sims Bayou Rectification
Reach 6 Downstream of Cullen to SH-288
File No. HSC 409-16
END DESCRIPTION:
XS GIS Cut Line= 6
     3120490.422    13802191.083      3121140.02     13800747.82
      3121776.14     13800095.54      3121809.53     13799715.74
       3121843.3     13799078.53      3121800.34    13797229.346
#Sta/Elev= 30
  2084.8   43.77  2404.8   41.25  2649.8   42.57  2959.8   40.86  3184.8    41.7
  3244.8   40.27  3274.8   41.57  3588.6   41.35  3883.6   39.12  3959.2   41.25
  4214.2   38.55  4439.2   40.96  4474.2    39.5  4674.4      38  4749.4   37.91
  4839.4   40.35  4864.2   39.01    4926   18.41    4946   18.01    4970   10.01
  4986.9   9.672    4998   7.172  5013.1   9.672    5030   10.01    5054   18.01
    5074   18.41 5143.97   41.73  6002.1   39.93  6844.2   42.28  7448.2   43.25
#Mann= 6 ,-1 , 0
  2084.8      .1       0  4864.2    .035       0 5143.97     .08       0
  6002.1      .1       0  6844.2     .08       0  7448.2      .2       0
#XS Ineff= 2 , 0
       0    4860    38.2    5140       0   39.64
Permanent Ineff=
       F       F
Bank Sta=4864.2,5143.97
XS Rating Curve= 0 ,0
Exp/Cntr=0.5,0.3

Type RM Length L Ch R = 3 ,59364.2 ,,,
BEGIN DESCRIPTION:
SCOTT STREET
Structure ID: C00-30
END DESCRIPTION:
Bridge Culvert--1,0,-1,-1, 0
Deck Dist Width WeirC Skew NumUp NumDn MinLoCord MaxHiCord MaxSubmerge Is_Ogee
10,94,2.6,0, 138, 138, , , 0.95, 0, 1,1,,
  2094.8  2124.8  2154.8  2374.8  2414.8  2464.8  2659.8  2689.8  2719.8  2749.8
  2909.8  2959.8  2969.8  2974.8  2989.8  3104.8  3194.8  3224.8  3239.8  3254.8
  3284.8  3344.8  3393.6  3503.6  3518.6  3538.6  3573.6  3598.6  3643.6  3708.6
  3728.6  3818.6  3838.6  3858.6  3893.6  3928.6  3969.2  4114.2  4164.2  4199.2
  4224.2  4269.2  4289.2  4329.2  4449.2  4464.2  4484.2  4559.2  4579.2  4579.4
  4583.1  4674.4  4684.4  4719.44742.4154742.4154752.4154762.4154772.4154782.415
4792.4154802.4154812.4154822.4154832.4154842.4154852.4154862.4154872.4154882.415
4892.4154902.4154912.4154922.4154932.4154942.4154952.4154962.4154972.4154982.415
4990.5854990.5854992.4155002.4155012.4155022.4155032.4155042.4155052.4155053.965
5053.9655062.4155072.4155082.4155092.4155102.4155112.4155122.4155132.4155142.415
5152.4155162.4155172.4155182.4155182.415  5207.8  5212.8  5237.8  5287.8  5317.8
  5547.9    5709  5852.9  5932.9  5977.9  6012.1  6082.9  6194.8  6474.8  6489.8
  6579.8  6829.8  6834.8  6849.8  6854.2  6869.8  7014.8  7044.8  7059.8  7084.8
  7124.8  7144.8  7169.8  7189.8  7209.8  7239.8  7269.8  7458.2
   43.76   43.63   42.76   42.36   41.24   42.27   42.56   41.75   42.39   41.89
   41.91   41.28   40.85   40.91   41.71   41.61   41.69   40.83   40.81   40.26
   41.56   41.49   41.26   41.27   40.73   41.16   40.75   41.34   40.48   40.68
   40.39   40.32   39.43   39.78   39.11   40.95   41.24   39.44   39.17   39.33
   38.54   39.27    39.1   39.78   40.95    40.5   39.49    39.1   39.47   39.47
   39.44   38.34    38.2   38.44  38.544   39.29  39.328   39.39  39.478  39.591
  39.729  39.893  40.081  40.295  40.533  40.797  41.086  41.401   41.74  42.104
  42.443  42.751  43.028  43.274  43.488  43.672  43.824  43.946  44.036  44.095
  44.118  44.118  44.123   44.12  44.086  44.021  43.924  43.797  43.638  43.609
  43.609  43.448  43.228  42.976  42.693  42.379  42.034  41.657   41.25   40.81
  40.372  39.968  39.596  39.257  41.524   42.08   42.08   41.61   41.66   41.06
   40.28   40.04   39.81   40.59   40.06   39.92   39.63   40.69   41.66   41.46
   41.71   41.86   42.22   42.38   42.27   41.88    41.6   42.41   42.29   42.91
   42.53   43.08   42.68   43.03   42.82   43.15   42.88   43.24
                                                                                
                                                                                
                                                                                
                                                                                
                                                                                
                                                                                
                                                  38.557  38.872  39.212  39.576
  39.914  40.222  40.499  40.745  40.959  41.142  41.294  41.416  41.506  41.565
  41.588  41.588  41.593   41.59  41.556  41.491  41.394  41.267  41.108  41.079
  41.078  40.919  40.699  40.447  40.164   39.85  39.506  39.129  38.722  38.282
  37.844   37.44  37.068  36.729  41.512   42.07   42.07    41.6   41.65   41.05
   40.27   40.03   39.81   40.59   40.06   39.92   39.63   40.69   41.66   41.46
   41.71   41.86   42.22   42.38   42.27   41.88    41.6   42.41   42.29   42.91
   42.53   43.08   42.68   43.03   42.82   43.15   42.88   43.24
  2094.8  2124.8  2154.8  2374.8  2414.8  2464.8  2659.8  2689.8  2719.8  2749.8
  2909.8  2959.8  2969.8  2974.8  2989.8  3104.8  3194.8  3224.8  3239.8  3254.8
  3284.8  3344.8  3393.6  3503.6  3518.6  3538.6  3573.6  3598.6  3643.6  3708.6
  3728.6  3818.6  3838.6  3858.6  3893.6  3928.6  3969.2  4114.2  4164.2  4199.2
  4224.2  4269.2  4289.2  4329.2  4449.2  4464.2  4484.2  4559.2  4579.2  4579.4
  4583.1  4674.4  4684.4  4719.44742.4154742.4154752.4154762.4154772.4154782.415
4792.4154802.4154812.4154822.4154832.4154842.4154852.4154862.4154872.4154882.415
4892.4154902.4154912.4154922.4154932.4154942.4154952.4154962.4154972.4154982.415
4990.5854990.5854992.4155002.4155012.4155022.4155032.4155042.4155052.4155053.965
5053.9655062.4155072.4155082.4155092.4155102.4155112.4155122.4155132.4155142.415
5152.4155162.4155172.4155182.4155182.415  5207.8  5212.8  5237.8  5287.8  5317.8
  5547.9    5709  5852.9  5932.9  5977.9  6012.1  6082.9  6194.8  6474.8  6489.8
  6579.8  6829.8  6834.8  6849.8  6854.2  6869.8  7014.8  7044.8  7059.8  7084.8
  7124.8  7144.8  7169.8  7189.8  7209.8  7239.8  7269.8  7458.2
   43.76   43.63   42.76   42.36   41.24   42.27   42.56   41.75   42.39   41.89
   41.91   41.28   40.85   40.91   41.71   41.61   41.69   40.83   40.81   40.26
   41.56   41.49   41.26   41.27   40.73   41.16   40.75   41.34   40.48   40.68
   40.39   40.32   39.43   39.78   39.11   40.95   41.24   39.44   39.17   39.33
   38.54   39.27    39.1   39.78   40.95    40.5   39.49    39.1   39.47   39.47
   39.44   38.34    38.2   38.44  38.544   39.29  39.328   39.39  39.478  39.591
  39.729  39.893  40.081  40.295  40.533  40.797  41.086  41.401   41.74  42.104
  42.443  42.751  43.028  43.274  43.488  43.672  43.824  43.946  44.036  44.095
  44.118  44.118  44.123   44.12  44.086  44.021  43.924  43.797  43.638  43.609
  43.609  43.448  43.228  42.976  42.693  42.379  42.034  41.657   41.25   40.81
  40.372  39.968  39.596  39.257  41.524   42.08   42.08   41.61   41.66   41.06
   40.28   40.04   39.81   40.59   40.06   39.92   39.63   40.69   41.66   41.46
   41.71   41.86   42.22   42.38   42.27   41.88    41.6   42.41   42.29   42.91
   42.53   43.08   42.68   43.03   42.82   43.15   42.88   43.24
                                                                                
                                                                                
                                                                                
                                                                                
                                                                                
                                                                                
                                                  38.507  38.822  39.162  39.526
  39.864  40.172  40.449  40.695  40.909  41.092  41.244  41.366  41.456  41.515
  41.538   41.05   41.03  40.919  40.809  40.698  40.588  40.478  40.367   40.35
  41.028  40.869  40.649  40.397  40.114    39.8  39.456  39.079  38.672  38.232
  37.794   37.39  37.018  36.679  41.462   42.02   42.02   41.55    41.6      41
   40.22   39.98   39.76   40.54   40.01   39.87   39.58   40.64   41.61   41.41
   41.66   41.81   42.17   42.33   42.22   41.83   41.55   42.36   42.24   42.86
   42.48   43.03   42.63   42.98   42.77    43.1   42.83   43.19
Pier Skew, UpSta & Num, DnSta & Num=  ,4919.385, 2 ,4919.385, 2 , 0 , 0 , 0 ,,
    3.16    3.16
       0      44
    3.16    3.16
       0      44
Pier Skew, UpSta & Num, DnSta & Num=  ,4968.385, 2 ,4968.385, 2 , 0 , 0 , 0 ,,
    3.16    3.16
       0      44
    3.16    3.16
       0      44
Pier Skew, UpSta & Num, DnSta & Num=  ,5032.385, 2 ,5032.385, 2 , 0 , 0 , 0 ,,
    3.16    3.16
       0      44
    3.16    3.16
       0      44
Pier Skew, UpSta & Num, DnSta & Num=  ,5082.385, 2 ,5082.385, 2 , 0 , 0 , 0 ,,
    3.16    3.16
       0      44
    3.16    3.16
       0      44
BR Coef= 1 , 1 , 0 ,1.25, 0 ,,,0.8,0,1.2,0,
WSPro=,,,, 1 ,,,, 0 ,,,, 0 ,,,,-1 ,-1 ,-1 , 0 , 0 , 0 , 0 , 0
BR U #Sta/Elev= 106
  2084.8   43.77  2114.8   43.64  2144.8   42.77  2364.8   42.37  2404.8   41.25
  2454.8   42.28  2649.8   42.57  2679.8   41.76  2709.8    42.4  2739.8    41.9
  2899.8   41.92  2949.8   41.29  2959.8   40.86  2964.8   40.92  2979.8   41.72
  3094.8   41.62  3184.8    41.7  3214.8   40.84  3229.8   40.82  3244.8   40.27
  3274.8   41.57  3334.8    41.5  3383.6   41.27  3493.6   41.28  3508.6   40.74
  3528.6   41.17  3563.6   40.76  3588.6   41.35  3633.6   40.49  3698.6   40.69
  3718.6    40.4  3808.6   40.33  3828.6   39.44  3848.6   39.79  3883.6   39.12
  3918.6   40.96  3959.2   41.25  4104.2   39.45  4154.2   39.18  4189.2   39.34
  4214.2   38.55  4259.2   39.28  4279.2   39.11  4319.2   39.79  4439.2   40.96
  4454.2   40.51  4474.2    39.5  4549.2   39.11  4569.2   39.48  4569.4   39.48
  4573.1   39.44  4664.4   38.34  4674.4      38  4709.4   38.44  4749.4   37.91
  4799.4   39.96  4823.1   40.19  4839.4   40.35    4850   39.01  4864.2   39.01
    4926   18.41    4946   18.01    4970   10.01  4986.9   9.672    4998   7.172
    5000   7.172    5002   7.172  5013.1   9.672    5030   10.01    5054   18.01
    5074   18.41 5143.97   41.73  5156.7   41.18  5197.8   42.08  5202.8   42.08
  5227.8   41.61  5277.8   41.66  5307.8   41.06  5537.9   40.28    5699   40.04
  5842.9   39.82  5922.9    40.6  5967.9   40.07  6002.1   39.93  6072.9   39.64
  6184.8    40.7  6464.8   41.67  6479.8   41.47  6569.8   41.72  6819.8   41.87
  6824.8   42.23  6839.8   42.39  6844.2   42.28  6859.8   41.89  7004.8   41.61
  7034.8   42.42  7049.8    42.3  7074.8   42.92  7114.8   42.54  7134.8   43.09
  7159.8   42.69  7179.8   43.04  7199.8   42.83  7229.8   43.16  7259.8   42.89
  7448.2   43.25
BR U #Mann= 6
  2084.8      .1  4864.2    .015 5143.97     .08  6002.1      .1  6844.2     .08
  7448.2      .2
BR D #Sta/Elev= 106
  2084.8   43.71  2114.8   43.58  2144.8   42.71  2364.8   42.31  2404.8   41.19
  2454.8   42.22  2649.8   42.51  2679.8    41.7  2709.8   42.34  2739.8   41.84
  2899.8   41.86  2949.8   41.23  2959.8    40.8  2964.8   40.86  2979.8   41.66
  3094.8   41.56  3184.8   41.64  3214.8   40.78  3229.8   40.76  3244.8   40.21
  3274.8   41.51  3334.8   41.44  3383.6   41.21  3493.6   41.22  3508.6   40.68
  3528.6   41.11  3563.6    40.7  3588.6   41.29  3633.6   40.43  3698.6   40.63
  3718.6   40.34  3808.6   40.27  3828.6   39.38  3848.6   39.73  3883.6   39.06
  3918.6    40.9  3959.2   41.19  4104.2   39.39  4154.2   39.12  4189.2   39.28
  4214.2   38.49  4259.2   39.22  4279.2   39.05  4319.2   39.73  4439.2    40.9
  4454.2   40.45  4474.2   39.44  4549.2   39.05  4569.2   39.42  4569.4   39.42
  4573.1   39.38  4664.4   38.28  4674.4   37.94  4709.4   38.38  4749.4   37.85
  4799.4    39.9  4823.1   40.13  4839.4   40.29 4861.06   40.01    4926   18.36
    4946   17.96    4970    9.96  4986.9   9.622    4998   7.122    5000   7.122
    5002   7.122  5013.1   9.622    5030    9.96    5054   17.96    5074   18.36
 5139.03   40.04  5142.8   40.82  5156.7   41.12  5197.8   42.02  5202.8   42.02
  5227.8   41.55  5277.8    41.6  5307.8      41  5537.9   40.22    5699   39.98
  5842.9   39.76  5922.9   40.54  5967.9   40.01  6002.1   39.87  6072.9   39.58
  6184.8   40.64  6464.8   41.61  6479.8   41.41  6569.8   41.66  6819.8   41.81
  6824.8   42.17  6839.8   42.33  6844.2   42.22  6859.8   41.83  7004.8   41.55
  7034.8   42.36  7049.8   42.24  7074.8   42.86  7114.8   42.48  7134.8   43.03
  7159.8   42.63  7179.8   42.98  7199.8   42.77  7229.8    43.1  7259.8   42.83
  7448.2   43.19
BR D #Mann= 6
  2084.8      .1 4861.06    .015  5142.8     .08  6002.1      .1  6844.2     .08
  7448.2      .2
BC Design=,, 0 ,, 0 ,,,,,,
BC HTab HWMax=43.77
BC Use User HTab Curves=0
BC User HTab FreeFlow(D)= 0

Type RM Length L Ch R = 1 ,59305.9 ,244.69,487.86,750.33
BEGIN DESCRIPTION:
Downstream Section of Bridge/Culvert/Weir
USACE Sims Bayou Rectification
Reach 6 Downstream of Cullen to SH-288
File No. HSC 409-16
END DESCRIPTION:
XS GIS Cut Line= 6
     3120598.869     13802221.65       3121251.5     13800771.66
      3121887.62     13800119.38      3121921.01     13799739.58
      3121954.78     13799102.37     3121911.992    13797260.572
#Sta/Elev= 30
  2084.8   43.71  2404.8   41.19  2649.8   42.51  2959.8    40.8  3184.8   41.64
  3244.8   40.21  3274.8   41.51  3588.6   41.29  3883.6   39.06  3959.2   41.19
  4214.2   38.49  4439.2    40.9  4474.2   39.44  4749.4   37.85  4799.4    39.9
 4861.06   40.01    4926   18.36    4946   17.96    4970    9.96  4986.9   9.622
    4998   7.122  5013.1   9.622    5030    9.96    5054   17.96    5074   18.36
  5142.8   40.82  5202.8   42.02  6002.1   39.87  6844.2   42.22  7448.2   43.19
#Mann= 6 ,-1 , 0
  2084.8      .1       0 4861.06    .035       0  5142.8     .08       0
  6002.1      .1       0  6844.2     .08       0  7448.2      .2       0
#XS Ineff= 2 , 0
       0    4861    38.2    5140       0   39.64
Permanent Ineff=
       F       F
Bank Sta=4861.06,5142.8
XS Rating Curve= 0 ,0
Exp/Cntr=0.5,0.3