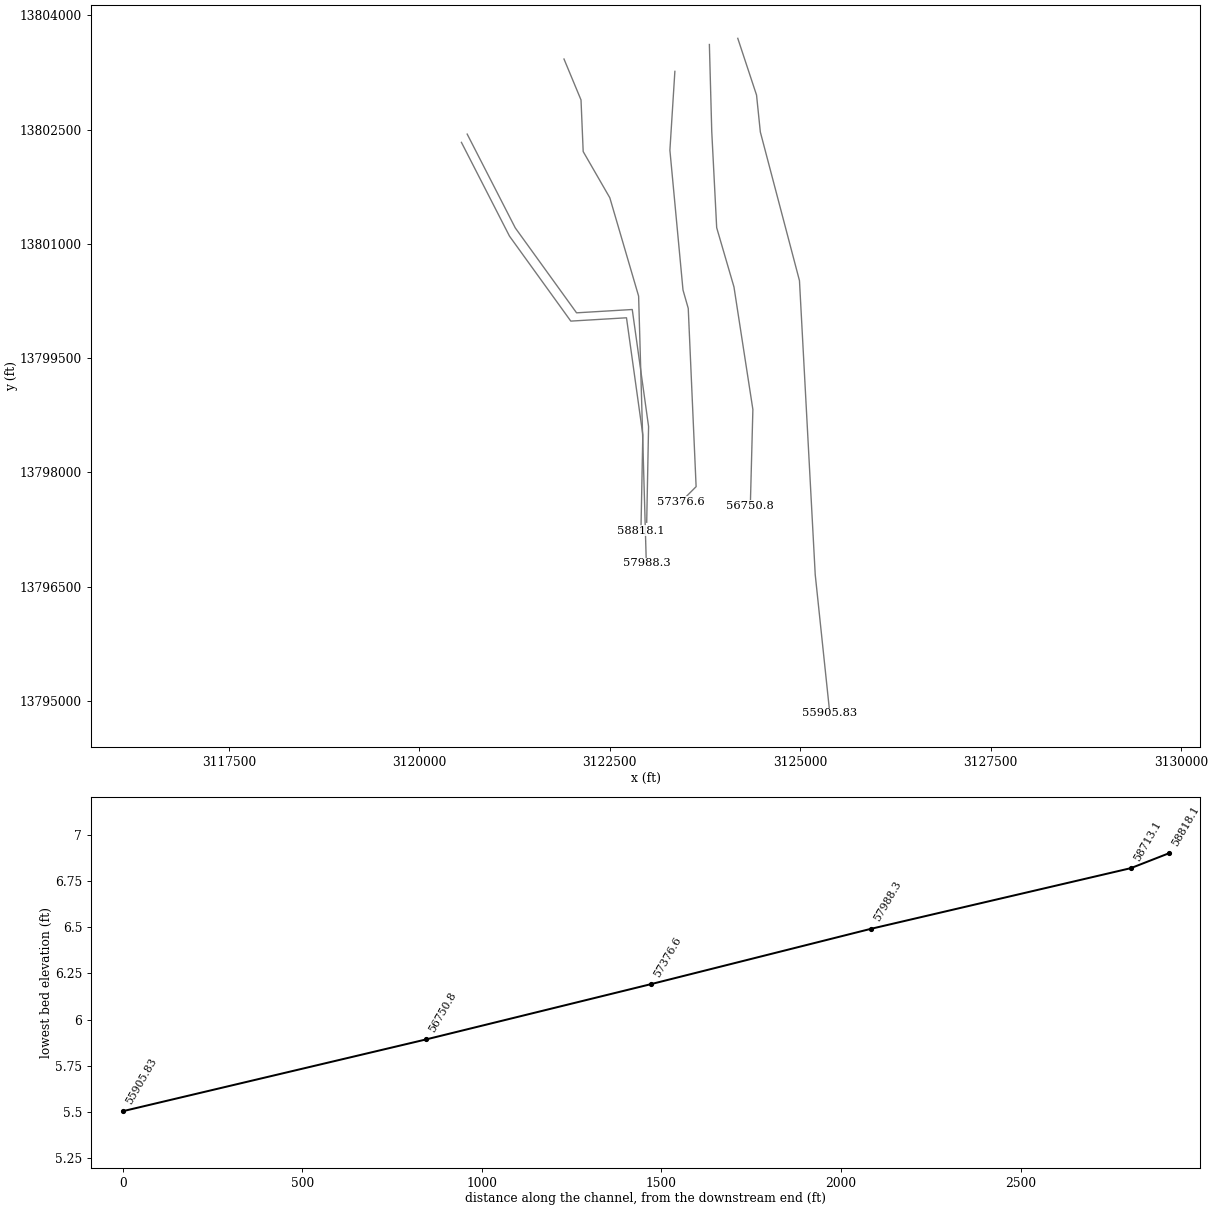
HEC-RAS study C100-00-00.prj: C100-00-00

--- C100-00-00.g01 (geometry) --- (continued)

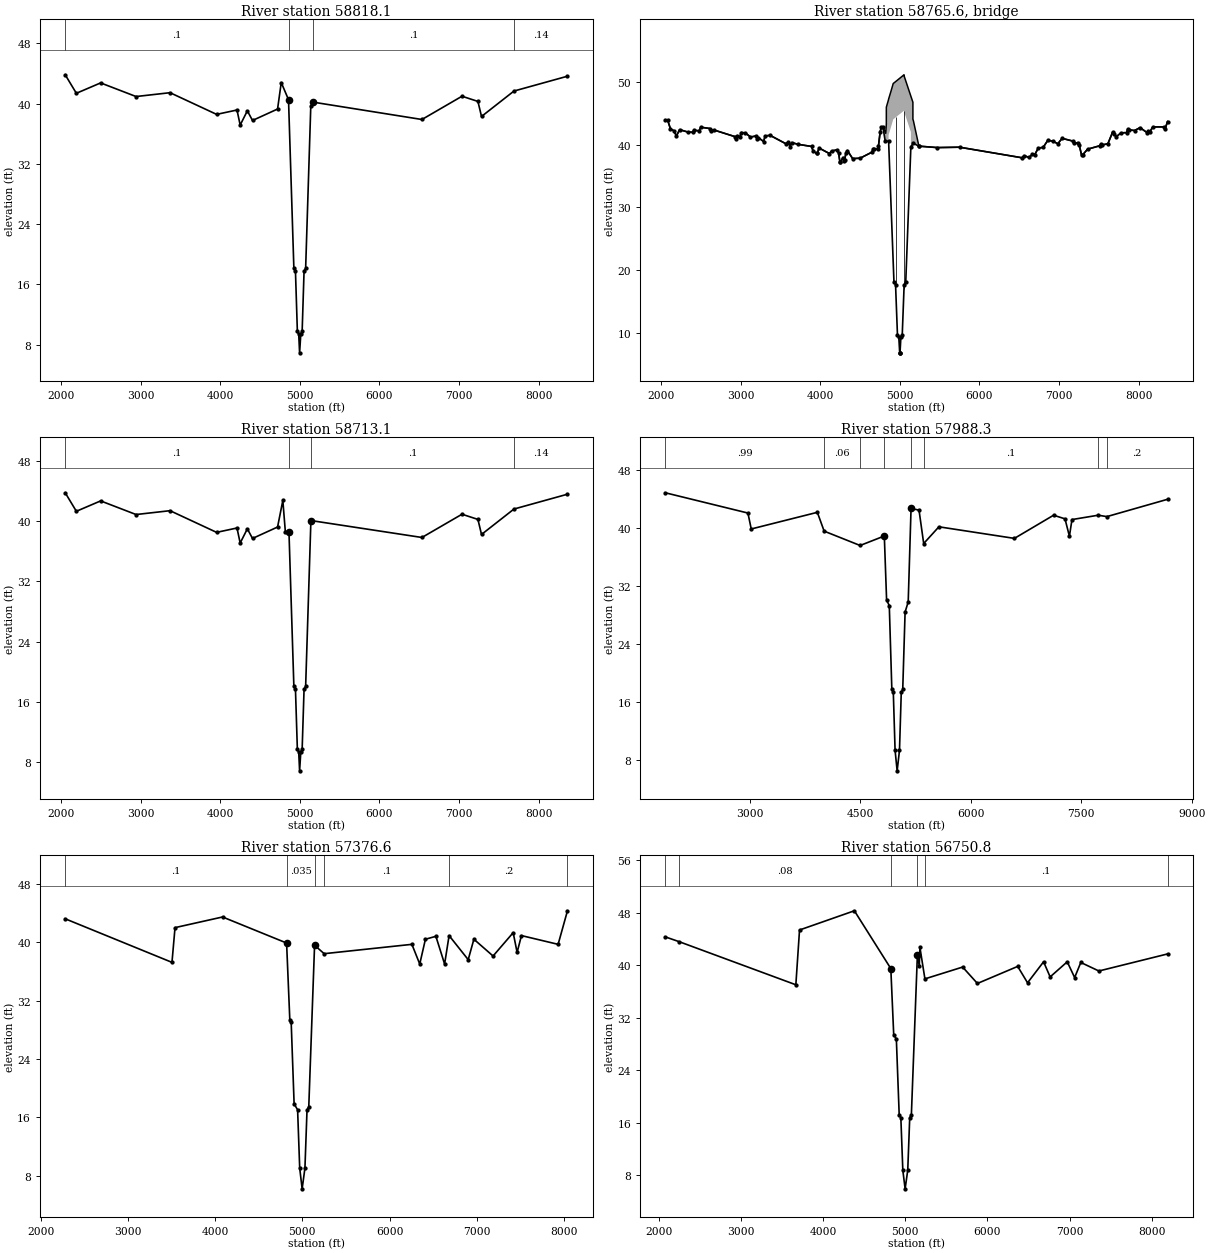
Type RM Length L Ch R = 1 ,58818.1 ,104.53,104.94,112.53
BEGIN DESCRIPTION:
Upstream Section of Bridge/Culvert/Weir
USACE Sims Bayou Rectification
Reach 6 Downstream of Cullen to SH-288
File No. HSC 409-16
END DESCRIPTION:
XS GIS Cut Line= 6
  3120553.59995213802331.4148641 3121184.749936813801100.1348463
 3121989.4100729 13799985.064898 3122720.530001713800028.6550339
 3122934.8300981 13798492.874969 3122910.350160113797236.2150807
#Sta/Elev= 30
  2053.1   43.84  2193.1   41.38  2498.1   42.76  2943.1   40.95  3370.2   41.46
  3955.2   38.58  4211.4   39.16  4251.4   37.16  4341.4   39.05  4406.4   37.77
  4721.2   39.29  4767.4   42.81 4858.83   40.53    4926   18.14    4946   17.74
    4970    9.74  4986.9   9.402    4998   6.902  5013.1   9.402    5030    9.74
    5054   17.74    5074   18.14 5138.55   39.66 5170.19    40.2    6535    37.9
  7038.6   40.99  7238.6    40.3  7283.6    38.3  7691.6   41.68  8363.6   43.65
#Mann= 4 ,-1 , 0
  2053.1      .1       0 4858.83    .035       0 5170.19      .1       0
  7691.6     .14       0
#XS Ineff= 2 , 0
       0 4858.83   37.16 5138.55       0   39.52
Permanent Ineff=
       F       F
Bank Sta=4858.83,5170.19
XS Rating Curve= 0 ,0
Exp/Cntr=0.5,0.3

Type RM Length L Ch R = 3 ,58765.6 ,,,
BEGIN DESCRIPTION:
AIRPORT ROAD
Structure ID: C00-29
END DESCRIPTION:
Bridge Culvert--1,0,-1,-1, 0
Deck Dist Width WeirC Skew NumUp NumDn MinLoCord MaxHiCord MaxSubmerge Is_Ogee
10,92,2.6,0, 142, 142, , , 0.95, 0, 1,1,,
  2053.1  2083.1  2118.1  2158.1  2193.1  2233.1  2333.1  2398.1  2413.1  2478.1
  2498.1  2613.1  2628.1  2663.1  2928.1  2943.1  2958.1  2988.1  3008.1  3058.1
  3123.1  3188.1  3208.1  3223.1  3288.1  3308.1  3370.2  3565.2  3600.2  3620.2
  3640.2  3725.2  3890.2  3910.2  3955.2  3965.2  3985.2  4115.2  4141.4  4211.4
  4231.4  4246.4  4251.4  4286.4  4301.4  4306.4  4321.4  4341.4  4406.4  4500.6
  4650.6  4665.6  4676.2  4721.2  4731.2  4752.4  4767.4  4787.4  4822.4  4828.9
 4829.01  4829.1 4830.09  4830.2 4830.31  4833.6  4837.4  4847.4 4856.18 4856.27
 4858.83  4873.1 4889.08  4916.6  4924.8 4945.48 4947.26 4949.24 4969.92  4999.9
 5030.08 5050.76  5052.5 5052.64  5052.9 5054.52  5075.2 5110.92  5126.9 5138.55
 5145.61  5145.7  5149.8  5162.4 5163.89    5164 5164.11 5170.19  5170.3  5170.4
  5238.8  5243.6  5468.6    5750    6535    6560    6625    6665    6695    6740
    6800    6860    6925    6985  7038.6  7173.6  7193.6  7238.6  7253.6  7283.6
  7298.6  7358.6  7508.6  7528.6  7538.6  7613.6  7673.6  7691.6  7718.6  7778.6
  7848.6  7863.6  7883.6  7948.6  8018.6  8108.6  8123.6  8138.6  8178.6  8318.6
  8333.6  8363.6
   43.84   43.85   42.48   42.21   41.38   42.37      42   41.95   42.26   42.19
   42.76   42.55    42.2   42.32   41.26   40.95   41.42   41.13   41.91   41.86
    41.2   41.35   40.92    41.1   40.48   41.38   41.46   40.15   40.38   39.67
   40.31   40.03    39.7   38.97   38.58   38.73   39.45   38.57   38.97   39.16
   38.62   37.26   37.16   37.93   37.38   37.49   38.61   39.05   37.77   37.83
    38.8   39.36   39.27   39.29   39.76      42   42.81   42.82   41.79   43.22
   43.22   43.23   43.25   45.95   45.95   46.09   46.26   46.69   47.07   47.08
   47.23   47.81    48.5    49.7   49.78      50   50.01   50.03   50.25   50.55
   50.86   51.07   51.09   51.03   50.93   50.87   50.09   48.73   48.13   47.74
   47.42   47.42   47.26   46.79   46.73   46.73   44.03   43.79   43.79   43.78
   39.78   39.75   39.52   39.58    37.9   38.23   37.96   38.45   38.39   39.46
   39.54   40.69   40.52   40.13   40.99   40.55   40.21    40.3   39.94    38.3
   38.39   39.26    39.8   40.06   39.94   40.12   41.98   41.68   41.24   41.86
    41.9    42.5   42.33   42.23   42.69   41.87   42.08   41.96   42.81   42.81
   42.53   43.65
                                                                                
                                                                                
                                                                                
                                                                                
                                                                                
                                                                                
                                                                                
   41.53   42.11    42.8      44   44.08    44.3   44.31   44.33   44.55   44.85
   45.16   45.37   45.39   45.33   45.23   45.17   44.39   43.03   42.43      42
                                                                                
                                                                                
                                                                                
                                                                                
                                                                                
                
  2053.1  2083.1  2118.1  2158.1  2193.1  2233.1  2333.1  2398.1  2413.1  2478.1
  2498.1  2613.1  2628.1  2663.1  2928.1  2943.1  2958.1  2988.1  3008.1  3058.1
  3123.1  3188.1  3208.1  3223.1  3288.1  3308.1  3370.2  3565.2  3600.2  3620.2
  3640.2  3725.2  3890.2  3910.2  3955.2  3965.2  3985.2  4115.2  4141.4  4211.4
  4231.4  4246.4  4251.4  4286.4  4301.4  4306.4  4321.4  4341.4  4406.4  4500.6
  4650.6  4665.6  4676.2  4721.2  4731.2  4752.4  4767.4  4787.4  4822.4  4828.9
 4829.01  4829.1 4830.09  4830.2 4830.31  4833.6  4837.4  4847.4 4856.18 4856.27
 4864.38  4873.1 4889.08  4916.6  4924.8 4945.48 4947.26 4949.24 4969.92  4999.9
 5030.08 5050.76  5052.5 5052.64  5052.9 5054.52  5075.2 5110.92  5126.9 5140.07
 5145.61  5145.7  5149.8  5162.4 5163.89    5164 5164.11 5170.19  5170.3  5170.4
  5238.8  5243.6  5468.6    5750    6535    6560    6625    6665    6695    6740
    6800    6860    6925    6985  7038.6  7173.6  7193.6  7238.6  7253.6  7283.6
  7298.6  7358.6  7508.6  7528.6  7538.6  7613.6  7673.6  7691.6  7718.6  7778.6
  7848.6  7863.6  7883.6  7948.6  8018.6  8108.6  8123.6  8138.6  8178.6  8318.6
  8333.6  8363.6
   43.84   43.85   42.48   42.21   41.38   42.37      42   41.95   42.26   42.19
   42.76   42.55    42.2   42.32   41.26   40.95   41.42   41.13   41.91   41.86
    41.2   41.35   40.92    41.1   40.48   41.38   41.46   40.15   40.38   39.67
   40.31   40.03    39.7   38.97   38.58   38.73   39.45   38.57   38.97   39.16
   38.62   37.26   37.16   37.93   37.38   37.49   38.61   39.05   37.77   37.83
    38.8   39.36   39.27   39.29   39.76      42   42.81   42.82   41.79   43.22
   43.22   43.23   43.25   45.95   45.95   46.09   46.26   46.69   47.07   47.08
   47.46   47.81    48.5    49.7   49.78      50   50.01   50.03   50.25   50.55
   50.86   51.07   51.09   51.03   50.93   50.87   50.09   48.73   48.13   47.68
   47.42   47.42   47.26   46.79   46.73   46.73   44.03   43.79   43.79   43.78
   39.78   39.75   39.52   39.58    37.9   38.23   37.96   38.45   38.39   39.46
   39.54   40.69   40.52   40.13   40.99   40.55   40.21    40.3   39.94    38.3
   38.39   39.26    39.8   40.06   39.94   40.12   41.98   41.68   41.24   41.86
    41.9    42.5   42.33   42.23   42.69   41.87   42.08   41.96   42.81   42.81
   42.53   43.65
                                                                                
                                                                                
                                                                                
                                                                                
                                                                                
                                                                                
                                                                                
   41.74   42.05   42.74   43.94   44.02   44.24   44.25   44.27   44.49   44.79
    45.1   45.31   45.33   45.27   45.17   45.11   44.33   42.97   42.37   41.94
                                                                                
                                                                                
                                                                                
                                                                                
                                                                                
                
Pier Skew, UpSta & Num, DnSta & Num=  ,4946.5, 2 ,4946.5, 2 , 0 , 0 , 0 ,,
       2       2
   15.83   45.31
       2       2
   15.77   45.25
Pier Skew, UpSta & Num, DnSta & Num=  ,5051.7, 2 ,5051.7, 2 , 0 , 0 , 0 ,,
       2       2
   15.28   46.37
       2       2
   15.22   46.31
BR Coef= 1 , 1 , 0 ,1.25, 0 ,,,0.8,0,2,0,
WSPro=,,,, 1 ,,,, 0 ,,,, 0 ,,,,-1 ,-1 ,-1 , 0 , 0 , 0 , 0 , 0
BR U #Sta/Elev= 115
  2053.1   43.84  2083.1   43.85  2118.1   42.48  2158.1   42.21  2193.1   41.38
  2233.1   42.37  2333.1      42  2398.1   41.95  2413.1   42.26  2478.1   42.19
  2498.1   42.76  2613.1   42.55  2628.1    42.2  2663.1   42.32  2928.1   41.26
  2943.1   40.95  2958.1   41.42  2988.1   41.13  3008.1   41.91  3058.1   41.86
  3123.1    41.2  3188.1   41.35  3208.1   40.92  3223.1    41.1  3288.1   40.48
  3308.1   41.38  3370.2   41.46  3565.2   40.15  3600.2   40.38  3620.2   39.67
  3640.2   40.31  3725.2   40.03  3890.2    39.7  3910.2   38.97  3955.2   38.58
  3965.2   38.73  3985.2   39.45  4115.2   38.57  4141.4   38.97  4211.4   39.16
  4231.4   38.62  4246.4   37.26  4251.4   37.16  4286.4   37.93  4301.4   37.38
  4306.4   37.49  4321.4   38.61  4341.4   39.05  4406.4   37.77  4500.6   37.83
  4650.6    38.8  4665.6   39.36  4676.2   39.27  4721.2   39.29  4731.2   39.76
  4752.4      42  4767.4   42.81  4787.4   42.82 4816.14   40.53 4858.83   40.53
    4926   18.14    4946   17.74    4970    9.74  4986.9     9.4    4998     6.9
    5000     6.9    5002     6.9  5013.1     9.4    5030    9.74    5054   17.74
    5074   18.14 5138.55   39.66 5170.19    40.2  5238.8   39.74  5243.6   39.74
  5468.6   39.52    5750   39.58    6535    37.9    6560   38.23    6625   37.96
    6665   38.45    6695   38.39    6740   39.46    6800   39.54    6860   40.69
    6925   40.52    6985   40.13  7038.6   40.99  7173.6   40.55  7193.6   40.21
  7238.6    40.3  7253.6   39.94  7283.6    38.3  7298.6   38.39  7358.6   39.26
  7508.6    39.8  7528.6   40.06  7538.6   39.94  7613.6   40.12  7673.6   41.98
  7691.6   41.68  7718.6   41.24  7778.6   41.86  7848.6    41.9  7863.6    42.5
  7883.6   42.33  7948.6   42.23  8018.6   42.69  8108.6   41.87  8123.6   42.08
  8138.6   41.96  8178.6   42.81  8318.6   42.81  8333.6   42.53  8363.6   43.65
BR U #Mann= 4
  2053.1      .1 4858.83    .015 5170.19      .1  7691.6     .14
BR D #Sta/Elev= 115
  2053.1   43.77  2083.1   43.78  2118.1   42.41  2158.1   42.14  2193.1   41.31
  2233.1    42.3  2333.1   41.93  2398.1   41.88  2413.1   42.19  2478.1   42.12
  2498.1   42.69  2613.1   42.48  2628.1   42.13  2663.1   42.25  2928.1   41.19
  2943.1   40.88  2958.1   41.35  2988.1   41.06  3008.1   41.84  3058.1   41.79
  3123.1   41.13  3188.1   41.28  3208.1   40.85  3223.1   41.03  3288.1   40.41
  3308.1   41.31  3370.2   41.39  3565.2   40.08  3600.2   40.31  3620.2    39.6
  3640.2   40.24  3725.2   39.96  3890.2   39.63  3910.2    38.9  3955.2   38.51
  3965.2   38.66  3985.2   39.38  4115.2    38.5  4141.4    38.9  4211.4   39.09
  4231.4   38.55  4246.4   37.19  4251.4   37.09  4286.4   37.86  4301.4   37.31
  4306.4   37.42  4321.4   38.54  4341.4   38.98  4406.4    37.7  4500.6   37.76
  4650.6   38.73  4665.6   39.29  4676.2    39.2  4721.2   39.22  4731.2   39.69
  4752.4   41.93  4767.4   42.74  4787.4   42.75 4818.87    38.6 4864.38    38.6
    4926   18.06    4946   17.66    4970    9.66  4986.9    9.32    4998    6.82
    5000    6.82    5002    6.82  5013.1    9.32    5030    9.66    5054   17.66
    5074   18.06 5140.07   40.08  5203.2   40.32  5238.8   39.67  5243.6   39.67
  5468.6   39.45    5750   39.51    6535   37.83    6560   38.16    6625   37.89
    6665   38.38    6695   38.32    6740   39.39    6800   39.47    6860   40.62
    6925   40.45    6985   40.06  7038.6   40.92  7173.6   40.48  7193.6   40.14
  7238.6   40.23  7253.6   39.87  7283.6   38.23  7298.6   38.32  7358.6   39.19
  7508.6   39.73  7528.6   39.99  7538.6   39.87  7613.6   40.05  7673.6   41.91
  7691.6   41.61  7718.6   41.17  7778.6   41.79  7848.6   41.83  7863.6   42.43
  7883.6   42.26  7948.6   42.16  8018.6   42.62  8108.6    41.8  8123.6   42.01
  8138.6   41.89  8178.6   42.74  8318.6   42.74  8333.6   42.46  8363.6   43.58
BR D #Mann= 4
  2053.1      .1 4864.38    .015 5140.07      .1  7691.6     .14
BC Design=,, 0 ,, 0 ,,,,,,
BC HTab HWMax=43.85
BC Use User HTab Curves=0
BC User HTab FreeFlow(D)= 0

Type RM Length L Ch R = 1 ,58713.1 ,956.17,724.82,453.66
BEGIN DESCRIPTION:
Downstream Section of Bridge/Culvert/Weir
USACE Sims Bayou Rectification
Reach 6 Downstream of Cullen to SH-288
File No. HSC 409-16
END DESCRIPTION:
XS GIS Cut Line= 6
  3120629.19002413802440.0967333 3121260.349851213801208.8167156
 3122065.009987313800093.7464391 3122796.129916113800137.3365751
 3123010.430012513798601.5565102  3122985.93990413797344.9064644
#Sta/Elev= 30
  2053.1   43.77  2193.1   41.31  2498.1   42.69  2943.1   40.88  3370.2   41.39
  3955.2   38.51  4211.4   39.09  4251.4   37.09  4341.4   38.98  4406.4    37.7
  4721.2   39.22  4787.4   42.75 4818.87    38.6 4864.38    38.6    4926   18.06
    4946   17.66    4970    9.66  4986.9   9.322    4998   6.822  5013.1   9.322
    5030    9.66    5054   17.66    5074   18.06 5140.07   40.08    6535   37.83
  7038.6   40.92  7238.6   40.23  7283.6   38.23  7691.6   41.61  8363.6   43.58
#Mann= 4 ,-1 , 0
  2053.1      .1       0 4864.38    .035       0 5140.07      .1       0
  7691.6     .14       0
#XS Ineff= 2 , 0
       0 4864.38   36.69 5140.07       0   38.95
Permanent Ineff=
       F       F
Bank Sta=4864.38,5140.07
XS Rating Curve= 0 ,0
Exp/Cntr=0.5,0.3

Type RM Length L Ch R = 1 ,57988.3 ,627.87,611.76,593.18
BEGIN DESCRIPTION:
Cross Section 58541.3
USACE Sims Bayou Rectification
Reach 6 Downstream of Cullen to SH-288
File No. HSC 409-16
END DESCRIPTION:
XS GIS Cut Line= 6
     3121900.153    13803425.606      3122123.53      13802888.3
      3122152.06      13802210.6      3122501.62     13801604.24
       3122879.7     13800313.04     3122980.775    13796804.735
#Sta/Elev= 30
  1847.9    44.9  2970.5    42.1  3015.5    39.9  3913.7    42.2  4006.1    39.6
  4494.8   37.62  4823.8   38.93 4854.85   30.06  4891.2   29.33    4926   17.73
    4946   17.33    4970    9.33    4998   6.492    5030    9.33    5054   17.33
    5074   17.73 5106.11   28.43 5148.31   29.82 5187.09   42.74  5295.4    42.5
  5358.8   37.89  5565.4    40.2  6591.4    38.6  7123.8    41.8  7278.8    41.3
  7338.8    38.9  7373.8    41.2  7728.7    41.8  7848.4   41.61  8672.4      44
#Mann= 8 ,-1 , 0
  1847.9     .99       0  4006.1     .06       0  4494.8     .14       0
  4823.8    .035       0 5187.09     .14       0  5358.8      .1       0
  7728.7     .99       0  7848.4      .2       0
Bank Sta=4823.8,5187.09
XS Rating Curve= 0 ,0
Exp/Cntr=0.3,0.1

Type RM Length L Ch R = 1 ,57376.6 ,594.65,625.77,650.1
BEGIN DESCRIPTION:
Cross Section 57908.8
USACE Sims Bayou Rectification
Reach 6 Downstream of Cullen to SH-288
File No. HSC 409-16
END DESCRIPTION:
XS GIS Cut Line= 6
     3123355.703    13803263.666      3123290.32     13802228.55
      3123462.41     13800393.02      3123531.24      13800152.1
      3123634.49      13797811.8       3123435.1     13797612.41
#Sta/Elev= 30
  2282.3    43.2    3506   37.23  3540.9   41.99  4085.8   43.45 4819.85   39.88
 4856.72   29.35  4872.4   29.03    4906   17.83    4946   17.03    4970    9.03
    4998   6.192    5030    9.03    5054   17.03    5074   17.43 5140.42   39.57
  5250.6   38.42    6256    39.7    6346      37    6411    40.4    6531    40.8
    6631      37  6682.3    40.9  6901.5    37.6  6966.5    40.4  7186.5    38.1
    7417    41.3    7462    38.6    7512    40.9  7932.1    39.7  8039.2    44.3
#Mann= 6 ,-1 , 0
  2282.3      .1       0 4819.85    .035       0 5140.42     .14       0
  5250.6      .1       0  6682.3      .2       0  8039.2      .2       0
#XS Ineff= 2 , 0
       0 4819.85      39               0
Permanent Ineff=
       F       F
Bank Sta=4819.85,5140.42
XS Rating Curve= 0 ,0
Exp/Cntr=0.3,0.1

Type RM Length L Ch R = 1 ,56750.8 ,876.05,844.96,837.12
BEGIN DESCRIPTION:
Cross Section 57291.6-Interpolated
USACE Sims Bayou Rectification
Reach 6 Downstream of Cullen to SH-288
File No. HSC 409-16
END DESCRIPTION:
XS GIS Cut Line= 6
     3123808.631    13803616.212      3123839.76      13802474.6
      3123904.56     13801211.15      3124131.33     13800433.64
       3124379.7     13798824.64     3124346.072    13797558.131
#Sta/Elev= 30
  2079.6    44.3  2245.8   43.58  3668.2      37    3713   45.35  4380.4   48.28
  4823.9   39.47 4859.21   29.38  4891.2   28.74    4926   17.14    4946   16.74
    4970    8.73    4998   5.892    5030    8.74    5054   16.74    5074   17.14
 5147.37   41.59    5170   39.88    5178    42.7  5238.9    37.9  5697.9    39.7
  5877.9    37.2  6367.9    39.8  6487.9    37.3  6682.9    40.5  6762.9    38.2
    6971    40.5    7061    38.1    7136    40.4    7356    39.1  8191.7    41.7
#Mann= 6 ,-1 , 0
  2079.6      .1       0  2245.8     .08       0  4823.9    .035       0
 5147.37     .14       0  5238.9      .1       0  8191.7      .2       0
#XS Ineff= 2 , 0
       0  4823.9      39               0
Permanent Ineff=
       F       F
Bank Sta=4823.9,5147.37
XS Rating Curve= 0 ,0
Exp/Cntr=0.3,0.1

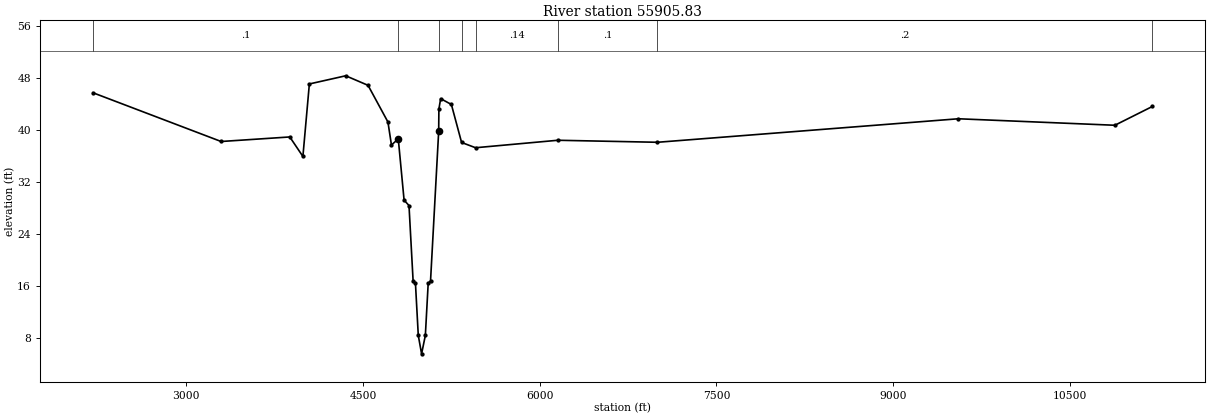
Type RM Length L Ch R = 1 ,55905.83,545.95,557.35,532.99
BEGIN DESCRIPTION:
Cross Section 56361.1
USACE Sims Bayou Rectification
Reach 6 Downstream of Cullen to SH-288
File No. HSC 409-16
END DESCRIPTION:
XS GIS Cut Line= 6
     3124181.418    13803697.136      3124427.71     13802952.51
      3124477.65     13802467.42      3124991.28     13800516.35
      3125198.15     13796657.02     3125389.467    13794835.532
#Sta/Elev= 30
  2209.8    45.7  3296.6    38.2  3879.3    38.9  3990.7    35.9  4045.5   47.06
  4354.2   48.32  4543.5   46.85  4712.5    41.2  4742.2   37.66  4800.2    38.6
 4849.48   29.17  4891.2   28.34    4926   16.74    4946   16.34    4970    8.34
    4998   5.502    5030    8.34    5054   16.34    5074   16.74 5143.11   39.77
  5144.9    43.2  5159.9    44.8  5250.9    43.9  5337.5   38.05  5456.1   37.24
  6154.3   38.39  6999.8   38.08  9553.8    41.7 10882.1    40.7 11201.1    43.6
#Mann= 8 ,-1 , 0
  2209.8      .1       0  4800.2    .035       0 5143.11     .14       0
  5337.5      .1       0  5456.1     .14       0  6154.3      .1       0
  6999.8      .2       0 11201.1      .2       0
#XS Ineff= 2 , 0
       0  4712.5      39               0
Permanent Ineff=
       F       F
Bank Sta=4800.2,5143.11
XS Rating Curve= 0 ,0
Exp/Cntr=0.3,0.1