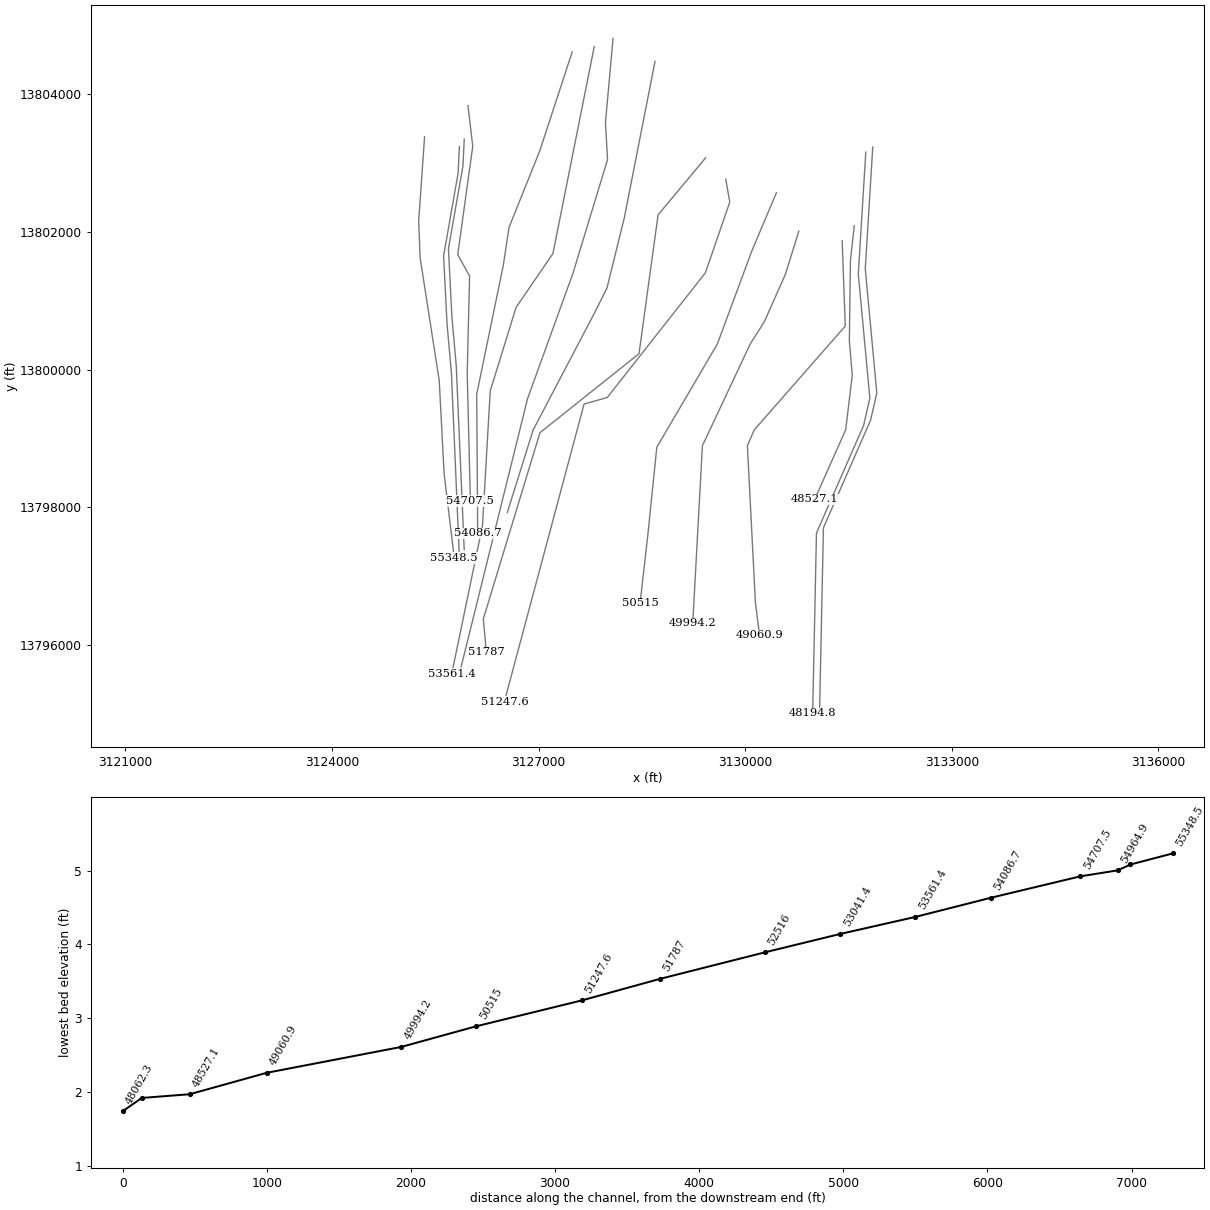
HEC-RAS study C100-00-00.prj: C100-00-00

--- C100-00-00.g01 (geometry) --- (continued)

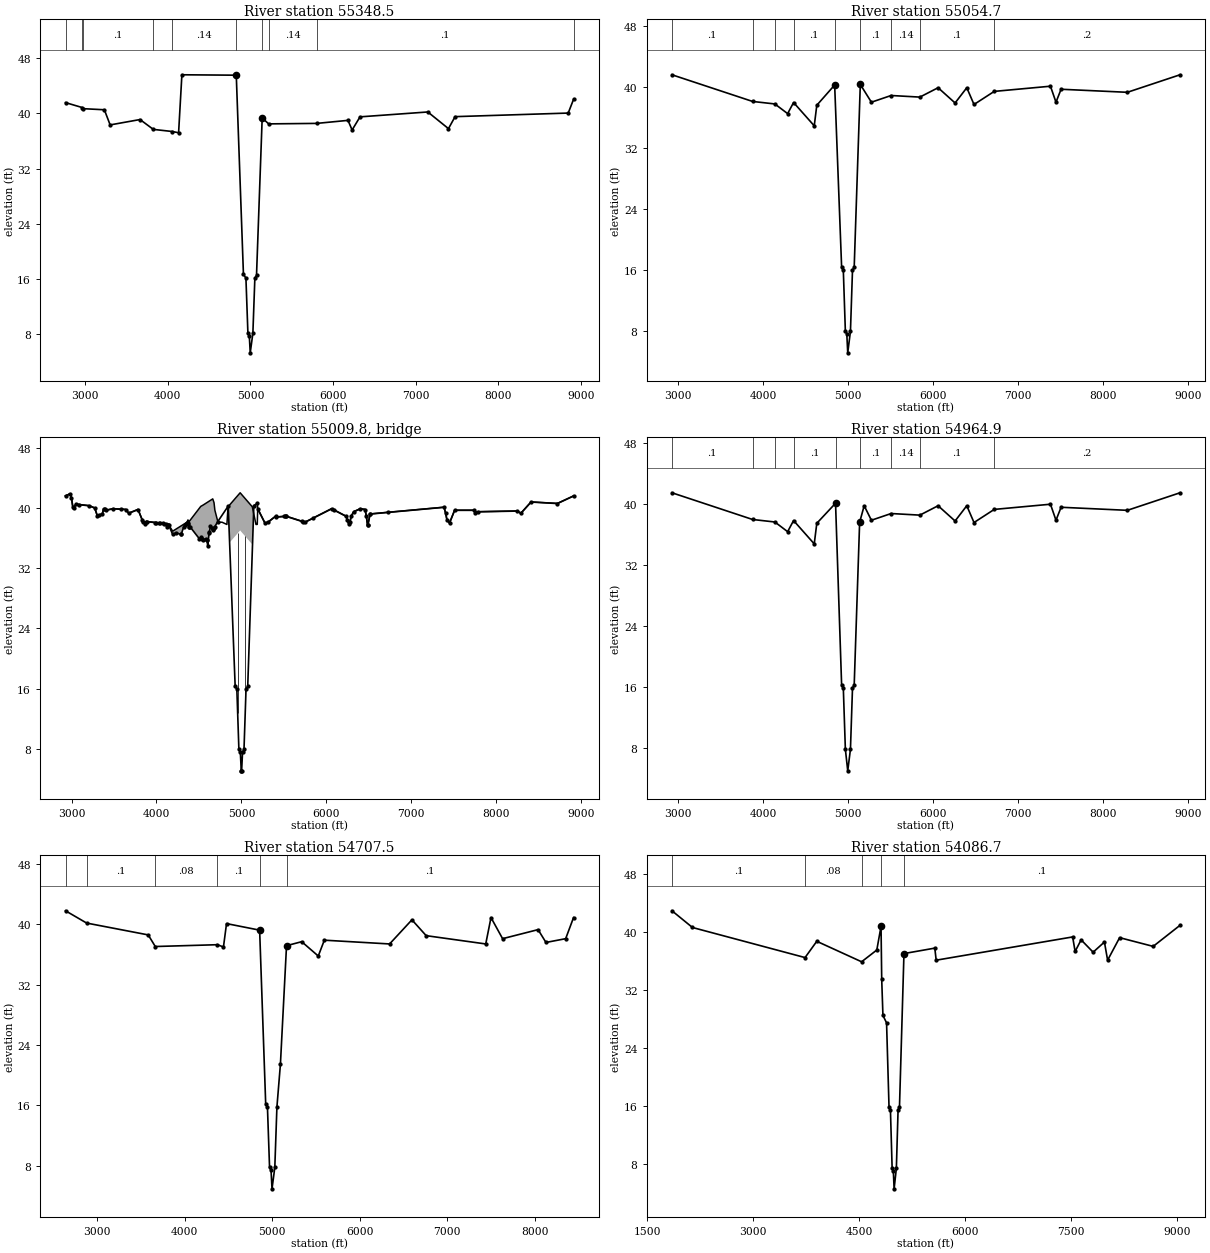
Type RM Length L Ch R = 1 ,55348.5 ,330.98,293.83,286.71
BEGIN DESCRIPTION:
Cross Section 55804.0 - Interpolated
USACE Sims Bayou Rectification
Reach 6 Downstream of Cullen to SH-288
File No. HSC 409-16
END DESCRIPTION:
XS GIS Cut Line= 6
      3125344.07     13803375.64      3125258.86     13802150.65
      3125280.16     13801618.04      3125557.12     13799839.14
      3125627.74     13798492.29      3125775.48     13797266.66
#Sta/Elev= 30
  2763.3   41.57  2968.8   40.84  2973.4   40.69  3233.3   40.53  3303.3   38.33
  3664.9   39.11  3825.8   37.68    4057   37.37  4131.4   37.19  4171.3   45.61
 4829.17   45.55  4915.8   16.67    4946   16.07    4970    8.07  4986.9   7.732
    4998   5.232    5030    8.07    5054   16.07    5074   16.47 5142.61   39.34
  5221.2   38.48    5802   38.55  6180.6   38.99  6230.6   37.59  6326.2    39.5
  7146.2   40.21  7396.2   37.79  7476.2   39.53  8844.9   40.05  8909.4   42.04
#Mann= 10 ,-1 , 0
  2763.3      .1       0  2968.8     .14       0  2973.4      .1       0
  3825.8     .08       0    4057     .14       0 4829.17    .035       0
 5142.61      .1       0  5221.2     .14       0    5802      .1       0
  8909.4      .2       0
#XS Ineff= 2 , 0
       0 4829.17      39               0
Permanent Ineff=
       F       F
Bank Sta=4829.17,5142.61
XS Rating Curve= 0 ,0
Exp/Cntr=0.5,0.3

Type RM Length L Ch R = 1 ,55054.7 ,85.44,89.73,89.38
BEGIN DESCRIPTION:
Upstream Section of Bridge/Culvert/Weir
USACE Sims Bayou Rectification
Reach 6 Downstream of Cullen to SH-288
File No. HSC 409-16
END DESCRIPTION:
XS GIS Cut Line= 6
  3125850.01488413803235.8526877 3125830.774765513802846.3324694
 3125620.3949369 13801646.872598 3125670.064785113800666.5527082
 3125734.355010813799943.3625536 3125849.384964513797281.4525231
#Sta/Elev= 30
    2929   41.58  3877.9   38.08  4140.1   37.75  4290.5   36.48  4360.4   37.94
  4603.8   34.88  4633.8   37.58 4844.06   40.24    4926   16.32    4946   15.92
    4970    7.92  4986.9   7.582    4998   5.082    5030    7.92    5054   15.92
    5074   16.32 5145.96   40.31  5276.5   37.98  5508.8   38.86  5846.9   38.65
  6061.6   39.88  6261.6   37.88  6399.3   39.88  6484.3   37.68  6722.7    39.4
  7384.3   40.08  7449.3   37.98  7509.3   39.68  8289.3   39.28  8909.3   41.58
#Mann= 9 ,-1 , 0
    2929      .1       0  3877.9     .08       0  4140.1     .14       0
  4360.4      .1       0 4844.06    .035       0 5145.96      .1       0
  5508.8     .14       0  5846.9      .1       0  6722.7      .2       0
#XS Ineff= 2 , 0
       0 4844.06      39 5145.96       0   37.78
Permanent Ineff=
       F       F
Bank Sta=4844.06,5145.96
XS Rating Curve= 0 ,0
Exp/Cntr=0.5,0.3

Type RM Length L Ch R = 3 ,55009.8 ,,,
BEGIN DESCRIPTION:
CULLEN BLVD
Structure ID: C00-28
END DESCRIPTION:
Bridge Culvert--1,0,-1,-1, 0
Deck Dist Width WeirC Skew NumUp NumDn MinLoCord MaxHiCord MaxSubmerge Is_Ogee
10,74,2.6,0, 157, 157, , , 0.95, 0, 1,1,,
    2929    2984    2999    3014    3029    3049    3082  3207.6  3272.6  3302.6
    3319  3362.6  3377.6  3397.6  3407.6  3487.6    3584  3637.6  3672.6  3782.7
  3832.7  3837.7  3867.7  3877.9  3882.7    3982    3997  4026.7  4041.7  4071.7
  4086.7  4107.7  4122.7  4137.7  4140.1  4145.5  4190.5  4230.5    4290  4290.5
  4320.5  4340.8    4360  4360.4  4365.8    4370  4380.8    4385  4395.8  4505.8
    4520  4520.8  4537.2  4548.8  4578.8  4588.8  4593.8  4603.8  4618.8  4623.8
  4633.8  4658.8  4662.2  4663.8  4677.2  4687.2  4721.2  4736.2  4737.2 4740.63
  4741.2  4746.2  4751.2  4756.2  4761.2  4766.2  4771.2 4771.38  4786.2  4796.2
  4801.2 4828.97  4841.2 4841.96  4846.2  4851.2 4857.11  4857.2 4860.48 4860.57
 4876.25 4891.75  4917.3 4926.39 4941.98 4950.38 4953.84 4971.42 4984.85    5000
 5028.58 5045.03  5048.5 5056.36 5073.78 5110.16 5118.82 5124.79 5127.74 5139.92
 5140.03  5142.8 5142.89 5171.04 5186.19  5191.5  5276.5  5311.5  5401.5  5411.2
  5505.3  5508.8  5518.8  5526.2  5713.8  5728.8  5746.6  5846.9  6061.6  6093.8
  6231.6  6244.9  6261.6  6276.6  6291.6  6321.6  6399.3  6454.3  6469.3  6484.3
  6489.3  6514.3  6515.4  6722.7  7384.3  7404.3  7419.3  7449.3  7509.3  7734.3
  7749.3  7779.3  8244.3  8289.3  8409.3  8719.3  8909.3
    41.6    41.9    41.4    40.2      40    40.5   40.47   40.31   40.01   39.01
   39.06   39.21   39.91   39.91   39.71   39.91   39.85   39.81   39.31   39.81
   38.41   38.11   37.91   38.11   38.21   38.08   38.06   38.02      38   37.96
   37.94   37.91   37.51   37.81   37.78   37.71   36.91   37.19    37.6    37.6
   37.82   37.96    38.1   38.11   38.27    38.4   38.26    38.2   38.36   39.99
    40.2    40.2    40.3   40.38    40.6   40.67   40.71   40.78   40.89   40.92
      41   41.18    41.2   41.15    40.7    39.7   38.21   38.11   38.07    38.1
    38.1    38.1    38.1    38.1    38.1    38.1    38.1    38.1   38.02   37.97
   37.94    37.8   40.01   40.15   40.21   40.27   40.35   40.35   40.39   40.39
    40.6    40.8   41.13   41.25   41.45   41.56   41.61   41.84   42.01   41.81
   41.44   41.23   41.18   41.08   40.85   40.38   40.27   40.19   40.15   39.49
   39.48   39.33   39.33    37.8   37.81   39.91   38.01   38.11   38.91   38.81
   38.89   38.89    38.9   38.91   38.23   38.17   38.11   38.68   39.91   39.72
   38.91   38.47   37.91   38.11   38.91   39.51   39.91   39.81   39.01   37.71
   37.81   39.21   39.21   39.42    40.1    39.3    38.4      38    39.7    39.7
    39.4    39.5    39.6    39.3    40.8    40.6    41.6
                                                                                
                                                                                
                                                                                
                                                                                
                                                                                
                                                                                
                                                                                
                                                                                
                                    31.6    31.4   35.01    33.8   32.77   35.39
    35.6    35.8   36.13   36.25   36.45   36.56   36.61   36.84   37.01   36.81
   36.44   36.23   36.18   36.08   35.85   35.38   35.27   35.19   35.15   34.49
   33.11    33.8   35.01   36.82
                                                                                
                                                                                
                                                                                
                                                        
    2929    2984    2999    3014    3029    3049    3082  3207.6  3272.6  3302.6
    3319  3362.6  3377.6  3397.6  3407.6  3487.6    3584  3637.6  3672.6  3782.7
  3832.7  3837.7  3867.7  3877.9  3882.7    3982    3997  4026.7  4041.7  4071.7
  4086.7  4107.7  4122.7  4137.7  4140.1  4145.5  4190.5  4230.5    4290  4290.5
  4320.5  4340.8    4360  4360.4  4365.8    4370  4380.8    4385  4395.8  4505.8
    4520  4520.8  4537.2  4548.8  4578.8  4588.8  4593.8  4603.8  4618.8  4623.8
  4633.8  4658.8  4662.2  4663.8  4677.2  4687.2  4721.2  4736.2  4737.2 4740.63
  4741.2  4746.2  4751.2  4756.2  4761.2  4766.2  4771.2 4771.38  4786.2  4796.2
  4801.2 4828.97  4841.2 4841.96  4846.2  4851.2 4857.11  4857.2 4860.48 4860.57
 4876.25 4891.75  4917.3 4926.39 4941.98 4950.38 4953.84 4971.42 4984.85    5000
 5028.58 5045.03  5048.5 5056.36 5073.78 5110.16 5118.82 5124.79 5127.74 5139.92
 5140.03  5142.8 5142.89 5171.04 5186.19  5191.5  5276.5  5311.5  5401.5  5411.2
  5505.3  5508.8  5518.8  5526.2  5713.8  5728.8  5746.6  5846.9  6061.6  6093.8
  6231.6  6244.9  6261.6  6276.6  6291.6  6321.6  6399.3  6454.3  6469.3  6484.3
  6489.3  6514.3  6515.4  6722.7  7384.3  7404.3  7419.3  7449.3  7509.3  7734.3
  7749.3  7779.3  8244.3  8289.3  8409.3  8719.3  8909.3
    41.6    41.9    41.4    40.2      40    40.5   40.47   40.31   40.01   39.01
   39.06   39.21   39.91   39.91   39.71   39.91   39.85   39.81   39.31   39.81
   38.41   38.11   37.91   38.11   38.21   38.08   38.06   38.02      38   37.96
   37.94   37.91   37.51   37.81   37.78   37.71   36.91   37.19    37.6    37.6
   37.82   37.96    38.1   38.11   38.27    38.4   38.26    38.2   38.36   39.99
    40.2    40.2    40.3   40.38    40.6   40.67   40.71   40.78   40.89   40.92
      41   41.18    41.2   41.15    40.7    39.7   38.21   38.11   38.07    38.1
    38.1    38.1    38.1    38.1    38.1    38.1    38.1    38.1   38.02   37.97
   37.94    37.8   40.01   40.15   40.21   40.27   40.35   40.35   40.39   40.39
    40.6    40.8   41.13   41.25   41.45   41.56   41.61   41.84   42.01   41.81
   41.44   41.23   41.18   41.08   40.85   40.38   40.27   40.19   40.15   39.49
   39.48   39.33   39.33    37.8   37.81   39.91   38.01   38.11   38.91   38.81
   38.89   38.89    38.9   38.91   38.23   38.17   38.11   38.68   39.91   39.72
   38.91   38.47   37.91   38.11   38.91   39.51   39.91   39.81   39.01   37.71
   37.81   39.21   39.21   39.42    40.1    39.3    38.4      38    39.7    39.7
    39.4    39.5    39.6    39.3    40.8    40.6    41.6
                                                                                
                                                                                
                                                                                
                                                                                
                                                                                
                                                                                
                                                                                
                                                                                
                                   31.59   31.39      35   33.79   32.76   35.38
   35.59   35.79   36.12   36.24   36.44   36.55    36.6   36.83      37    36.8
   36.43   36.22   36.17   36.07   35.84   35.37   35.26   35.18   35.14   34.48
    33.1   33.79      35   36.81
                                                                                
                                                                                
                                                                                
                                                        
Pier Skew, UpSta & Num, DnSta & Num=  ,4955.5, 2 ,4955.5, 2 , 0 , 0 , 0 ,,
       2       2
   14.47   37.48
       2       2
   14.46   37.47
Pier Skew, UpSta & Num, DnSta & Num=  ,5045.4, 2 ,5045.4, 2 , 0 , 0 , 0 ,,
       2       2
   14.72   37.13
       2       2
   14.71   37.12
BR Coef= 1 , 1 , 0 ,1.25, 0 ,,,0.8,-1,1.2,0,
WSPro=,,,, 1 ,,,, 0 ,,,, 0 ,,,,-1 ,-1 ,-1 , 0 , 0 , 0 , 0 , 0
BR U #Sta/Elev= 123
    2929   41.58    2984   41.88    2999   41.38    3014   40.18    3029   39.98
    3049   40.48    3082   40.44  3207.6   40.28  3272.6   39.98  3302.6   38.98
    3319   39.03  3362.6   39.18  3377.6   39.88  3397.6   39.88  3407.6   39.68
  3487.6   39.88    3584   39.82  3637.6   39.78  3672.6   39.28  3782.7   39.78
  3832.7   38.38  3837.7   38.08  3867.7   37.88  3877.9   38.08  3882.7   38.18
    3982   38.05    3997   38.03  4026.7   37.99  4041.7   37.97  4071.7   37.93
  4086.7   37.91  4107.7   37.88  4122.7   37.48  4137.7   37.78  4140.1   37.75
  4145.5   37.68  4190.5   36.48  4230.5   36.68    4290   36.48  4290.5   36.48
  4320.5   37.48  4340.8   37.78    4360   37.93  4360.4   37.94  4365.8   37.98
    4370   37.84  4380.8   37.48    4385   37.48  4395.8   37.48  4505.8   35.88
    4520   36.07  4520.8   36.08  4537.2    35.9  4548.8   35.78  4578.8   35.88
  4588.8   35.68  4593.8   35.78  4603.8   34.88  4618.8   36.68  4623.8   36.78
  4633.8   37.58  4658.8   37.28  4662.2   37.14  4663.8   37.08  4677.2   37.34
  4687.2   37.53  4721.2   38.18 4844.06   40.24    4926   16.32    4946   15.92
    4970    7.92  4986.9    7.58    4998    5.08    5000    5.08    5002    5.08
  5013.1    7.58    5030    7.92    5054   15.92    5074   16.32 5145.96   40.31
 5186.19    40.6  5191.5   39.88  5276.5   37.98  5311.5   38.08  5401.5   38.88
  5411.2   38.78  5505.3   38.86  5508.8   38.86  5518.8   38.87  5526.2   38.88
  5713.8    38.2  5728.8   38.14  5746.6   38.08  5846.9   38.65  6061.6   39.88
  6093.8   39.69  6231.6   38.88  6244.9   38.44  6261.6   37.88  6276.6   38.08
  6291.6   38.88  6321.6   39.48  6399.3   39.88  6454.3   39.78  6469.3   38.98
  6484.3   37.68  6489.3   37.78  6514.3   39.18  6515.4   39.18  6722.7    39.4
  7384.3   40.08  7404.3   39.28  7419.3   38.38  7449.3   37.98  7509.3   39.68
  7734.3   39.68  7749.3   39.38  7779.3   39.48  8244.3   39.58  8289.3   39.28
  8409.3   40.78  8719.3   40.58  8909.3   41.58
BR U #Mann= 11
    2929      .1  3877.9     .08  4140.1     .14  4360.4      .1 4844.06    .035
    4926    .015    5074    .035 5145.96      .1  5508.8     .14  5846.9      .1
  6722.7      .2
BR D #Sta/Elev= 122
    2929   41.45    2984   41.75    2999   41.25    3014   40.05    3029   39.85
    3049   40.35    3082   40.31  3207.6   40.15  3272.6   39.85  3302.6   38.85
    3319    38.9  3362.6   39.05  3377.6   39.75  3397.6   39.75  3407.6   39.55
  3487.6   39.75    3584   39.69  3637.6   39.65  3672.6   39.15  3782.7   39.65
  3832.7   38.25  3837.7   37.95  3867.7   37.75  3877.9   37.95  3882.7   38.05
    3982   37.92    3997    37.9  4026.7   37.86  4041.7   37.84  4071.7    37.8
  4086.7   37.78  4107.7   37.75  4122.7   37.35  4137.7   37.65  4140.1   37.62
  4145.5   37.55  4190.5   36.35  4230.5   36.55    4290   36.35  4290.5   36.35
  4320.5   37.35  4340.8   37.65    4360    37.8  4360.4   37.81  4365.8   37.85
    4370   37.71  4380.8   37.35    4385   37.35  4395.8   37.35  4505.8   35.75
    4520   35.94  4520.8   35.95  4537.2   35.77  4548.8   35.65  4578.8   35.75
  4588.8   35.55  4593.8   35.65  4603.8   34.75  4618.8   36.55  4623.8   36.65
  4633.8   37.45  4658.8   37.15  4662.2   37.01  4663.8   36.95  4677.2   37.21
  4687.2    37.4  4721.2   38.05 4854.49   40.08    4926   16.24    4946   15.84
    4970    7.84  4986.9     7.5    4998       5    5000       5    5002       5
  5013.1     7.5    5030    7.84    5054   15.84    5074   16.24 5138.01   37.58
  5191.5   39.75  5276.5   37.85  5311.5   37.95  5401.5   38.75  5411.2   38.65
  5505.3   38.73  5508.8   38.73  5518.8   38.74  5526.2   38.75  5713.8   38.07
  5728.8   38.01  5746.6   37.95  5846.9   38.52  6061.6   39.75  6093.8   39.56
  6231.6   38.75  6244.9   38.31  6261.6   37.75  6276.6   37.95  6291.6   38.75
  6321.6   39.35  6399.3   39.75  6454.3   39.65  6469.3   38.85  6484.3   37.55
  6489.3   37.65  6514.3   39.05  6515.4   39.05  6722.7   39.27  7384.3   39.95
  7404.3   39.15  7419.3   38.25  7449.3   37.85  7509.3   39.55  7734.3   39.55
  7749.3   39.25  7779.3   39.35  8244.3   39.45  8289.3   39.15  8409.3   40.65
  8719.3   40.45  8909.3   41.45
BR D #Mann= 11
    2929      .1  3877.9     .08  4140.1     .14  4360.4      .1 4854.49    .035
    4926    .015    5074    .035 5138.01      .1  5508.8     .14  5846.9      .1
  6722.7      .2
BC Design=,, 0 ,, 0 ,,,,,,
BC HTab HWMax=41.88
BC Use User HTab Curves=0
BC User HTab FreeFlow(D)= 0

Type RM Length L Ch R = 1 ,54964.9 ,163.8,257.46,328.85
BEGIN DESCRIPTION:
Downstream Section of Bridge/Culvert/Weir
USACE Sims Bayou Rectification
Reach 6 Downstream of Cullen to SH-288
File No. HSC 409-16
END DESCRIPTION:
XS GIS Cut Line= 6
  3125920.35299813803340.8009686 3125901.113207513802951.2709078
 3125690.733050813801751.8110364 3125740.403227113800771.4908186
 3125804.6931247 13800048.300992 3125919.723078413797386.4011321
#Sta/Elev= 30
    2929   41.45  3877.9   37.95  4140.1   37.62  4290.5   36.35  4360.4   37.81
  4603.8   34.75  4633.8   37.45 4854.49   40.08    4926   16.24    4946   15.84
    4970    7.84    4998   5.002    5030    7.84    5054   15.84    5074   16.24
 5138.01   37.58  5191.5   39.75  5276.5   37.85  5508.8   38.73  5846.9   38.52
  6061.6   39.75  6261.6   37.75  6399.3   39.75  6484.3   37.55  6722.7   39.27
  7384.3   39.95  7449.3   37.85  7509.3   39.55  8289.3   39.15  8909.3   41.45
#Mann= 9 ,-1 , 0
    2929      .1       0  3877.9     .08       0  4140.1     .14       0
  4360.4      .1       0 4854.49    .035       0 5138.01      .1       0
  5508.8     .14       0  5846.9      .1       0  6722.7      .2       0
#XS Ineff= 2 , 0
       0 4854.49      39 5138.01       0   37.15
Permanent Ineff=
       F       F
Bank Sta=4854.49,5138.01
XS Rating Curve= 0 ,0
Exp/Cntr=0.5,0.3

Type RM Length L Ch R = 1 ,54707.5 ,734.06,620.75,528.28
BEGIN DESCRIPTION:
Cross Section 55079.6
USACE Sims Bayou Rectification
Reach 6 Downstream of Cullen to SH-288
File No. HSC 409-16
END DESCRIPTION:
XS GIS Cut Line= 6
     3125974.235    13803827.942      3126043.63      13803238.1
      3125825.66     13801666.42      3125997.74     13801356.67
      3125963.32     13799945.61      3126009.21    13798094.177
#Sta/Elev= 30
  2640.6    41.8    2882   40.17  3584.7    38.6  3665.5   37.06  4374.4    37.3
  4443.8      37  4478.8    40.1  4856.8   39.23    4926   16.16    4946   15.76
    4970    7.76  4986.9   7.422    4998   4.922    5030    7.76    5054   15.76
    5094   21.45 5163.77   37.17    5337    37.7  5526.1    35.8  5595.4    37.9
  6340.4    37.4  6595.4    40.6    6758    38.5    7438    37.4    7498    40.9
  7630.4    38.1  8035.4    39.3  8125.4    37.6  8350.4    38.1  8440.4    40.9
#Mann= 6 ,-1 , 0
  2640.6      .2       0    2882      .1       0  3665.5     .08       0
  4374.4      .1       0  4856.8    .035       0 5163.77      .1       0
#XS Ineff= 2 , 0
       0  4856.8      39               0
Permanent Ineff=
       F       F
Bank Sta=4856.8,5163.77
XS Rating Curve= 0 ,0
Exp/Cntr=0.3,0.1

Type RM Length L Ch R = 1 ,54086.7 ,635.56,525.35,453.83
BEGIN DESCRIPTION:
Cross Section 54410.2-Interpolated
USACE Sims Bayou Rectification
Reach 6 Downstream of Cullen to SH-288
File No. HSC 409-16
END DESCRIPTION:
XS GIS Cut Line= 6
     3127487.607    13804607.186      3127016.67     13803171.38
      3126570.87      13802062.9      3126486.53     13801508.66
      3126100.97     13799641.12     3126115.284    13797622.243
#Sta/Elev= 30
  1853.2    42.9  2143.2    40.6  3737.2   36.46  3903.2    38.7    4538   35.88
    4753    37.5  4812.9   40.76  4822.4   33.47  4839.8    28.5  4891.2   27.47
    4926   15.87    4946   15.47    4970    7.47  4986.9   7.132    4998   4.632
    5030    7.47    5054   15.47    5074   15.87 5137.42   37.01    5574   37.76
  5593.6    36.1  7525.5    39.3  7560.5    37.3  7645.5    38.9  7815.5    37.2
  7975.5    38.6  8020.5    36.1  8190.5    39.2  8665.5      38  9045.5    40.9
#Mann= 5 ,-1 , 0
  1853.2      .1       0  3737.2     .08       0    4538      .1       0
  4812.9    .035       0 5137.42      .1       0
#XS Ineff= 2 , 0
       0  4812.9      39               0
Permanent Ineff=
       F       F
Bank Sta=4812.9,5137.42
XS Rating Curve= 0 ,0
Exp/Cntr=0.3,0.1

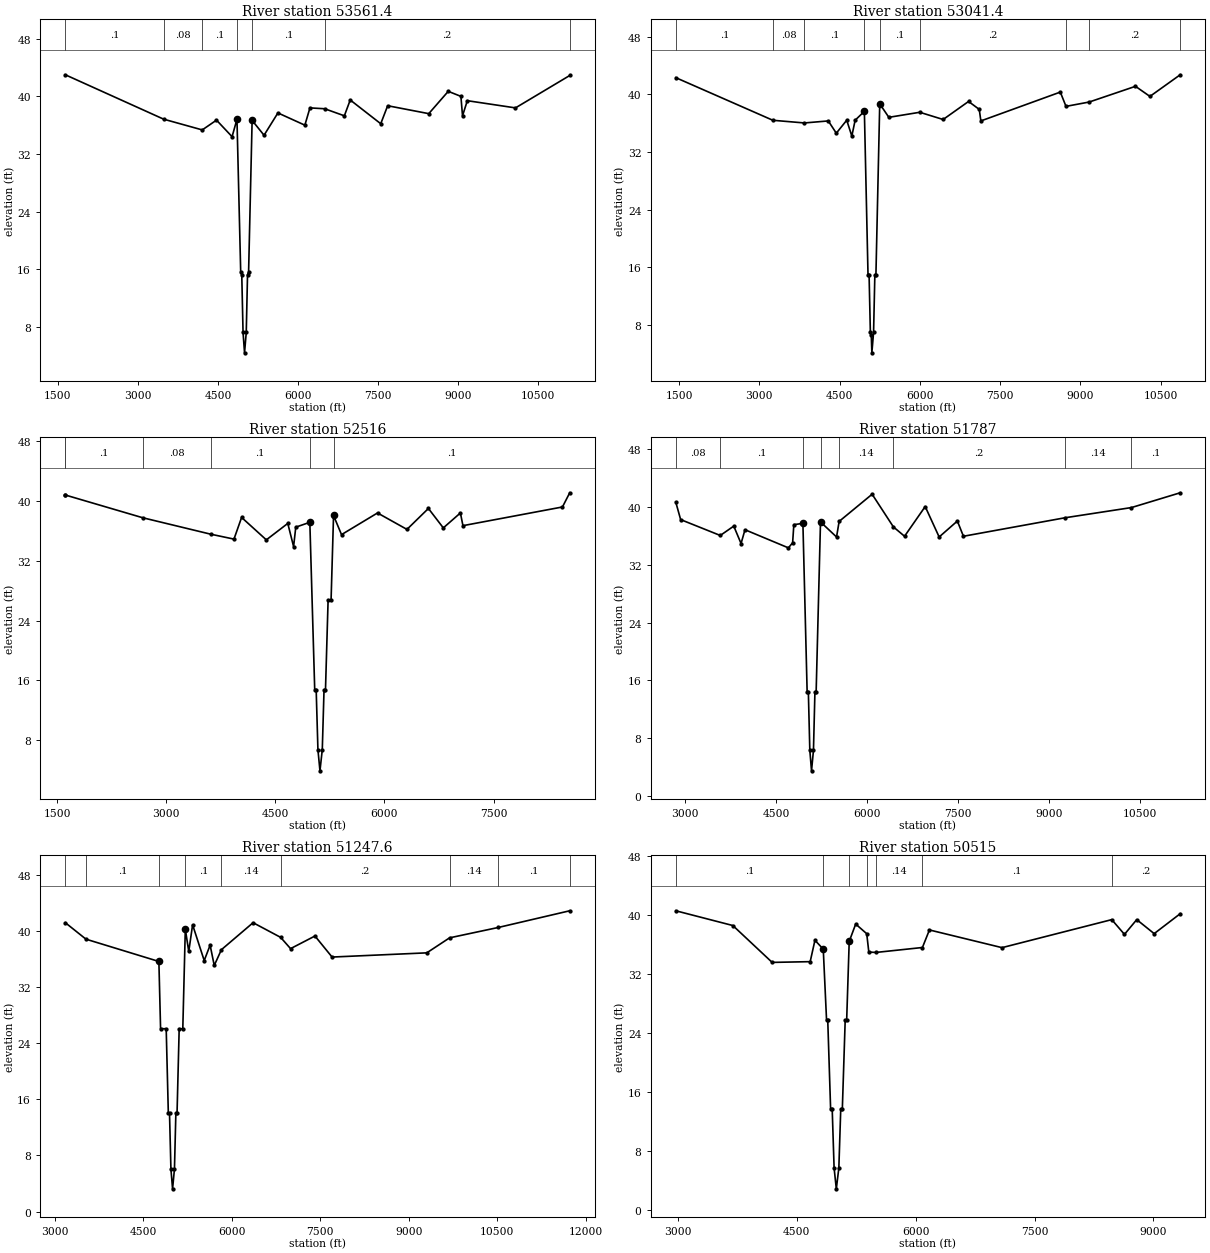
Type RM Length L Ch R = 1 ,53561.4 ,451.43,519.96,561.5
BEGIN DESCRIPTION:
Cross Section 53844.4
USACE Sims Bayou Rectification
Reach 6 Downstream of Cullen to SH-288
File No. HSC 409-16
END DESCRIPTION:
XS GIS Cut Line= 6
     3127807.956     13804684.64      3127207.72     13801682.12
      3126672.34     13800900.46      3126297.57     13799690.51
      3126185.14     13797736.38      3125737.81    13795583.926
#Sta/Elev= 30
  1639.9      43  3483.4   36.83  4205.7   35.34  4472.5    36.7  4764.4    34.4
  4856.1   36.82    4926   15.61    4946   15.21    4970    7.21    4998   4.372
    5030    7.21    5054   15.21    5074   15.61    5140   36.66  5363.4    34.6
  5623.4    37.7  6128.3      36  6223.3    38.4  6499.9   38.28  6868.3    37.3
  6978.3    39.5  7549.9    36.2  7679.9    38.7  8449.9    37.6  8814.9    40.7
  9052.3      40  9082.3    37.3  9172.3    39.4 10074.9    38.4 11091.2    42.9
#Mann= 7 ,-1 , 0
  1639.9      .1       0  3483.4     .08       0  4205.7      .1       0
  4856.1    .035       0    5140      .1       0  6499.9      .2       0
 11091.2      .2       0
Bank Sta=4856.1,5140
XS Rating Curve= 0 ,0
Exp/Cntr=0.3,0.1

Type RM Length L Ch R = 1 ,53041.4 ,537.51,525.43,511.17
BEGIN DESCRIPTION:
Cross Section 53270.1
USACE Sims Bayou Rectification
Reach 5 Mykawa to Downstream of Cullen
File No. HSC 409-15
END DESCRIPTION:
XS GIS Cut Line= 6
     3128080.903    13804803.758      3127970.72     13803583.84
      3128000.67     13803044.72      3127498.99      13801397.4
      3126838.58     13799574.39     3125875.553    13795690.835
#Sta/Elev= 30
  1438.2    42.3  3252.8   36.39  3842.4   36.02  4288.5    36.3  4438.5    34.6
  4633.5    36.4  4728.5    34.2  4790.5    36.4 4963.05   37.63    5031   14.98
    5051   14.98    5075    6.98  5091.9   6.642    5103   4.142    5135    6.98
    5159   14.98    5179   14.98 5250.07   38.67  5420.5    36.8  5998.2    37.5
  6435.2    36.5  6910.3      39  7110.3    37.9  7140.3    36.3  8625.3    40.3
  8731.7   38.32  9164.8   38.92 10030.3    41.1 10300.3    39.7 10866.1    42.7
#Mann= 9 ,-1 , 0
  1438.2      .1       0  3252.8     .08       0  3842.4      .1       0
 4963.05    .035       0 5250.07      .1       0  5998.2      .2       0
  8731.7      .2       0  9164.8      .2       0 10866.1      .2       0
Bank Sta=4963.05,5250.07
XS Rating Curve= 0 ,0
Exp/Cntr=0.3,0.1

Type RM Length L Ch R = 1 ,52516   ,627.2,728.96,863.71
BEGIN DESCRIPTION:
Cross Section 52749.6-Interpolated
USACE Sims Bayou Rectification
Reach 5 Mykawa to Downstream of Cullen
File No. HSC 409-15
END DESCRIPTION:
XS GIS Cut Line= 6
     3128690.254    13804469.811      3128245.63     13802207.49
      3127992.61     13801183.35      3127811.88     13800821.89
      3126920.28     13799123.03     3126545.296    13797926.675
#Sta/Elev= 30
    1611    40.8  1611.1    40.8  2675.1   37.76    3610   35.56  3930.4    34.9
  4035.4    37.8  4375.4    34.8  4670.4      37  4750.4    33.9  4780.4    36.5
 4973.74   37.15    5041   14.73    5061   14.73    5085    6.73    5113   3.892
    5145    6.73    5169   14.73    5189   14.73    5225   26.73  5265.8   26.73
  5299.8   38.06  5409.5    35.5  5904.5    38.4  6309.5    36.2  6604.5      39
  6809.5    36.4  7044.5    38.4  7079.5    36.7  8448.1    39.2  8548.1    41.1
#Mann= 6 ,-1 , 0
    1611      .2       0  1611.1      .1       0  2675.1     .08       0
    3610      .1       0 4973.74    .035       0  5299.8      .1       0
Bank Sta=4973.74,5299.8
XS Rating Curve= 0 ,0
Exp/Cntr=0.3,0.1

Type RM Length L Ch R = 1 ,51787   ,658.32,539.37,383.44
BEGIN DESCRIPTION:
Cross Section 51944.0
USACE Sims Bayou Rectification
Reach 5 Mykawa to Downstream of Cullen
File No. HSC 409-15
END DESCRIPTION:
XS GIS Cut Line= 6
      3129425.75    13803071.685      3128734.47     13802243.52
      3128457.42     13800229.31      3127019.54     13799084.15
      3126197.03     13796382.79     3126241.444    13795898.373
#Sta/Elev= 30
  2847.8    40.6  2927.8    38.2  3580.7   36.01    3803    37.3    3923    34.9
    3988    36.8    4703    34.3  4772.7      35  4792.7    37.5 4942.07   37.68
    5012   14.37    5032   14.37    5056    6.37    5084   3.532    5116    6.37
    5140   14.37    5160   14.37    5232   37.88  5496.3    35.8  5539.1   37.95
  6082.5    41.7  6432.9   37.19  6616.8    35.9  6956.8      40  7186.8    35.8
  7486.8      38  7586.8    35.9  9259.2   38.45   10355   39.86   11158    41.9
#Mann= 8 ,-1 , 0
  2847.8     .08       0  3580.7      .1       0 4942.07    .035       0
    5232      .1       0  5539.1     .14       0  6432.9      .2       0
  9259.2     .14       0   10355      .1       0
Bank Sta=4942.07,5232
XS Rating Curve= 0 ,0
Exp/Cntr=0.3,0.1

Type RM Length L Ch R = 1 ,51247.6 ,685.25,732.64,768.5
BEGIN DESCRIPTION:
Cross Section 51309.4
USACE Sims Bayou Rectification
Reach 5 Mykawa to Downstream of Cullen
File No. HSC 409-15
END DESCRIPTION:
XS GIS Cut Line= 6
     3129717.155    13802762.761      3129775.28     13802427.72
      3129421.85     13801403.39      3127996.18     13799594.34
      3127660.26     13799500.42     3126503.449    13795185.389
#Sta/Elev= 30
  3180.8    41.2  3530.8   38.85 4766.04   35.67  4794.8   26.08    4890   26.08
    4926   14.08    4946   14.08    4970    6.08    4998   3.242    5030    6.08
    5054   14.08    5074   14.08    5110   26.08  5171.3   26.08  5213.9   40.28
  5272.4    37.1  5337.4    40.9  5534.2    35.8  5634.2      38  5704.2    35.1
  5825.5   37.35  6362.3    41.2  6828.8   39.11  6997.3    37.5  7410.7    39.3
  7700.7    36.3  9305.7    36.9  9691.8   39.04 10517.4   40.52 11727.6    42.9
#Mann= 9 ,-1 , 0
  3180.8     .08       0  3530.8      .1       0 4766.04    .035       0
  5213.9      .1       0  5825.5     .14       0  6828.8      .2       0
  9691.8     .14       0 10517.4      .1       0 11727.6      .2       0
Bank Sta=4766.04,5213.9
XS Rating Curve= 0 ,0
Exp/Cntr=0.3,0.1

Type RM Length L Ch R = 1 ,50515   ,543.59,520.81,491.47
BEGIN DESCRIPTION:
Cross Section 50588.5-Interpolated
USACE Sims Bayou Rectification
Reach 5 Mykawa to Downstream of Cullen
File No. HSC 409-15
END DESCRIPTION:
XS GIS Cut Line= 6
     3130452.299    13802563.892      3130094.19     13801716.13
      3129595.06     13800370.64      3128716.15     13798873.25
      3128588.81     13797629.21     3128473.127    13796611.224
#Sta/Elev= 30
  2971.8    40.6  3691.8    38.6  4188.2    33.6  4668.2    33.7  4728.2    36.6
  4833.2    35.4    4875   25.73    4890   25.73    4926   13.73    4946   13.73
    4970    5.73    4998   2.892    5030    5.73    5054   13.73    5074   13.73
    5110   25.73  5128.6   25.73 5160.74   36.44  5242.6    38.8  5381.9   37.49
  5408.3      35  5498.1   34.95  6084.9   35.62  6173.3      38  7089.6    35.6
  8474.8    39.4  8635.1    37.4  8790.1    39.4  9010.1    37.5  9338.6    40.2
#Mann= 7 ,-1 , 0
  2971.8      .1       0  4833.2    .035       0 5160.74     .14       0
  5381.9      .1       0  5498.1     .14       0  6084.9      .1       0
  8474.8      .2       0
Bank Sta=4833.2,5160.74
XS Rating Curve= 0 ,0
Exp/Cntr=0.3,0.1

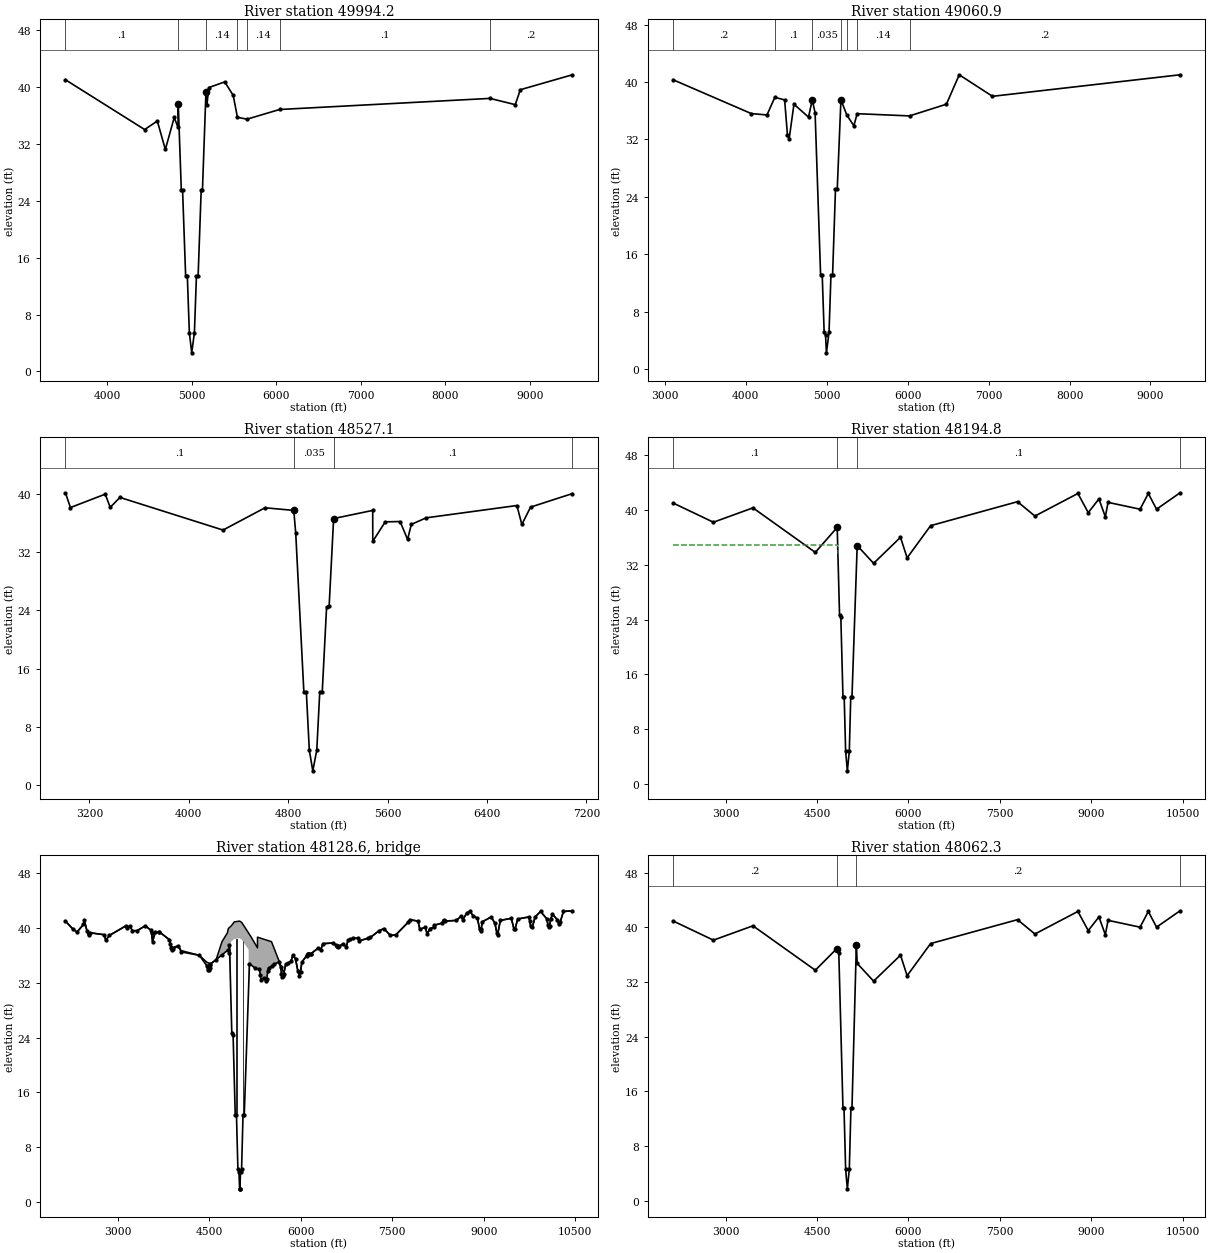
Type RM Length L Ch R = 1 ,49994.2 ,987.84,933.27,882.85
BEGIN DESCRIPTION:
Cross Section 50046.3-Interpolated
USACE Sims Bayou Rectification
Reach 5 Mykawa to Downstream of Cullen
File No. HSC 409-15
END DESCRIPTION:
XS GIS Cut Line= 6
     3130778.325    13802007.397      3130582.47     13801379.76
      3130278.65     13800696.16      3130072.49     13800370.64
      3129378.04     13798894.95     3129237.915    13796319.701
#Sta/Elev= 30
  3503.2      41  4440.9      34  4590.9    35.2  4685.9    31.2  4790.9    35.7
  4835.9    34.3 4838.56    37.6    4875   25.45    4890   25.45    4926   13.45
    4946   13.45    4970    5.45    4998   2.612    5030    5.45    5054   13.45
    5074   13.45    5110   25.45    5125   25.45 5166.26   39.21    5179    37.5
    5199    39.9  5389.3    40.7  5489.3    38.8  5539.3   35.72  5652.9   35.46
  6038.2   36.82  8529.1   38.38  8828.5    37.5  8888.5    39.6  9504.2    41.7
#Mann= 7 ,-1 , 0
  3503.2      .1       0 4838.56    .035       0 5166.26     .14       0
  5539.3      .1       0  5652.9     .14       0  6038.2      .1       0
  8529.1      .2       0
Bank Sta=4838.56,5166.26
XS Rating Curve= 0 ,0
Exp/Cntr=0.3,0.1

Type RM Length L Ch R = 1 ,49060.9 ,409.66,533.86,675.7
BEGIN DESCRIPTION:
Cross Section 49090.1
USACE Sims Bayou Rectification
Reach 5 Mykawa to Downstream of Cullen
File No. HSC 409-15
END DESCRIPTION:
XS GIS Cut Line= 6
     3131407.165    13801870.592      3131452.54     13800630.65
      3130130.43      13799124.4      3130031.36     13798896.41
      3130147.67     13796617.45     3130208.601    13796146.249
#Sta/Elev= 30
  3105.5    40.3  4068.9    35.6  4263.9    35.4  4360.9   37.86  4481.9    37.5
  4516.9    32.6  4536.9      32  4596.9    36.9  4776.9    35.1    4823    37.5
  4858.2    35.7    4926    13.1    4946    13.1    4970     5.1  4986.9   4.762
    4998   2.262    5030     5.1    5054    13.1    5074    13.1    5110    25.1
  5131.7    25.1    5177    37.5  5250.7   35.37  5336.5    33.9  5377.8   35.58
  6024.4   35.27  6479.6    36.9  6638.2      41  7048.2      38  9365.2      41
#Mann= 7 ,-1 , 0
  3105.5      .2       0  4360.9      .1       0    4823    .035       0
    5177     .14       0  5250.7      .1       0  5377.8     .14       0
  6024.4      .2       0
Bank Sta=4823,5177
XS Rating Curve= 0 ,0
Exp/Cntr=0.3,0.1

Type RM Length L Ch R = 1 ,48527.1 ,332.21,332.32,322.12
BEGIN DESCRIPTION:
Cross Section 48555.0 - Interpolated
USACE Sims Bayou Rectification
Reach 5 Mykawa to Downstream of Cullen
File No. HSC 409-15
END DESCRIPTION:
XS GIS Cut Line= 6
      3131583.43    13802086.809      3131527.61     13801580.76
      3131511.63     13800414.36      3131554.24     13799919.03
      3131458.37     13799125.45     3131008.051    13798117.565
#Sta/Elev= 30
    3008   40.15    3048   38.12    3328   39.96    3368   38.15  3446.7   39.51
  4275.8   35.03  4613.4   38.09    4845   37.73 4860.62   34.61    4926   12.81
    4946   12.81    4970    4.81    4998   1.972    5030    4.81    5054   12.81
    5074   12.81 5108.89   24.44 5129.66   24.65 5165.54   36.61    5480   37.73
  5480.6   33.48  5580.6   36.16  5700.6    36.2  5760.6   33.74  5790.6   35.81
  5909.9   36.71  6639.9    38.4  6679.9    35.8  6749.9   38.18  7086.1   40.04
#Mann= 4 ,-1 , 0
    3008      .1       0    4845    .035       0 5165.54      .1       0
  7086.1      .2       0
Bank Sta=4845,5165.54
XS Rating Curve= 0 ,0
Exp/Cntr=0.5,0.3

Type RM Length L Ch R = 1 ,48194.8 ,128.87,132.42,142.85
BEGIN DESCRIPTION:
Upstream Section of Bridge/Culvert/Weir
USACE Sims Bayou Rectification
Reach 5 Mykawa to Downstream of Cullen
File No. HSC 409-15
END DESCRIPTION:
XS GIS Cut Line= 6
      3131750.41     13803152.35      3131641.57     13801383.81
       3131809.3     13799586.74      3131719.44     13799191.39
      3131034.19      13797629.5       3130979.1     13795013.41
#Sta/Elev= 30
  2141.7   41.01  2801.7   38.21  3449.9   40.31  4472.7   33.81 4831.61   37.46
  4870.2    24.6  4891.1   24.39    4926   12.76    4946   12.76    4970    4.76
    4998   1.922    5030    4.76    5054   12.76    5074   12.76  5159.4   34.81
  5428.6   32.21  5869.6   36.01  5978.4   33.01  6363.4   37.71  7788.7   41.21
  8073.7   39.11  8778.7   42.41  8948.7   39.61  9123.7   41.61  9228.7   39.01
  9273.7   41.11  9798.7   40.11  9933.7   42.41 10068.7   40.11 10454.5   42.51
#Mann= 4 ,-1 , 0
  2141.7      .1       0 4831.61    .035       0  5159.4      .1       0
 10454.5      .2       0
#XS Ineff= 2 , 0
       0 4843.16   34.84 5155.44       0   33.27
Permanent Ineff=
       F       F
Bank Sta=4831.61,5159.4
XS Rating Curve= 0 ,0
Exp/Cntr=0.5,0.3

Type RM Length L Ch R = 3 ,48128.6 ,,,
BEGIN DESCRIPTION:
M.L. KING BLVD - Skew 40 Degrees
Structure ID: C00-26
END DESCRIPTION:
Bridge Culvert--1,0,-1,-1, 0
Deck Dist Width WeirC Skew NumUp NumDn MinLoCord MaxHiCord MaxSubmerge Is_Ogee
26.41,106,2.6,0, 156, 156, , , 0.95, 0, 1,1,,
2141.699  2266.72331.699  2436.72451.699  2496.7  2521.7  2541.7  2781.72801.699
  2861.7  3131.7  3146.73201.6993236.6993316.699  3449.9  3539.9  3554.9  3569.9
  3614.93667.699  3683.6  3843.6  3858.6  3868.63888.599  3913.6  3993.6  4038.6
4337.7014457.699  4472.7  4492.7  4502.7  4512.7  4517.74520.399  4612.84708.919
 4796.83 4812.834818.819 4857.784911.831    50005032.831 5145.755178.8315184.829
 5290.83 5290.83  5323.6  5338.65348.5995398.6015428.601  5443.6  5458.6  5473.6
 5520.88  5559.6  5639.65669.601  5684.65699.601  5714.6  5722.3  5754.6  5787.3
  5839.65869.601  5914.6  5953.3  5978.4  5998.46018.399  6097.3  6102.3  6112.3
6118.3996127.2996127.799  6162.8  6163.4  6278.4  6328.4  6363.46535.899  6577.8
  6587.86597.7996615.899  6634.1  6695.9  6745.9  6775.96809.1016861.701  6946.7
  6956.7  7095.5  7141.7  7285.8  7365.87470.799  7560.8  7758.7  7788.77923.699
  7953.7  8043.78073.6998118.699  8188.78193.7018313.6998343.699  8373.7  8553.7
8628.6998658.699  8723.7  8778.78823.6998898.699  8933.7  8948.7  8958.7  8978.7
  9123.79183.6999218.699  9228.7  9273.7  9453.79498.6999513.699  9558.7  9738.7
  9758.7  9768.79798.699  9843.7  9933.7 10038.7 10053.7 10068.7 10083.7 10098.7
 10128.7 10208.7 10233.7 10253.7 10308.7 10454.5
      41    39.8    39.4    40.5    41.1    39.5    38.9    39.3      39    38.2
    38.9    40.3      40    40.3    39.6    39.6    40.3    39.7    39.2      38
    39.4   39.41   39.41   38.31   37.71   37.31   37.26    37.2   37.41    36.7
   36.01   35.02   34.96   34.88   34.84    34.8   34.78   34.77   35.38      38
   39.27    39.9   39.97   40.28    40.9      41    40.8   39.25    38.8   38.71
    37.1   38.66   38.57   38.52   38.49   38.35   38.26   38.22   38.18   38.14
      38   37.12   35.29    34.6   34.26   33.92   33.58    33.4   34.71   34.86
   35.11   36.01   35.51   33.71    33.6   33.69   35.01   35.96   36.02   36.14
   36.21   36.21   36.21   36.21   36.21   37.01   36.81   37.71   37.81    37.5
   37.42   37.35   37.21   37.32   37.71   37.21   38.21   38.33   38.51   38.51
   38.11   38.49    38.6    39.6    39.9    38.9      39    40.8    41.2      41
    39.8    40.1    39.1    39.9    40.1    40.4    40.7    41.2      41    41.1
    41.7    41.2    42.2    42.4    41.8    41.4    39.8    39.6    39.8    40.9
    41.6    40.7    39.2      39    41.1    41.4    39.8    39.8    41.3    41.6
      41    40.3    40.1    41.6    42.4    41.3    40.4    40.1    40.3    41.3
      42    41.2    40.5    40.8    42.4    42.5
                                                                                
                                                                                
                                                                                
                                                                                
                              38    38.4    38.5    38.3   36.84
                                                                                
                                                                                
                                                                                
                                                                                
                                                                                
                                                                                
                                                                                
                                                                                
                                                                                
                                                                                
                                                
2141.699  2266.72331.699  2436.72451.699  2496.7  2521.7  2541.7  2781.72801.699
  2861.7  3131.7  3146.73201.6993236.6993316.699  3449.9  3539.9  3554.9  3569.9
  3614.93667.699  3683.6  3843.6  3858.6  3868.63888.599  3913.6  3993.6  4038.6
4337.7014457.699  4472.7  4492.7  4502.7  4512.7  4517.74520.399  4612.84708.919
 4796.83 4812.834818.819 4857.784911.831    50005032.831 5145.755178.8315184.829
 5290.83 5290.83  5323.6  5338.65348.5995398.6015428.601  5443.6  5458.6  5473.6
 5520.88  5559.6  5639.65669.601  5684.65699.601  5714.6  5722.3  5754.6  5787.3
  5839.65869.601  5914.6  5953.3  5978.4  5998.46018.399  6097.3  6102.3  6112.3
6118.3996127.2996127.799  6162.8  6163.4  6278.4  6328.4  6363.46535.899  6577.8
  6587.86597.7996615.899  6634.1  6695.9  6745.9  6775.96809.1016861.701  6946.7
  6956.7  7095.5  7141.7  7285.8  7365.87470.799  7560.8  7758.7  7788.77923.699
  7953.7  8043.78073.6998118.699  8188.78193.7018313.6998343.699  8373.7  8553.7
8628.6998658.699  8723.7  8778.78823.6998898.699  8933.7  8948.7  8958.7  8978.7
  9123.79183.6999218.699  9228.7  9273.7  9453.79498.6999513.699  9558.7  9738.7
  9758.7  9768.79798.699  9843.7  9933.7 10038.7 10053.7 10068.7 10083.7 10098.7
 10128.7 10208.7 10233.7 10253.7 10308.7 10454.5
      41    39.8    39.4    40.5    41.1    39.5    38.9    39.3      39    38.2
    38.9    40.3      40    40.3    39.6    39.6    40.3    39.7    39.2      38
    39.4   39.41   39.41   38.31   37.71   37.31   37.26    37.2   37.41    36.7
   36.01   35.02   34.96   34.88   34.84    34.8   34.78   34.77   35.38      38
   39.27    39.9   39.97   40.28    40.9      41    40.8   39.25    38.8   38.71
    37.1   38.66   38.57   38.52   38.49   38.35   38.26   38.22   38.18   38.14
      38   37.12   35.29    34.6   34.26   33.92   33.58    33.4   34.71   34.86
   35.11   36.01   35.51   33.71    33.6   33.69   35.01   35.96   36.02   36.14
   36.21   36.21   36.21   36.21   36.21   37.01   36.81   37.71   37.81    37.5
   37.42   37.35   37.21   37.32   37.71   37.21   38.21   38.33   38.51   38.51
   38.11   38.49    38.6    39.6    39.9    38.9      39    40.8    41.2      41
    39.8    40.1    39.1    39.9    40.1    40.4    40.7    41.2      41    41.1
    41.7    41.2    42.2    42.4    41.8    41.4    39.8    39.6    39.8    40.9
    41.6    40.7    39.2      39    41.1    41.4    39.8    39.8    41.3    41.6
      41    40.3    40.1    41.6    42.4    41.3    40.4    40.1    40.3    41.3
      42    41.2    40.5    40.8    42.4    42.5
                                                                                
                                                                                
                                                                                
                                                                                
                              38   38.35   38.45   38.25   36.84
                                                                                
                                                                                
                                                                                
                                                                                
                                                                                
                                                                                
                                                                                
                                                                                
                                                                                
                                                                                
                                                
Pier Skew, UpSta & Num, DnSta & Num=  ,4946.5, 4 ,4946.5, 4 , 3 , 3 , 0 ,,
       3       3       7       7
       5    36.8    36.8      42
       3       3       7       7
       5    36.8    36.8      42
Pier Skew, UpSta & Num, DnSta & Num=  ,5053.499, 4 ,5053.499, 4 , 3 , 3 , 0 ,,
       3       3       7       7
       5    36.7    36.7      42
       3       3       7       7
       5    36.7    36.7      42
BR Coef= 1 , 1 , 0 ,1.25, 0 ,,,0.8,-1,1.2,0,
WSPro=,,,, 1 ,,,, 0 ,,,, 0 ,,,,-1 ,-1 ,-1 , 0 , 0 , 0 , 0 , 0
BR U #Sta/Elev= 162
  2141.7   41.01  2266.7   39.81  2331.7   39.41  2436.7   40.51  2451.7   41.11
  2496.7   39.51  2521.7   38.91  2541.7   39.31  2781.7   39.01  2801.7   38.21
  2861.7   38.91  3131.7   40.31  3146.7   40.01  3201.7   40.31  3236.7   39.61
  3316.7   39.61  3449.9   40.31  3539.9   39.71  3554.9   39.21  3569.9   38.01
  3614.9   39.41  3667.7   39.41  3683.6   39.41  3843.6   38.31  3858.6   37.71
  3868.6   37.01  3888.6   36.81  3913.6   36.95  3993.6   37.41  4038.6   36.51
  4337.7   36.01  4457.7   34.51  4472.7   33.81  4492.7   34.11  4502.7   33.81
  4512.7   34.21  4517.7   34.61  4520.4   34.71  4612.8   35.38 4708.92   36.08
  4810.4   36.81  4825.4   36.41 4831.61   37.46  4870.2    24.6  4891.1   24.39
    4926   12.76    4946   12.76    4970    4.76  4986.9    4.42    4998    1.92
    5000    1.92    5002    1.92  5013.1    4.42    5030    4.76    5054   12.76
    5074   12.76  5159.4   34.81  5253.6   34.11  5323.6   34.01  5338.6   33.11
  5348.6   32.41  5398.6   32.71  5428.6   32.21  5443.6   32.51  5458.6   33.71
  5473.6   34.11 5520.88   34.44  5559.6   34.71  5639.6   35.01  5669.6   34.31
  5684.6   33.21  5699.6   32.81  5714.6   33.01  5722.3   33.34  5754.6   34.71
  5787.3   34.86  5839.6   35.11  5869.6   36.01  5914.6   35.51  5953.4   33.71
  5978.4   33.01  5998.4   33.61  6018.4   35.01  6097.3   35.96  6102.3   36.02
  6112.3   36.14  6118.4   36.21  6127.3   36.21  6127.8   36.21  6162.8   36.21
  6163.4   36.21  6278.4   37.01  6328.4   36.81  6363.4   37.71  6535.9   37.81
  6577.8    37.5  6587.8   37.42  6597.8   37.35  6615.9   37.21  6634.1   37.32
  6695.9   37.71  6745.9   37.21  6775.9   38.21  6809.1   38.33  6861.7   38.51
  6946.7   38.51  6956.7   38.11  7095.5   38.49  7141.7   38.61  7285.8   39.61
  7365.8   39.91  7470.8   38.91  7560.8   39.01  7758.7   40.81  7788.7   41.21
  7923.7   41.01  7953.7   39.81  8043.7   40.11  8073.7   39.11  8118.7   39.91
  8188.7   40.11  8193.7   40.41  8313.7   40.71  8343.7   41.21  8373.7   41.01
  8553.7   41.11  8628.7   41.71  8658.7   41.21  8723.7   42.21  8778.7   42.41
  8823.7   41.81  8898.7   41.41  8933.7   39.81  8948.7   39.61  8958.7   39.81
  8978.7   40.91  9123.7   41.61  9183.7   40.71  9218.7   39.21  9228.7   39.01
  9273.7   41.11  9453.7   41.41  9498.7   39.81  9513.7   39.81  9558.7   41.31
  9738.7   41.61  9758.7   41.01  9768.7   40.31  9798.7   40.11  9843.7   41.61
  9933.7   42.41 10038.7   41.31 10053.7   40.41 10068.7   40.11 10083.7   40.31
 10098.7   41.31 10128.7   42.01 10208.7   41.21 10233.7   40.51 10253.7   40.81
 10308.7   42.41 10454.5   42.51
BR U #Mann= 3
  2141.7      .1 4831.61    .015  5159.4      .1
BR D #Sta/Elev= 161
  2141.7   40.94  2266.7   39.74  2331.7   39.34  2436.7   40.44  2451.7   41.04
  2496.7   39.44  2521.7   38.84  2541.7   39.24  2781.7   38.94  2801.7   38.14
  2861.7   38.84  3131.7   40.24  3146.7   39.94  3201.7   40.24  3236.7   39.54
  3316.7   39.54  3449.9   40.24  3539.9   39.64  3554.9   39.14  3569.9   37.94
  3614.9   39.34  3667.7   39.34  3683.6   39.34  3843.6   38.24  3858.6   37.64
  3868.6   36.94  3888.6   36.74  3913.6   36.88  3993.6   37.34  4038.6   36.44
  4337.7   35.94  4457.7   34.44  4472.7   33.74  4492.7   34.04  4502.7   33.74
  4512.7   34.14  4517.7   34.54  4520.4   34.64  4612.8   35.31 4708.92   36.01
  4810.4   36.74  4825.4    36.9 4857.78   36.31    4926   13.58    4943   13.58
    4970    4.58  4986.9    4.24    4998    1.74    5000    1.74    5002    1.74
  5013.1    4.24    5030    4.58    5057   13.58    5074   13.58 5145.75   37.49
  5159.4   34.74  5253.6   34.04  5323.6   33.94  5338.6   33.04  5348.6   32.34
  5398.6   32.64  5428.6   32.14  5443.6   32.44  5458.6   33.64  5473.6   34.04
 5520.88   34.37  5559.6   34.64  5639.6   34.94  5669.6   34.24  5684.6   33.14
  5699.6   32.74  5714.6   32.94  5722.3   33.27  5754.6   34.64  5787.3   34.79
  5839.6   35.04  5869.6   35.94  5914.6   35.44  5953.4   33.64  5978.4   32.94
  5998.4   33.54  6018.4   34.94  6097.3   35.89  6102.3   35.95  6112.3   36.07
  6118.4   36.14  6127.3   36.14  6127.8   36.14  6162.8   36.14  6163.4   36.14
  6278.4   36.94  6328.4   36.74  6363.4   37.64  6535.9   37.74  6577.8   37.43
  6587.8   37.35  6597.8   37.28  6615.9   37.14  6634.1   37.25  6695.9   37.64
  6745.9   37.14  6775.9   38.14  6809.1   38.26  6861.7   38.44  6946.7   38.44
  6956.7   38.04  7095.5   38.42  7141.7   38.54  7285.8   39.54  7365.8   39.84
  7470.8   38.84  7560.8   38.94  7758.7   40.74  7788.7   41.14  7923.7   40.94
  7953.7   39.74  8043.7   40.04  8073.7   39.04  8118.7   39.84  8188.7   40.04
  8193.7   40.34  8313.7   40.64  8343.7   41.14  8373.7   40.94  8553.7   41.04
  8628.7   41.64  8658.7   41.14  8723.7   42.14  8778.7   42.34  8823.7   41.74
  8898.7   41.34  8933.7   39.74  8948.7   39.54  8958.7   39.74  8978.7   40.84
  9123.7   41.54  9183.7   40.64  9218.7   39.14  9228.7   38.94  9273.7   41.04
  9453.7   41.34  9498.7   39.74  9513.7   39.74  9558.7   41.24  9738.7   41.54
  9758.7   40.94  9768.7   40.24  9798.7   40.04  9843.7   41.54  9933.7   42.34
 10038.7   41.24 10053.7   40.34 10068.7   40.04 10083.7   40.24 10098.7   41.24
 10128.7   41.94 10208.7   41.14 10233.7   40.44 10253.7   40.74 10308.7   42.34
 10454.5   42.44
BR D #Mann= 3
  2141.7      .1  4825.4    .015 5145.75      .1
BC Design=,, 0 ,, 0 ,,,,,,
BC HTab HWMax=42.51
BC Use User HTab Curves=0
BC User HTab FreeFlow(D)= 0

Type RM Length L Ch R = 1 ,48062.3 ,837.99,882.73,938.45
BEGIN DESCRIPTION:
Downstream Section of Bridge/Culvert/Weir
USACE Sims Bayou Rectification
Reach 5 Mykawa to Downstream of Cullen
File No. HSC 409-15
END DESCRIPTION:
XS GIS Cut Line= 6
      3131851.57     13803227.46      3131742.73     13801458.91
      3131910.46     13799661.84       3131820.6     13799266.49
      3131135.35      13797704.6      3131080.27     13795088.51
#Sta/Elev= 30
  2141.7   40.94  2801.7   38.14  3449.9   40.24  4472.7   33.74  4825.4    36.9
 4857.78   36.31    4926   13.58    4943   13.58    4970    4.58    4998   1.742
    5030    4.58    5057   13.58    5074   13.58 5145.75   37.49  5159.4   34.74
  5428.6   32.14  5869.6   35.94  5978.4   32.94  6363.4   37.64  7788.7   41.14
  8073.7   39.04  8778.7   42.34  8948.7   39.54  9123.7   41.54  9228.7   38.94
  9273.7   41.04  9798.7   40.04  9933.7   42.34 10068.7   40.04 10454.5   42.44
#Mann= 4 ,-1 , 0
  2141.7      .2       0  4825.4    .035       0 5145.75      .2       0
 10454.5      .2       0
#XS Ineff= 2 , 0
       0 4857.78   34.14 5145.75       0   32.77
Permanent Ineff=
       F       F
Bank Sta=4825.4,5145.75
XS Rating Curve= 0 ,0
Exp/Cntr=0.5,0.3