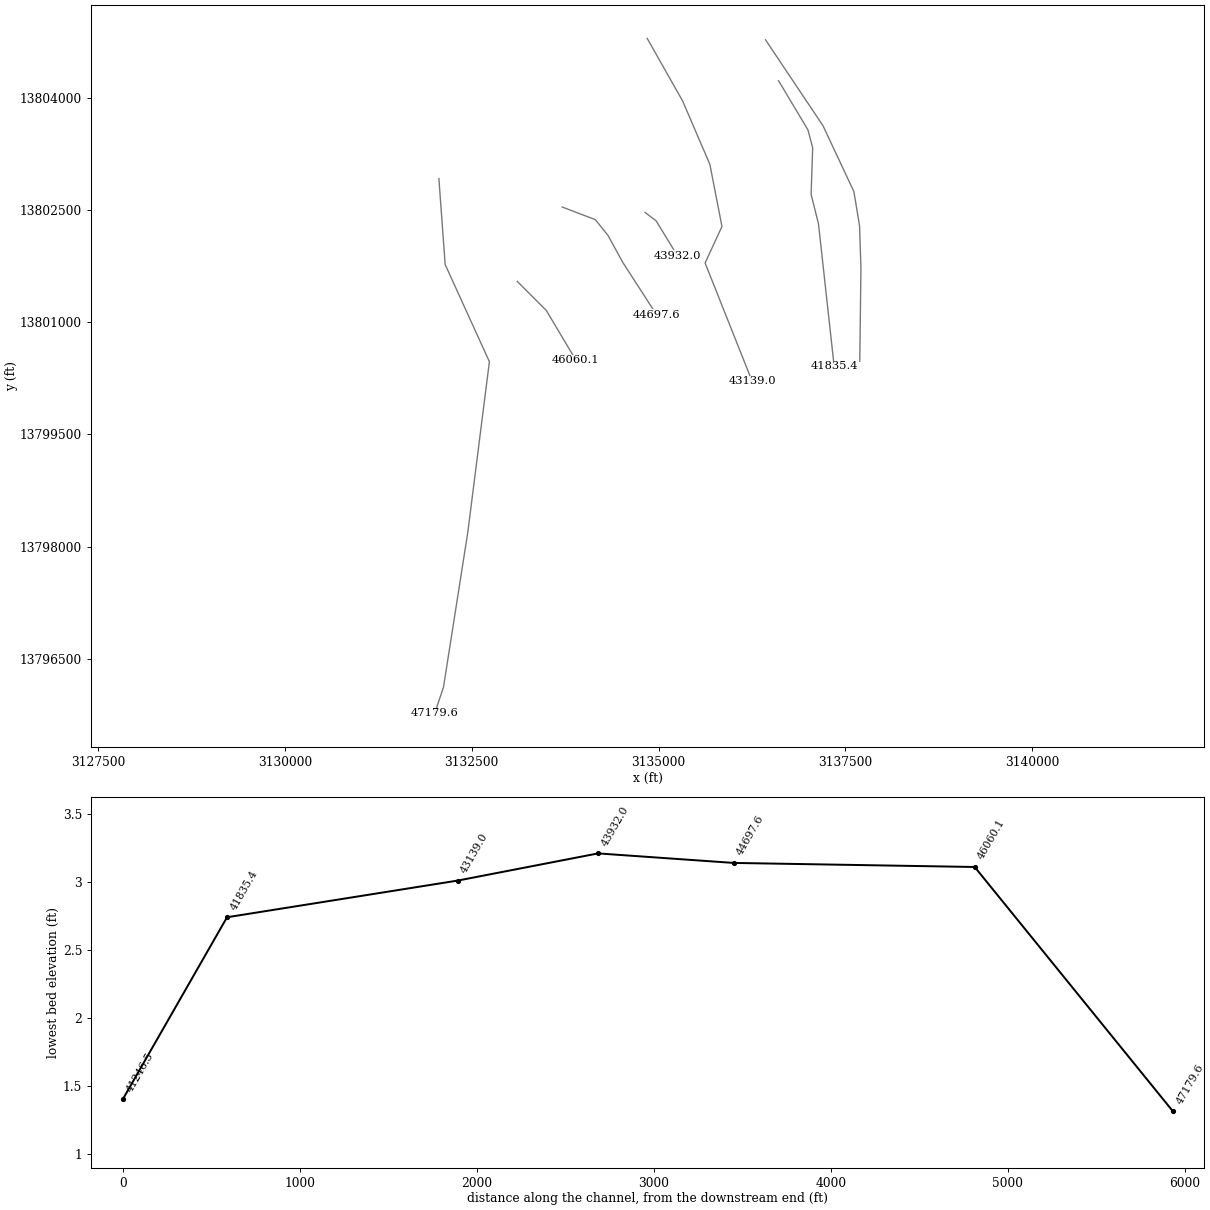
HEC-RAS study C100-00-00.prj: C100-00-00

--- C100-00-00.g01 (geometry) --- (continued)

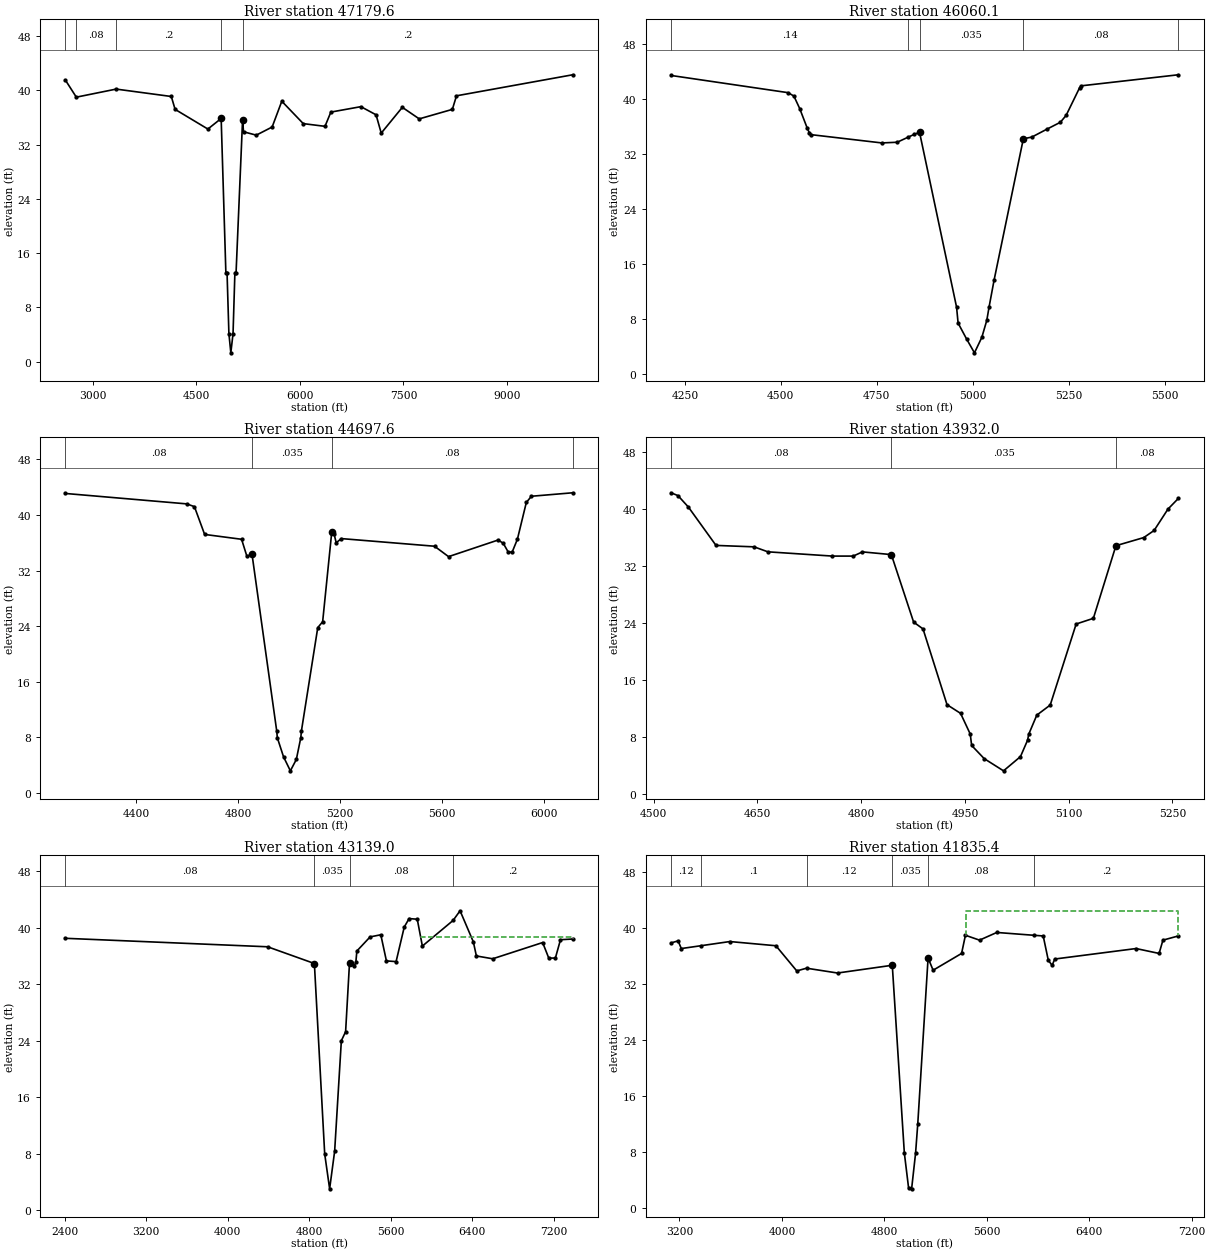
Type RM Length L Ch R = 1 ,47179.6 ,1050.5,1119.5,1092
BEGIN DESCRIPTION:
Cross Section 47179.6
USACE Sims Bayou Rectification
Reach 5 Mykawa to Downstream of Cullen
File No. HSC 409-15
END DESCRIPTION:
XS GIS Cut Line= 6
      3132061.27     13802921.05      3132145.24     13801771.19
      3132736.97     13800472.98      3132447.96     13798191.01
      3132122.87     13796122.58      3132005.04     13795771.84
#Sta/Elev= 30
  2601.3    41.5  2758.6      39  3335.9   40.19  4135.3    39.1  4190.3    37.2
  4665.3    34.3 4857.88   35.86    4926   13.15    4943   13.15    4970    4.15
    4998   1.312    5030    4.15    5057   13.15    5074   13.15  5168.2   35.66
  5181.7    33.9  5366.7    33.4  5596.7    34.6  5736.7    38.4  6047.8    35.1
  6362.8    34.7  6447.8    36.8  6882.8    37.6  7102.8    36.4  7177.8    33.7
  7483.6    37.5  7728.6    35.8  8208.6    37.2  8268.6    39.2    9953    42.3
#Mann= 5 ,-1 , 0
  2601.3      .1       0  2758.6     .08       0  3335.9      .2       0
 4857.88    .035       0  5168.2      .2       0
Bank Sta=4857.88,5168.2
XS Rating Curve= 0 ,0
Exp/Cntr=0.3,0.1

Type RM Length L Ch R = 1 ,46060.1 ,1338.5,1362.5,1322.8
BEGIN DESCRIPTION:
Cross Section 46060.1
END DESCRIPTION:
XS GIS Cut Line= 3
      3133110.67     13801545.41      3133498.82     13801157.25
      3133894.04     13800493.86
#Sta/Elev= 28
    4214    43.4    4519    40.9    4534    40.4    4549    38.6    4569    35.7
    4574    35.1    4579    34.8  4762.9    33.6  4802.9    33.7  4831.9   34.45
  4847.2   34.84  4861.1   35.16  4957.6    9.75  4961.6    7.43  4983.8    5.11
  5004.2    3.11  5023.4    5.36  5036.3    7.83  5042.5    9.84  5055.4    13.7
  5131.5    34.2  5153.6   34.45  5192.9    35.6  5227.9    36.6  5242.9    37.6
  5277.9    41.6  5282.9    41.9  5535.1    43.5
#Mann= 5 ,-1 , 0
    4214     .14       0  4831.9     .08       0  4861.1    .035       0
  5131.5     .08       0  5535.1      .2       0
Bank Sta=4861.1,5131.5
XS Rating Curve= 0 ,0
Exp/Cntr=0.3,0.1

Type RM Length L Ch R = 1 ,44697.6 ,728.2,765.6,756.2
BEGIN DESCRIPTION:
Cross Section 44697.6
END DESCRIPTION:
XS GIS Cut Line= 5
      3133710.54      13802540.5      3134155.16     13802371.12
      3134324.54      13802159.4      3134522.14     13801799.47
      3134973.81     13801100.79
#Sta/Elev= 30
  4122.9    43.1  4598.7    41.6  4628.7    41.2  4668.7    37.2  4813.7    36.5
  4834.5   34.05  4854.6   34.34  4951.5    8.87  4953.9     7.9  4978.2    5.16
    5005    3.14  5028.4    4.78  5045.9    7.92  5048.5    8.92  5112.4   23.77
  5131.6   24.62  5167.3   37.55  5176.3   37.28  5184.8      36  5204.8    36.6
  5570.4    35.5  5625.4      34  5820.4    36.4  5840.4    35.9  5860.4    34.6
  5875.4    34.7  5895.4    36.5  5930.4    41.8  5950.4    42.7  6112.4    43.2
#Mann= 4 ,-1 , 0
  4122.9     .08       0  4854.6    .035       0  5167.3     .08       0
  6112.4      .2       0
Bank Sta=4854.6,5167.3
XS Rating Curve= 0 ,0
Exp/Cntr=0.3,0.1

Type RM Length L Ch R = 1 ,43932.0 ,875.1,793,711.4
BEGIN DESCRIPTION:
Cross Section 43932.0
END DESCRIPTION:
XS GIS Cut Line= 3
      3134820.04     13802467.05      3134966.76     13802357.01
      3135253.94     13801887.94
#Sta/Elev= 30
  4525.1    42.3  4535.1    41.9  4550.1    40.3  4590.1    34.9  4645.1    34.7
  4665.1      34  4758.5    33.4  4788.5    33.4  4801.8   33.99  4843.6   33.61
  4875.8   24.12  4889.4   23.16  4924.1   12.51  4943.7   11.29  4957.7    8.38
  4959.7    6.78  4977.8    4.93  5005.8    3.21  5030.3    5.21  5040.5     7.5
  5042.3    8.37  5053.9   11.04  5073.3   12.46  5110.8   23.85  5135.7   24.65
  5168.3   34.86  5208.5      36  5223.5      37  5243.5      40  5258.5    41.5
#Mann= 3 , 1 , 0
  4525.1     .08       0  4843.6    .035       0  5168.3     .08       0
Bank Sta=4843.6,5168.3
XS Rating Curve= 0 ,0
Exp/Cntr=0.3,0.1

Type RM Length L Ch R = 1 ,43139.0 ,1257,1303.6,1295.6
BEGIN DESCRIPTION:
Cross Section 43139.0
END DESCRIPTION:
XS GIS Cut Line= 6
      3134847.97     13804795.06      3135322.17     13803958.16
      3135686.61     13803112.15      3135848.93     13802279.38
      3135623.09     13801792.42      3136253.65     13800208.38
#Sta/Elev= 30
  2408.5    38.5  4391.5    37.3  4850.5   34.93  4951.7    7.96  5000.1    3.01
  5049.4    8.35    5115   23.99  5156.9   25.27  5195.1   35.02  5242.3    34.6
  5257.3    35.1  5267.3    36.7  5397.2    38.7  5502.2      39  5557.2    35.3
  5652.2    35.2  5732.2    40.1  5779.9    41.3  5859.9    41.2  5909.9    37.4
  6211.2   41.03  6279.9    42.4  6409.9      38  6439.9      36  6599.9    35.6
  7089.9    37.9  7149.9    35.7  7214.9    35.7  7264.9    38.3  7384.9    38.4
#Mann= 4 , 1 , 0
  2408.5     .08       0  4850.5    .035       0  5195.1     .08       0
  6211.2      .2       0
#XS Ineff= 2 , 0
       0                    5890       0   38.64
Permanent Ineff=
       F       F
Bank Sta=4850.5,5195.1
XS Rating Curve= 0 ,0
Exp/Cntr=0.3,0.1

Type RM Length L Ch R = 1 ,41835.4 ,542.4,588.9,585.2
BEGIN DESCRIPTION:
Cross Section 41835.4
END DESCRIPTION:
XS GIS Cut Line= 6
      3136605.79     13804228.78      3136999.28     13803570.88
       3137062.8     13803330.92      3137041.63     13802709.88
      3137140.43     13802314.66      3137350.35     13800409.05
#Sta/Elev= 30
  3134.2    37.9  3189.2    38.2  3214.2    37.1  3370.3   37.51  3593.1    38.1
  3953.1    37.5    4116    33.9    4192   34.29  4434.3    33.6  4861.8   34.71
    4956    7.86  4989.5    2.81  5012.8    2.74  5043.6    7.82  5060.9   12.06
  5141.4   35.75  5180.7      34    5403    36.4    5433      39    5543    38.3
    5678    39.4  5971.6   38.99  6040.4    38.9  6080.4    35.4  6110.4    34.7
  6130.4    35.6  6765.4    37.1  6945.4    36.4  6975.4    38.3  7095.4    38.9
#Mann= 6 , 1 , 0
  3134.2     .12       0  3370.3      .1       0    4192     .12       0
  4861.8    .035       0  5141.4     .08       0  5971.6      .2       0
#XS Ineff= 2 , 0
       0                    5439       0    42.5
Permanent Ineff=
       F       F
Bank Sta=4861.8,5141.4
XS Rating Curve= 0 ,0
Exp/Cntr=0.3,0.1

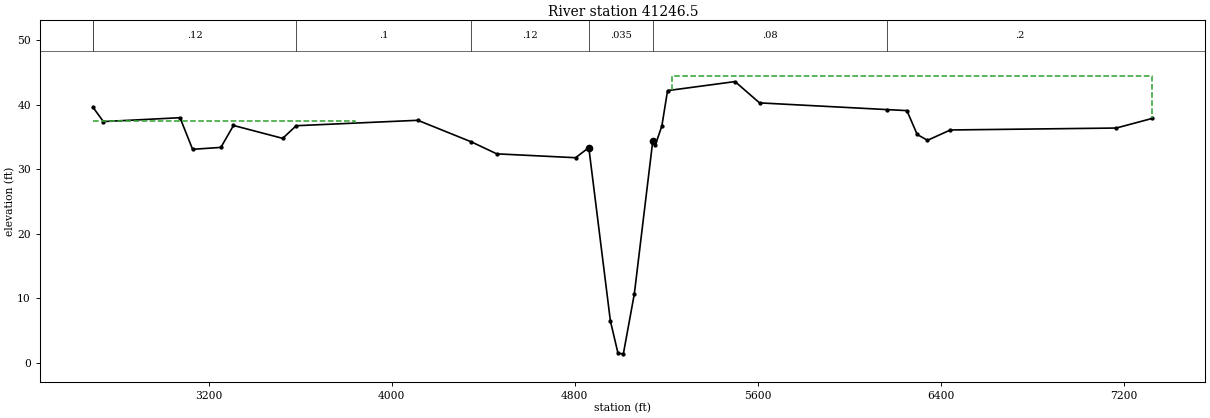
Type RM Length L Ch R = 1 ,41246.5 ,509.6,591.5,658.7
BEGIN DESCRIPTION:
Cross Section 41246.5- Interpolated
END DESCRIPTION:
XS GIS Cut Line= 6
      3136430.99     13804776.03      3137201.39     13803625.85
      3137613.72     13802746.95      3137689.67     13802291.22
      3137708.47     13801727.44      3137692.67     13800479.35
#Sta/Elev= 30
  2695.1    39.6  2740.1    37.4  3075.1      38  3130.1    33.1  3253.8    33.4
  3308.8    36.8  3523.8    34.8    3583   36.76  4114.5    37.6  4348.1   34.26
  4459.5    32.4  4804.1    31.8  4861.8   33.37    4956    6.52  4989.5    1.47
  5012.8     1.4  5060.9   10.72  5141.4   34.41  5152.7   33.79    5181    36.7
    5206    42.2    5501    43.6    5608    40.3  6164.4   39.26  6252.1    39.1
  6297.1    35.4  6342.1    34.5  6442.1    36.1  7167.1    36.4  7325.3    37.9
#Mann= 7 , 1 , 0
  2695.1      .2       0  2695.1     .12       0    3583      .1       0
  4348.1     .12       0  4861.8    .035       0  5141.4     .08       0
  6164.4      .2       0
#XS Ineff= 2 , 0
       0    3840    37.5    5226       0    44.5
Permanent Ineff=
       F       F
Bank Sta=4861.8,5141.4
XS Rating Curve= 0 ,0
Exp/Cntr=0.3,0.1