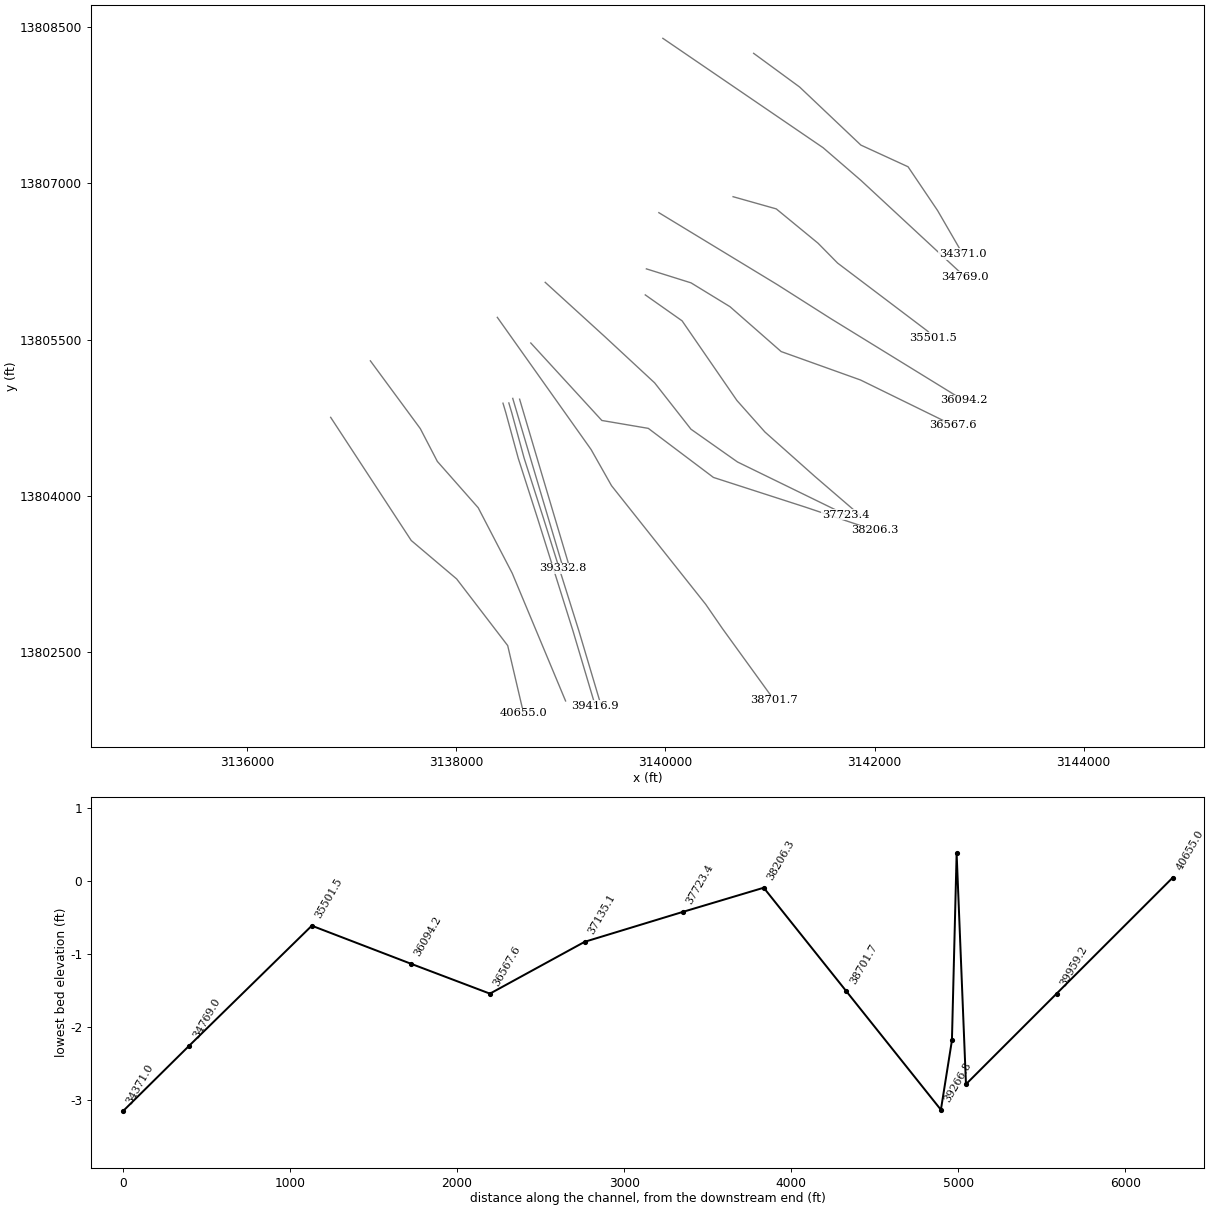
HEC-RAS study C100-00-00.prj: C100-00-00

--- C100-00-00.g01 (geometry) --- (continued)

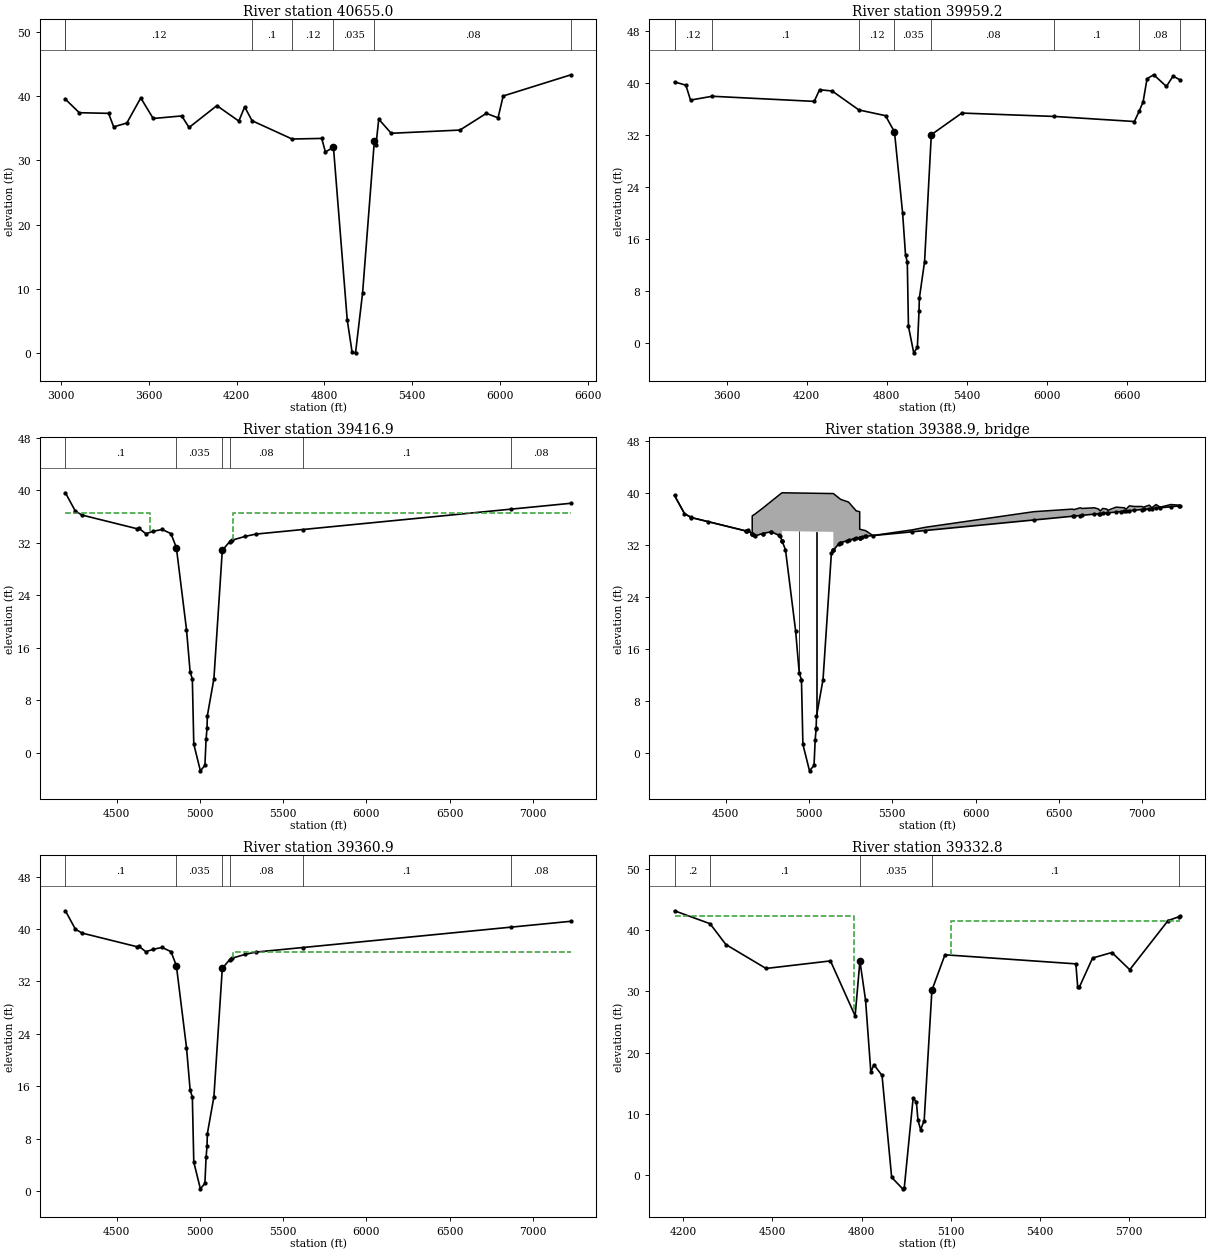
Type RM Length L Ch R = 1 ,40655.0 ,730.9,695.8,632.6
BEGIN DESCRIPTION:
Cross Section 40655.0-Interpolated
END DESCRIPTION:
XS GIS Cut Line= 5
      3136799.92     13804754.32      3137570.32      13803571.6
      3138004.34     13803202.68      3138492.63     13802562.48
      3138644.54     13801911.44
#Sta/Elev= 30
  3030.2    39.5  3125.2    37.4  3325.2    37.3  3360.2    35.2  3450.2    35.8
  3545.2    39.7  3630.2    36.5  3825.2    36.9  3875.2    35.1  4065.2    38.5
  4215.2    36.1  4255.2    38.3  4305.9   36.15  4579.3   33.31  4781.7    33.4
  4806.7    31.3  4861.8   32.02    4956    5.17  4989.5     .12  5012.8     .05
  5060.9    9.37  5141.4   33.06  5152.7   32.44  5171.3    36.4  5256.3    34.2
  5726.3    34.7  5906.5    37.3  5986.5    36.6  6021.5      40    6485    43.3
#Mann= 7 , 1 , 0
  3030.2      .2       0  3030.2     .12       0  4305.9      .1       0
  4579.3     .12       0  4861.8    .035       0  5141.4     .08       0
    6485      .2       0
Bank Sta=4861.8,5141.4
XS Rating Curve= 0 ,0
Exp/Cntr=0.3,0.1

Type RM Length L Ch R = 1 ,39959.2 ,576.5,542.3,486.9
BEGIN DESCRIPTION:
Cross Section 39959.2-Interpolated
END DESCRIPTION:
XS GIS Cut Line= 6
      3137179.69     13805296.86      3137657.12     13804645.82
      3137819.88     13804331.15      3138210.51     13803886.27
      3138536.03     13803256.93      3139046.01      13802030.8
#Sta/Elev= 30
  3209.5    40.2  3294.5    39.7  3329.5    37.4  3491.9   37.99  4256.8    37.2
  4296.8      39  4391.1    38.8  4591.7   35.88  4791.1      35  4858.5   32.49
  4919.3   20.01  4941.3   13.49  4954.4   12.48  4963.1    2.54  5002.7   -1.54
  5029.9    -.71  5042.4    4.92  5044.7    6.87    5084   12.51  5134.4   32.07
  5363.1    35.4  6057.4   34.88  6656.7    34.1  6694.6   35.79  6721.7    37.1
  6751.7    40.7  6801.7    41.3  6896.7    39.5  6946.7    41.1  6999.6    40.5
#Mann= 9 , 1 , 0
  3209.5      .2       0  3209.5     .12       0  3491.9      .1       0
  4591.7     .12       0  4858.5    .035       0  5134.4     .08       0
  6057.4      .1       0  6694.6     .08       0  6999.6      .2       0
Bank Sta=4858.5,5134.4
XS Rating Curve= 0 ,0
Exp/Cntr=0.5,0.3

Type RM Length L Ch R = 1 ,39416.9 ,56,56,56
BEGIN DESCRIPTION:
Upstream Section of Bridge/Culvert/Weir
END DESCRIPTION:
XS GIS Cut Line= 6
      3138447.61     13804890.38      3138475.26     13804797.05
      3138593.77     13804360.56      3138778.78     13803782.42
      3139116.88     13802703.06      3139329.96     13801983.99
#Sta/Elev= 29
  4191.7   39.62  4251.7   36.82  4291.7   36.22  4620.5   34.15  4631.7   34.24
    4675   33.38  4720.6   33.75  4772.5   34.03  4826.1   33.39  4858.5   31.25
  4919.3   18.77  4941.3   12.25  4954.4   11.24  4963.1     1.3  5002.7   -2.78
  5029.9   -1.95  5036.9       2  5042.4    3.68  5044.7    5.63    5084   11.27
  5134.4   30.83  5178.4   32.16  5183.8   32.32  5190.3   32.37  5272.1   32.97
  5335.7   33.32  5619.3   34.02  6871.2   37.13  7229.4   38.02
#Mann= 6 , 1 , 0
  4191.7      .1       0  4858.5    .035       0  5134.4      .1       0
  5178.4     .08       0  5619.3      .1       0  6871.2     .08       0
#XS Ineff= 2 , 0
       0    4700    36.5    5200       0    36.5
Permanent Ineff=
       F       F
Bank Sta=4858.5,5134.4
XS Rating Curve= 0 ,0
Exp/Cntr=0.5,0.3

Type RM Length L Ch R = 3 ,39388.9 ,,,
BEGIN DESCRIPTION:
MYKAWA ROAD
Structure ID: C00-24
END DESCRIPTION:
Bridge Culvert--1,0,-1,-1, 0
Deck Dist Width WeirC Skew NumUp NumDn MinLoCord MaxHiCord MaxSubmerge Is_Ogee
10,36,2.6,0, 52, 51, , , 0.95, 0, 1,1,,
  4191.7  4251.7  4291.7  4620.5  4631.7 4658.49  4658.6    4675  4720.6  4772.5
  4826.1  4837.5 4837.61  4837.7 5145.89    5146  5146.1  5183.8  5190.3  5237.4
  5283.3  5304.3 5304.41  5339.8  5383.3  5619.3  5698.3  6350.4  6584.4  6589.4
  6629.4  6639.4  6714.4  6739.4  6749.4  6764.4  6789.4  6794.4  6844.4  6894.4
  6904.4  6924.4  6954.4  6999.4  7009.4  7044.4  7059.4  7084.4  7109.4  7174.4
  7224.4  7229.4
    39.6    36.8   36.21   34.14   34.23   33.75   36.45   36.73   37.62   38.69
   39.79   40.01   40.01   40.01   39.89   39.89   39.89   39.12   38.99   38.58
   37.23    37.1    34.4   34.18   33.43    34.3    34.7    37.1    37.5    37.4
    37.7    37.6    37.7    37.5    37.2    37.6    37.5    37.3    37.8    37.7
    37.5      38    37.9    37.9    37.8    38.1    37.7    38.2    37.8    38.2
    38.1      38
    39.6    36.8    36.2   34.13   34.22   33.69   33.69   33.36   33.73   34.01
   33.37   32.62   32.61   34.11   33.99   31.16   31.16    32.3   32.35   32.68
   33.01   33.11   33.11   33.31   33.42      34    34.2   35.82    36.4   36.41
   36.51   36.54   36.72   36.78   36.81   36.85   36.91   36.92   37.04   37.17
   37.19   37.24   37.32   37.43   37.45   37.54   37.58   37.64    37.7   37.86
   37.99      38
  4191.7  4251.7  4291.7  4620.5  4631.7 4658.49  4658.6    4675  4720.6  4772.5
  4826.1  4837.5 4837.61  4837.7 5145.89    5146  5146.1  5183.8  5190.3  5237.4
  5283.3  5304.3 5304.41  5339.8  5383.3  5619.3  5698.3  6350.4  6584.4  6589.4
  6629.4  6639.4  6714.4  6739.4  6749.4  6764.4  6789.4  6794.4  6844.4  6894.4
  6904.4  6924.4  6954.4  6999.4  7009.4  7044.4  7059.4  7084.4  7109.4  7174.4
  7229.4
   39.68   36.88   36.28   34.21    34.3   33.77   36.45   36.73   37.62   38.69
   39.79   40.01   40.01   40.01   39.89   39.89   39.89   39.12   38.99   38.58
   37.23    37.1    34.4   34.18    33.5    34.3    34.7    37.1    37.5    37.4
    37.7    37.6    37.7    37.5    37.2    37.6    37.5    37.3    37.8    37.7
    37.5      38    37.9    37.9    37.8    38.1    37.7    38.2    37.8    38.2
   38.08
   39.68   36.88   36.28   34.21    34.3   33.77   33.77   33.44   33.81   34.09
   33.45    32.7   32.69   34.19   34.07   31.24   31.24   32.38   32.43   32.76
   33.09   33.19   33.19   33.39    33.5   34.08   34.28    35.9   36.48   36.49
   36.59   36.62    36.8   36.86   36.89   36.93   36.99      37   37.12   37.25
   37.27   37.32    37.4   37.51   37.53   37.62   37.66   37.72   37.78   37.94
   38.08
Pier Skew, UpSta & Num, DnSta & Num=  ,4941.3, 2 ,4941.3, 2 , 0 , 0 , 0 ,,
       2       2
   11.15   35.07
       2       2
   11.23   35.15
Pier Skew, UpSta & Num, DnSta & Num=  ,5044.7, 2 ,5044.7, 2 , 0 , 0 , 0 ,,
       2       2
    3.76   35.03
       2       2
    3.84   35.11
Abutment Skew #Up #Dn= , 2 , 2
  4837.5  4954.4
   34.11   11.22
  4837.5  4954.4
   34.19    11.3
Abutment Skew #Up #Dn= , 2 , 2
  5042.5 5146.09
    3.74   33.99
  5042.5 5146.09
    3.82   34.07
BR Coef= 1 , 1 , 0 ,1.25, 0 ,,,0.8,0,2,0,
WSPro=,,,, 1 ,,,, 0 ,,,, 0 ,,,,-1 ,-1 ,-1 , 0 , 0 , 0 , 0 , 0
BR U #Sta/Elev= 82
  4191.7    39.6  4251.7    36.8    4289   36.24  4291.7    36.2    4394   35.56
  4620.5   34.13    4624   34.16  4626.7   34.18  4631.7   34.22 4658.49   33.69
  4658.6   33.69 4658.71   33.68  4670.8   33.44    4675   33.36  4720.6   33.73
    4723   33.74  4770.8      34  4772.5   34.01  4818.9   33.46  4826.1   33.37
  4837.5   32.62 4837.61   32.61  4837.7    32.6  4858.5   31.23  4919.3   18.75
  4941.3   12.23  4954.3   11.23  4954.4   11.22  4963.1    1.28  5002.7    -2.8
  5029.9   -1.97  5036.9    1.98  5042.4    3.66  5042.5    3.74  5044.7    5.61
    5084   11.25  5134.4   30.81 5145.89   31.16    5146   31.16  5146.1   31.16
  5178.4   32.14  5183.8    32.3  5190.3   32.35  5225.1   32.59  5237.4   32.68
  5272.1   32.95  5283.3   33.01 5304.19   33.11  5304.3   33.11 5304.41   33.11
    5316   33.17  5335.7    33.3  5339.8   33.31  5383.3   33.42  5619.3      34
  5698.3    34.2  6350.4   35.82  6584.4    36.4  6589.4   36.41  6629.4   36.51
  6639.4   36.54  6714.4   36.72  6739.4   36.78  6749.4   36.81  6764.4   36.85
  6789.4   36.91  6794.4   36.92  6844.4   37.04  6871.2   37.11  6894.4   37.17
  6904.4   37.19  6924.4   37.24  6954.4   37.32  6999.4   37.43  7009.4   37.45
  7044.4   37.54  7059.4   37.58  7084.4   37.64  7109.4    37.7  7174.4   37.86
  7224.4   37.99  7229.4      38
BR U #Mann= 6
  4191.7      .1  4858.5    .035  5134.4      .1  5178.4     .08  5619.3      .1
  6871.2     .08
BR U Banks=4858.5,5134.4
BR D #Sta/Elev= 82
  4191.7   39.68  4251.7   36.88    4289   36.32  4291.7   36.28    4394   35.64
  4620.5   34.21    4624   34.24  4626.7   34.26  4631.7    34.3 4658.49   33.77
  4658.6   33.77 4658.71   33.76  4670.8   33.52    4675   33.44  4720.6   33.81
    4723   33.82  4770.8   34.08  4772.5   34.09  4818.9   33.54  4826.1   33.45
  4837.5    32.7 4837.61   32.69  4837.7   32.68  4858.5   31.31  4919.3   18.83
  4941.3   12.31  4954.3   11.31  4954.4    11.3  4963.1    1.36  5002.7   -2.72
  5029.9   -1.89  5036.9    2.06  5042.4    3.74  5042.5    3.82  5044.7    5.69
    5084   11.33  5134.4   30.89 5145.89   31.24    5146   31.24  5146.1   31.24
  5178.4   32.22  5183.8   32.38  5190.3   32.43  5225.1   32.67  5237.4   32.76
  5272.1   33.03  5283.3   33.09 5304.19   33.19  5304.3   33.19 5304.41   33.19
    5316   33.25  5335.7   33.38  5339.8   33.39  5383.3    33.5  5619.3   34.08
  5698.3   34.28  6350.4    35.9  6584.4   36.48  6589.4   36.49  6629.4   36.59
  6639.4   36.62  6714.4    36.8  6739.4   36.86  6749.4   36.89  6764.4   36.93
  6789.4   36.99  6794.4      37  6844.4   37.12  6871.2   37.19  6894.4   37.25
  6904.4   37.27  6924.4   37.32  6954.4    37.4  6999.4   37.51  7009.4   37.53
  7044.4   37.62  7059.4   37.66  7084.4   37.72  7109.4   37.78  7174.4   37.94
  7224.4   38.07  7229.4   38.08
BR D #Mann= 6
  4191.7      .1  4858.5    .035  5134.4      .1  5178.4     .08  5619.3      .1
  6871.2     .08
BR D Banks=4858.5,5134.4
BC Design=,, 0 ,, 0 ,,,,,,
BC HTab HWMax=39.62
BC Use User HTab Curves=0
BC User HTab FreeFlow(D)= 0

Type RM Length L Ch R = 1 ,39360.9 ,28.1,28.1,28.1
BEGIN DESCRIPTION:
Downstream Section of Bridge/Culvert/Weir
END DESCRIPTION:
XS GIS Cut Line= 6
      3138503.57     13804892.52      3138531.22     13804799.19
      3138649.73      13804362.7      3138834.74     13803784.56
      3139172.84      13802705.2      3139385.92     13801986.13
#Sta/Elev= 29
  4191.7   42.78  4251.7   39.98  4291.7   39.38  4620.5   37.31  4631.7    37.4
    4675   36.54  4720.6   36.91  4772.5   37.19  4826.1   36.55  4858.5   34.41
  4919.3   21.93  4941.3   15.41  4954.4    14.4  4963.1    4.46  5002.7     .38
  5029.9    1.21  5036.9    5.16  5042.4    6.84  5044.7    8.79    5084   14.43
  5134.4   33.99  5178.4   35.32  5183.8   35.48  5190.3   35.53  5272.1   36.13
  5335.7   36.48  5619.3   37.18  6871.2   40.29  7229.4   41.18
#Mann= 6 , 1 , 0
  4191.7      .1       0  4858.5    .035       0  5134.4      .1       0
  5178.4     .08       0  5619.3      .1       0  6871.2     .08       0
#XS Ineff= 2 , 0
       0    4700    36.5    5200       0    36.5
Permanent Ineff=
       F       F
Bank Sta=4858.5,5134.4
XS Rating Curve= 0 ,0
Exp/Cntr=0.5,0.3

Type RM Length L Ch R = 1 ,39332.8 ,66,66,66
BEGIN DESCRIPTION:
Upstream Section of Bridge/Culvert/Weir
END DESCRIPTION:
XS GIS Cut Line= 4
      3138540.93      13804936.2      3138753.73       13804215.
      3138869.36     13803824.76      3139023.45     13803306.12
#Sta/Elev= 30
    4171   43.13  4290.6   41.02  4343.7   37.63  4478.7   33.73  4695.4   34.96
  4778.3      26  4794.4   34.95  4813.4   28.53  4831.1   16.83  4841.3   18.05
  4868.7    16.3  4901.1    -.31  4938.1   -2.18  4943.5   -2.02  4973.4   12.65
  4984.3   11.92  4989.6    9.01  4998.4    7.46  5010.4    8.94  5036.4   30.18
  5080.3   35.96  5520.4   34.48  5526.6   30.73  5531.6   30.63  5576.6   35.43
  5641.6   36.33  5701.6   33.53  5830.4   41.53  5866.2   42.15    5871   42.23
#Mann= 5 , 1 , 0
    4171      .2       0  4290.6      .1       0  4794.4    .035       0
  5036.4      .1       0  5866.2      .2       0
#XS Ineff= 2 , 0
       0    4773   42.24    5102       0    41.5
Permanent Ineff=
       F       F
Bank Sta=4794.4,5036.4
XS Rating Curve= 0 ,0
Exp/Cntr=0.5,0.3

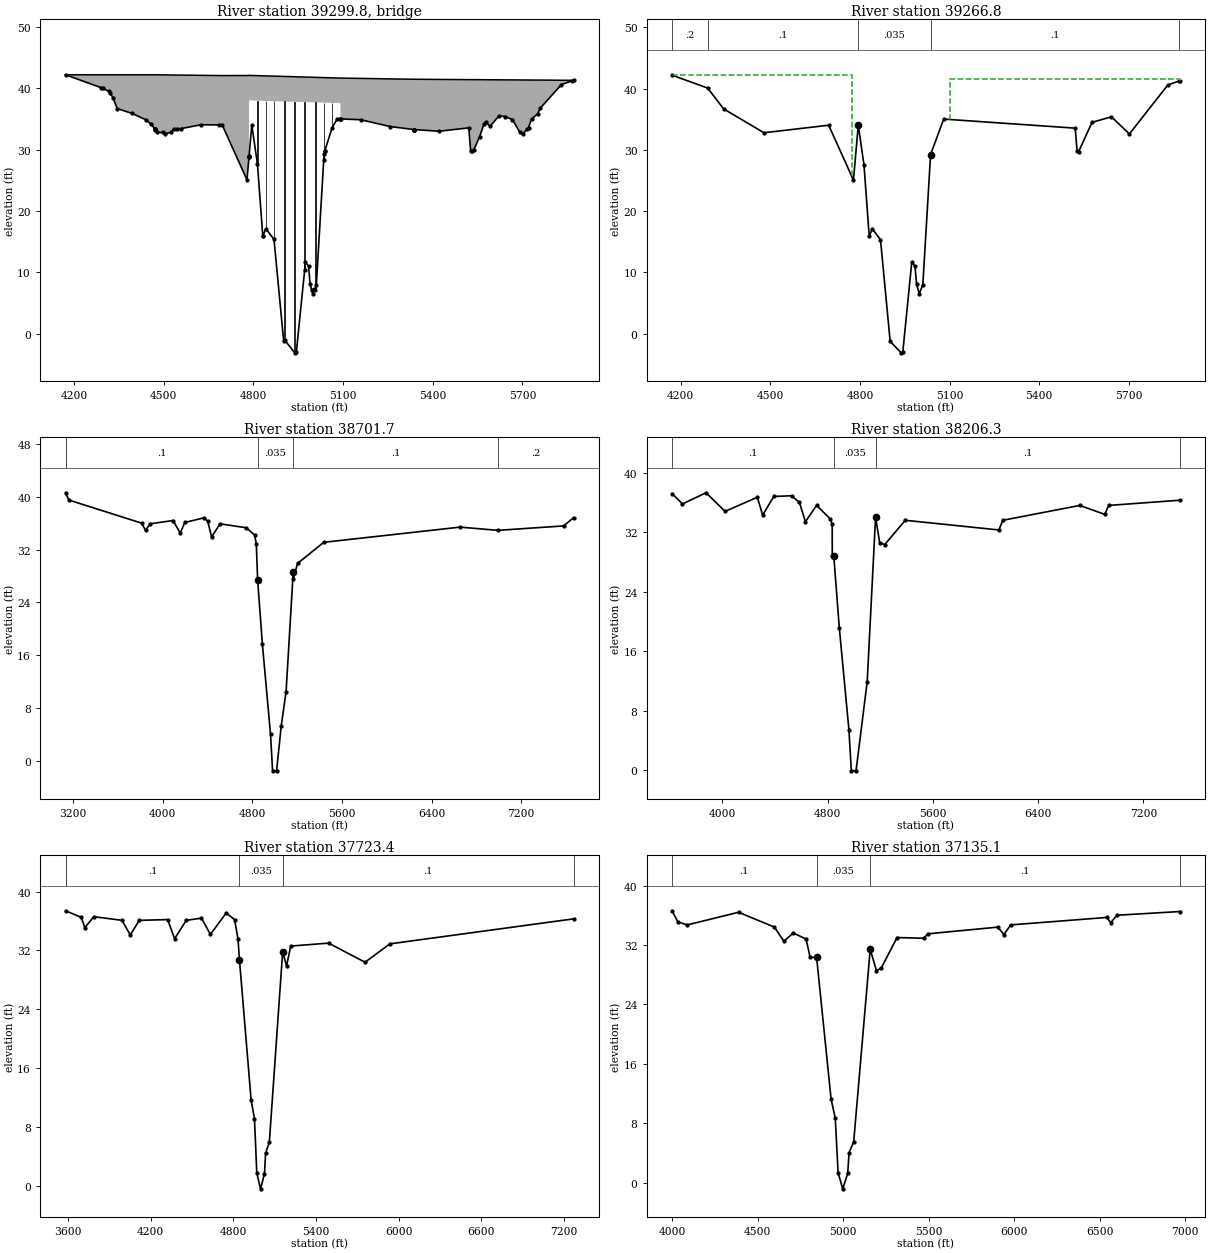
Type RM Length L Ch R = 3 ,39299.8 ,,,
BEGIN DESCRIPTION:
RAILROAD EAST OF MYKAWA
Structure ID: C00-23
END DESCRIPTION:
Bridge Culvert--1,0,-1,-1, 0
Deck Dist Width WeirC Skew NumUp NumDn MinLoCord MaxHiCord MaxSubmerge Is_Ogee
10,46,2.6,0, 47, 47, , , 0.95, 0, 1,1,,
    4171  4295.6  4315.6  4320.6  4330.6  4343.7  4393.7  4438.7  4458.7  4478.7
  4498.7  4503.7  4523.7  4533.7  4555.8  4623.4  4695.4  4778.3 4785.11  4785.2
  4785.3 5090.99  5091.1  5159.3  5257.7 5338.29  5421.2  5520.4  5526.6  5531.6
  5536.6  5556.6  5571.6  5576.6  5591.6  5621.6  5641.6  5666.6  5691.6  5701.6
  5720.4  5730.4  5750.4  5760.4  5830.4  5866.2    5871
    42.2    42.2    42.2    42.2    42.2    42.2    42.2    42.2    42.2    42.2
   42.18   42.18   42.17   42.16   42.15   42.11   42.07   42.08   42.09   42.09
    42.1   41.66   41.66   41.61   41.53   41.47   41.44   41.41   41.41   41.41
   41.41    41.4    41.4   41.39   41.39   41.38   41.37   41.37   41.36   41.35
   41.35   41.34   41.34   41.34   41.31    41.3    41.3
    42.2      40    39.5    39.2    38.4    36.7    35.9    34.9    34.1    32.8
    32.8    32.6    32.8    33.4   33.41   34.05   34.03   25.07   28.86   38.01
   38.02   37.58   35.01   34.87   33.76   33.27      33   33.55    29.8    29.7
    29.9    32.1    34.2    34.5    33.8    35.5    35.4    34.9    32.8    32.6
    33.6      35    35.8    36.8    40.6   41.22    41.3
    4171  4295.6  4315.6  4320.6  4330.6  4343.7  4393.7  4438.7  4458.7  4478.7
  4498.7  4503.7  4523.7  4533.7  4555.8  4623.4  4695.4  4778.3 4785.11  4785.2
  4785.3 5090.99  5091.1  5159.3  5257.7 5338.29  5421.2  5520.4  5526.6  5531.6
  5536.6  5556.6  5571.6  5576.6  5591.6  5621.6  5641.6  5666.6  5691.6  5701.6
  5720.4  5730.4  5750.4  5760.4  5830.4  5866.2    5871
    42.2    42.2    42.2    42.2    42.2    42.2    42.2    42.2    42.2    42.2
   42.18   42.18   42.17   42.16   42.15   42.11   42.07   42.08   42.09   42.09
    42.1   41.66   41.66   41.61   41.53   41.47   41.44   41.41   41.41   41.41
   41.41    41.4    41.4   41.39   41.39   41.38   41.37   41.37   41.36   41.35
   41.35   41.34   41.34   41.34   41.31    41.3    41.3
   42.15   39.95   39.45   39.15   38.35   36.65   35.85   34.85   34.05   32.75
   32.75   32.55   32.75   33.35   33.36      34   33.98   25.02   28.81   37.96
   37.97   37.53   34.96   34.82   33.71   33.22   32.95    33.5   29.75   29.65
   29.85   32.05   34.15   34.45   33.75   35.45   35.35   34.85   32.75   32.55
   33.55   34.95   35.75   36.75   40.55   41.17   41.25
Pier Skew, UpSta & Num, DnSta & Num=  ,4813.4, 2 ,4813.4, 2 , 0 , 0 , 0 ,,
     1.1     1.1
   26.24   38.98
     1.1     1.1
   26.19   38.93
Pier Skew, UpSta & Num, DnSta & Num=  ,4841.3, 2 ,4841.3, 2 , 0 , 0 , 0 ,,
     1.1     1.1
   16.05   38.94
     1.1     1.1
      16   38.89
Pier Skew, UpSta & Num, DnSta & Num=  ,4868.7, 2 ,4868.7, 2 , 0 , 0 , 0 ,,
     1.1     1.1
   14.09    38.9
     1.1     1.1
   14.04   38.85
Pier Skew, UpSta & Num, DnSta & Num=  ,4904.9, 2 ,4904.9, 2 , 0 , 0 , 0 ,,
     4.3     4.3
   -2.18   38.85
     4.3     4.3
   -2.23    38.8
Pier Skew, UpSta & Num, DnSta & Num=  ,4938.1, 2 ,4938.1, 2 , 0 , 0 , 0 ,,
     4.3     4.3
   -4.05    38.8
     4.3     4.3
    -4.1   38.75
Pier Skew, UpSta & Num, DnSta & Num=  ,4971.4, 2 ,4971.4, 2 , 0 , 0 , 0 ,,
     4.3     4.3
    8.42   38.75
     4.3     4.3
    8.37    38.7
Pier Skew, UpSta & Num, DnSta & Num=  ,5007, 2 ,5007, 2 , 0 , 0 , 0 ,,
     1.1     1.1
    6.22    38.7
     1.1     1.1
    6.17   38.65
Pier Skew, UpSta & Num, DnSta & Num=  ,5035, 2 ,5035, 2 , 0 , 0 , 0 ,,
     1.1     1.1
   26.85   38.66
     1.1     1.1
    26.8   38.61
Pier Skew, UpSta & Num, DnSta & Num=  ,5063.1, 2 ,5063.1, 2 , 0 , 0 , 0 ,,
     1.1     1.1
   32.48   38.62
     1.1     1.1
   32.43   38.57
Abutment Skew #Up #Dn= , 2 , 2
    4785  4831.1
   38.01    15.9
    4785  4831.1
   37.96   15.85
Abutment Skew #Up #Dn= , 2 , 2
  5038.2 5091.19
   29.73   37.58
  5038.2 5091.19
   29.68   37.53
BR Coef= 1 , 1 , 0 ,1.25, 0 ,,,0.8,0,2,0,
WSPro=,,,, 1 ,,,, 0 ,,,, 0 ,,,,-1 ,-1 ,-1 , 0 , 0 , 0 , 0 , 0
BR U #Sta/Elev= 86
    4171    42.2  4290.6   40.09  4295.6      40  4315.6    39.5  4320.6    39.2
  4330.6    38.4  4343.7    36.7  4393.7    35.9  4438.7    34.9  4458.7    34.1
    4471    33.3 4471.09   33.29  4471.2   33.29 4471.31   33.28  4478.7    32.8
  4498.7    32.8  4503.7    32.6  4523.7    32.8  4533.7    33.4  4543.7    33.4
  4555.8   33.41  4623.4   34.05  4683.5   34.03  4695.4   34.03  4778.3   25.07
    4785   28.79 4785.11   28.86  4785.2   28.91  4785.3   28.96  4794.4   34.02
  4813.4    27.6    4831   15.97  4831.1    15.9  4841.3   17.12  4868.7   15.37
  4901.1   -1.24  4904.9   -1.05  4938.1   -3.11  4943.5   -2.95  4971.4   10.45
  4973.4   11.72  4984.3   10.99  4989.6    8.08  4994.6    7.13  4998.4    6.53
  5002.4    7.26    5007    7.21  5010.4    8.01    5035    28.3  5036.4   29.25
  5038.1    29.7  5038.2   29.73  5063.1   33.56  5080.3   35.03 5090.99   35.01
  5091.1   35.01  5091.2   35.01  5159.3   34.87  5257.7   33.76  5336.2   33.28
 5338.29   33.27  5338.4   33.27 5338.51   33.27  5338.6   33.27  5421.2      33
  5520.4   33.55  5526.6    29.8  5531.6    29.7  5536.6    29.9  5556.6    32.1
  5571.6    34.2  5576.6    34.5  5591.6    33.8  5621.6    35.5  5641.6    35.4
  5666.6    34.9  5691.6    32.8  5701.6    32.6  5715.4    33.3  5720.4    33.6
  5730.4      35  5750.4    35.8  5760.4    36.8  5830.4    40.6  5866.2   41.22
    5871    41.3
BR U #Mann= 5
    4171      .2  4290.6      .1  4794.4    .035  5036.4      .1  5866.2      .2
BR U Banks=4794.4,5036.4
BR D #Sta/Elev= 86
    4171   42.15  4290.6   40.04  4295.6   39.95  4315.6   39.45  4320.6   39.15
  4330.6   38.35  4343.7   36.65  4393.7   35.85  4438.7   34.85  4458.7   34.05
    4471   33.25 4471.09   33.24  4471.2   33.24 4471.31   33.23  4478.7   32.75
  4498.7   32.75  4503.7   32.55  4523.7   32.75  4533.7   33.35  4543.7   33.35
  4555.8   33.36  4623.4      34  4683.5   33.98  4695.4   33.98  4778.3   25.02
    4785   28.74 4785.11   28.81  4785.2   28.86  4785.3   28.91  4794.4   33.97
  4813.4   27.55    4831   15.92  4831.1   15.85  4841.3   17.07  4868.7   15.32
  4901.1   -1.29  4904.9    -1.1  4938.1   -3.16  4943.5      -3  4971.4    10.4
  4973.4   11.67  4984.3   10.94  4989.6    8.03  4994.6    7.08  4998.4    6.48
  5002.4    7.21    5007    7.16  5010.4    7.96    5035   28.25  5036.4    29.2
  5038.1   29.65  5038.2   29.68  5063.1   33.51  5080.3   34.98 5090.99   34.96
  5091.1   34.96  5091.2   34.96  5159.3   34.82  5257.7   33.71  5336.2   33.23
 5338.29   33.22  5338.4   33.22 5338.51   33.22  5338.6   33.22  5421.2   32.95
  5520.4    33.5  5526.6   29.75  5531.6   29.65  5536.6   29.85  5556.6   32.05
  5571.6   34.15  5576.6   34.45  5591.6   33.75  5621.6   35.45  5641.6   35.35
  5666.6   34.85  5691.6   32.75  5701.6   32.55  5715.4   33.25  5720.4   33.55
  5730.4   34.95  5750.4   35.75  5760.4   36.75  5830.4   40.55  5866.2   41.17
    5871   41.25
BR D #Mann= 5
    4171      .2  4290.6      .1  4794.4    .035  5036.4      .1  5866.2      .2
BR D Banks=4794.4,5036.4
BC Design=,, 0 ,, 0 ,,,,,,
BC HTab HWMax=43.13
BC Use User HTab Curves=0
BC User HTab FreeFlow(D)= 0

Type RM Length L Ch R = 1 ,39266.8 ,565.1,565.1,565.1
BEGIN DESCRIPTION:
Downstream Section of Bridge/Culvert/Weir
END DESCRIPTION:
XS GIS Cut Line= 4
      3138606.51     13804928.81      3138819.31     13804207.62
      3138934.94     13803817.38      3139089.03     13803298.73
#Sta/Elev= 30
    4171   42.18  4290.6   40.07  4343.7   36.68  4478.7   32.78  4695.4   34.01
  4778.3   25.05  4794.4      34  4813.4   27.58  4831.1   15.88  4841.3    17.1
  4868.7   15.35  4901.1   -1.26  4938.1   -3.13  4943.5   -2.97  4973.4    11.7
  4984.3   10.97  4989.6    8.06  4998.4    6.51  5010.4    7.99  5036.4   29.23
  5080.3   35.01  5520.4   33.53  5526.6   29.78  5531.6   29.68  5576.6   34.48
  5641.6   35.38  5701.6   32.58  5830.4   40.58  5866.2    41.2    5871   41.28
#Mann= 5 , 1 , 0
    4171      .2       0  4290.6      .1       0  4794.4    .035       0
  5036.4      .1       0  5866.2      .2       0
#XS Ineff= 2 , 0
       0    4773   42.24    5102       0    41.5
Permanent Ineff=
       F       F
Bank Sta=4794.4,5036.4
XS Rating Curve= 0 ,0
Exp/Cntr=0.5,0.3

Type RM Length L Ch R = 1 ,38701.7 ,357.9,495.4,649
BEGIN DESCRIPTION:
Cross Section 38701.7-Interpolated
END DESCRIPTION:
XS GIS Cut Line= 6
      3138393.41     13805714.63      3139290.15     13804445.08
      3139485.46     13804097.86      3140386.07     13802958.53
      3140546.28     13802725.09      3141042.67     13802035.98
#Sta/Elev= 30
  3130.5    40.6  3160.5    39.5  3810.5      36  3845.5    34.9  3885.5    35.9
  4090.5    36.4  4155.5    34.5  4195.5    36.1  4365.5    36.8  4400.5    36.3
  4435.5    33.9  4510.5    35.9  4745.5    35.3  4819.4    34.2  4834.4    32.9
  4846.4   27.41  4888.6   17.71  4961.6    4.02  4979.8   -1.47  5015.8   -1.51
  5057.4    5.34  5100.6    10.5  5164.1   28.57  5164.4    27.5  5202.7    29.9
  5437.7    33.1    6655    35.4  6990.6   34.91  7578.2   35.58  7667.9   36.81
#Mann= 5 , 1 , 0
  3130.5      .2       0  3130.5      .1       0  4846.4    .035       0
  5164.1      .1       0  6990.6      .2       0
Bank Sta=4846.4,5164.1
XS Rating Curve= 0 ,0
Exp/Cntr=0.3,0.1

Type RM Length L Ch R = 1 ,38206.3 ,577.2,482.9,340
BEGIN DESCRIPTION:
Cross Section 38206.3
END DESCRIPTION:
XS GIS Cut Line= 6
      3138713.46      13805468.2      3139392.77     13804724.32
      3139836.94     13804648.49      3140459.87     13804177.23
      3141339.11     13803892.07      3142000.34     13803669.51
#Sta/Elev= 30
  3616.8    37.2  3696.8    35.8  3875.7    37.3  4020.7    34.8  4265.7    36.7
  4305.7    34.3  4390.7    36.8  4525.7    36.9  4585.7      36  4630.7    33.4
  4715.7    35.6  4819.4    33.8  4834.4    33.1  4835.1   28.75  4846.4   28.83
  4888.6   19.13  4961.6    5.44  4979.8    -.05  5015.8    -.09  5100.6   11.92
  5164.1   33.99  5195.6   30.58  5233.5   30.33    5390    33.6  6101.1    32.3
  6131.1    33.6  6716.1    35.6  6905.5    34.4  6935.5    35.6  7477.9    36.3
#Mann= 4 , 1 , 0
  3616.8      .1       0  4846.4    .035       0  5164.1      .1       0
  7477.9      .2       0
Bank Sta=4846.4,5164.1
XS Rating Curve= 0 ,0
Exp/Cntr=0.3,0.1

Type RM Length L Ch R = 1 ,37723.4 ,598.7,588.3,570.1
BEGIN DESCRIPTION:
Cross Section 37723.4-Interpolated
END DESCRIPTION:
XS GIS Cut Line= 6
      3138851.39      13806050.7      3139420.36     13805530.15
      3139897.79     13805085.27      3140245.01     13804640.39
      3140689.89     13804325.72      3141724.83      13803818.4
#Sta/Elev= 30
  3583.4    37.4  3698.4    36.5  3723.4    35.1  3788.4    36.6  3993.4    36.1
  4053.4    34.1  4118.4    36.1  4324.6    36.2  4374.6    33.6  4459.6    36.1
  4569.6    36.4  4634.6    34.2  4749.6    37.1  4809.6    36.2  4834.6    33.6
  4845.4   30.73  4929.9   11.66  4954.3    9.11  4971.1    1.73  4998.2    -.42
    5027    1.66  5035.1    4.46  5062.1    5.92  5158.7   31.82  5187.2    29.9
  5217.2    32.6  5491.5      33  5756.5    30.4  5936.5    32.9    7269    36.3
#Mann= 5 , 1 , 0
  3583.4      .2       0  3583.4      .1       0  4845.4    .035       0
  5158.7      .1       0    7269      .2       0
Bank Sta=4845.4,5158.7
XS Rating Curve= 0 ,0
Exp/Cntr=0.3,0.1

Type RM Length L Ch R = 1 ,37135.1 ,524.7,567.5,595
BEGIN DESCRIPTION:
Cross Section 37135.1
END DESCRIPTION:
XS GIS Cut Line= 6
      3139808.06     13805930.23      3140160.24     13805681.04
       3140684.2     13804916.45        3140952.     13804613.72
      3141429.45     13804187.07      3141858.28     13803816.44
#Sta/Elev= 30
  3999.9    36.6  4034.9    35.1  4089.9    34.7  4388.9    36.4  4598.9    34.4
  4653.9    32.5  4708.9    33.6  4783.9    32.8  4807.3   30.33  4845.4   30.32
  4929.9   11.25  4954.3     8.7  4971.1    1.32  4998.2    -.83    5027    1.25
  5035.1    4.05  5062.1    5.51  5158.7   31.41  5194.8   28.56  5221.6   28.84
  5315.8      33  5470.8    32.9  5495.8    33.5  5904.9    34.4  5939.9    33.4
  5979.9    34.7  6540.2    35.7  6565.2      35  6600.2      36  6969.5    36.5
#Mann= 4 , 1 , 0
  3999.9      .1       0  4845.4    .035       0  5158.7      .1       0
  6969.5      .2       0
Bank Sta=4845.4,5158.7
XS Rating Curve= 0 ,0
Exp/Cntr=0.3,0.1

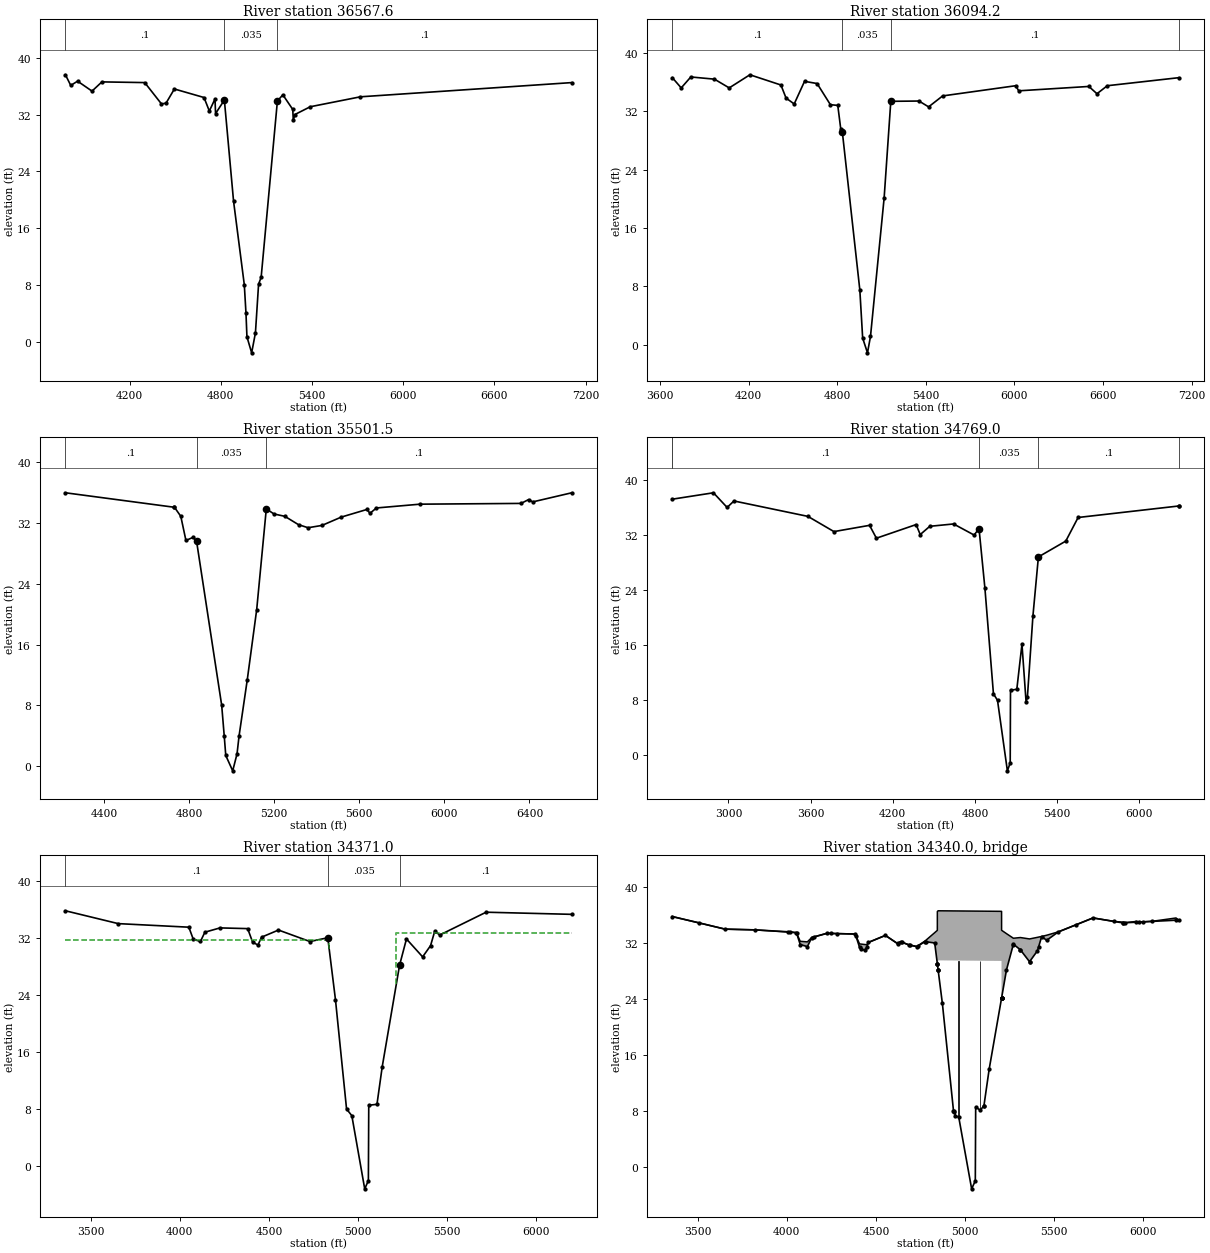
Type RM Length L Ch R = 1 ,36567.6 ,446,473.4,491.8
BEGIN DESCRIPTION:
Cross Section 36567.6
END DESCRIPTION:
XS GIS Cut Line= 6
      3139818.71     13806180.22      3140245.63     13806045.87
      3140618.22     13805816.88      3141107.25     13805386.07
      3141865.99     13805113.07      3142752.84     13804676.87
#Sta/Elev= 30
  3777.3    37.6  3812.3    36.1  3857.3    36.7  3952.3    35.3  4017.3    36.6
  4299.1    36.5  4409.1    33.5  4439.1    33.6  4494.1    35.6  4689.1    34.4
  4724.1    32.5  4761.5    34.2    4765   32.14    4823   34.04  4883.6   19.78
  4954.2    8.04  4965.1    4.08  4971.5     .72  5002.5   -1.54  5027.4    1.27
  5048.1    8.13    5065    9.09  5171.9   33.91  5207.8   34.78    5273   32.72
  5276.5    31.2  5286.5      32  5388.2    33.1  5718.2    34.5  7108.6    36.5
#Mann= 3 , 1 , 0
  3777.3      .1       0    4823    .035       0  5171.9      .1       0
Bank Sta=4823,5171.9
XS Rating Curve= 0 ,0
Exp/Cntr=0.3,0.1

Type RM Length L Ch R = 1 ,36094.2 ,613.3,592.7,563.7
BEGIN DESCRIPTION:
Cross Section 36094.2-Interpolated
END DESCRIPTION:
XS GIS Cut Line= 4
      3139937.94     13806719.82      3141069.67     13806029.28
      3141579.65     13805703.76      3142853.34     13804916.38
#Sta/Elev= 30
    3684    36.6    3744    35.2    3809    36.7    3969    36.4    4069    35.2
    4209      37    4419    35.6    4454    33.8    4509      33    4579    36.1
    4664    35.8    4754    32.9    4804    32.8    4824    29.6    4835   29.14
  4953.3     7.5  4972.5     .89  5005.1   -1.13  5025.5    1.12  5117.9   20.11
    5163   33.36  5353.9    33.4  5418.9    32.6  5513.9    34.1  6008.9    35.5
  6028.9    34.8  6503.9    35.4  6558.9    34.4  6628.9    35.5  7112.2    36.6
#Mann= 4 , 1 , 0
    3684      .1       0    4835    .035       0    5163      .1       0
  7112.2      .2       0
Bank Sta=4835,5163
XS Rating Curve= 0 ,0
Exp/Cntr=0.3,0.1

Type RM Length L Ch R = 1 ,35501.5 ,732.4,732.5,750.6
BEGIN DESCRIPTION:
Cross Section 35501.5
END DESCRIPTION:
XS GIS Cut Line= 6
      3140647.55     13806873.23      3141060.67     13806756.13
      3141460.43     13806426.23      3141646.73     13806236.05
       3142509.5     13805580.78      3142563.28     13805517.59
#Sta/Elev= 30
  4218.7      36  4728.7    34.1  4731.1    34.1  4761.1    32.9  4785.2   29.72
  4818.6   30.13    4835   29.66  4953.3    8.02  4965.2       4  4972.5    1.41
  5005.1    -.61  5025.5    1.64  5034.9    3.97  5073.7   11.41  5117.9   20.63
    5163   33.88  5199.2   33.21  5250.1    32.9  5314.4    31.8  5359.4    31.4
  5424.4    31.7  5515.6    32.8  5635.6    33.8  5650.6    33.3  5680.6      34
  5885.6    34.5  6360.6    34.6  6395.6    35.1  6415.6    34.8    6599      36
#Mann= 3 , 1 , 0
  4218.7      .1       0    4835    .035       0    5163      .1       0
Bank Sta=4835,5163
XS Rating Curve= 0 ,0
Exp/Cntr=0.3,0.1

Type RM Length L Ch R = 1 ,34769.0 ,232.3,398,337
BEGIN DESCRIPTION:
Cross Section 34769.0 - Interpolated
END DESCRIPTION:
XS GIS Cut Line= 4
      3139976.23     13808394.05      3141508.62     13807343.54
      3141870.79      13807029.3      3142866.06     13806102.45
#Sta/Elev= 30
  2590.3   37.22  2890.3   38.15  2990.3   36.02  3040.3   36.96  3580.3   34.72
  3770.3   32.51  4030.3   33.42  4080.3   31.55  4370.3   33.53  4400.3   32.08
  4470.3   33.28  4643.8   33.62  4793.8   32.01  4829.7   32.94  4872.7   24.28
    4935    8.94  4964.6       8  5036.8   -2.25  5057.4    -1.1  5059.5    9.46
  5105.6     9.6  5143.2   16.15  5173.2    7.77  5183.2    8.54  5223.2   20.24
  5263.2   28.83  5463.2   31.13  5553.2   34.56  6287.6   36.23  6287.7   36.23
#Mann= 5 , 1 , 0
  2590.3      .2       0  2590.3      .1       0  4829.7    .035       0
  5263.2      .1       0  6287.6      .2       0
Bank Sta=4829.7,5263.2
XS Rating Curve= 0 ,0
Exp/Cntr=0.5,0.3

Type RM Length L Ch R = 1 ,34371.0 ,62,62,62
BEGIN DESCRIPTION:
Upstream Section of Bridge/Culvert/Weir
END DESCRIPTION:
XS GIS Cut Line= 6
      3140844.29     13808250.12      3141284.13     13807926.25
       3141869.8      13807368.7      3142320.67      13807160.7
       3142603.2     13806740.08      3142843.71     13806322.89
#Sta/Elev= 30
    3358   35.82  3654.2   34.02  4050.3   33.52  4075.3   31.82  4115.3   31.52
  4140.3   32.82  4225.3   33.42  4380.3   33.32  4408.1   31.42  4438.1   31.02
  4458.1   32.12  4553.1   33.12  4729.7   31.51  4829.7   32.04  4872.7   23.38
    4935    8.04  4964.6     7.1  5036.8   -3.15  5057.4      -2  5059.5    8.56
  5105.6     8.7  5135.1   13.97  5232.2   28.18    5271   31.87  5361.7   29.36
  5406.1   30.93  5429.7   32.96  5457.6   32.42  5717.7   35.62  6198.3   35.32
#Mann= 3 , 1 , 0
    3358      .1       0  4829.7    .035       0  5232.2      .1       0
#XS Ineff= 2 , 0
       0    4838   31.71    5214       0   32.75
Permanent Ineff=
       F       F
Bank Sta=4829.7,5232.2
XS Rating Curve= 0 ,0
Exp/Cntr=0.5,0.3

Type RM Length L Ch R = 3 ,34340.0 ,,,
BEGIN DESCRIPTION:
SWALLOW STREET
Structure ID: C00-19
END DESCRIPTION:
Bridge Culvert--1,0,-1,-1, 0
Deck Dist Width WeirC Skew NumUp NumDn MinLoCord MaxHiCord MaxSubmerge Is_Ogee
10,42,2.6,0, 49, 49, , , 0.95, 0, 1,1,,
    3358  3654.2  3819.2  4050.3  4055.3  4075.3  4115.3  4140.3  4225.3  4380.3
  4388.1  4408.1  4418.1  4438.1  4448.1  4458.1  4553.1  4621.1  4638.2  4685.3
  4729.7  4775.1  4829.7 4844.39  4844.5    4849 4849.11  4849.2 5204.39  5204.5
  5204.8 5204.91  5232.2    5271  5310.3  5361.7  5406.1  5429.7  5457.6  5522.6
  5717.7  5836.5  5884.6  5898.3  5958.3  5978.3  6048.3  6183.3  6198.3
    35.8      34    33.9   33.51   33.41   32.26   32.18   32.81   33.41   33.31
   33.01   31.89   31.86    31.8   31.77   32.11   33.11   31.94   32.21   31.75
   31.53    32.3    33.5   33.83   36.53   36.63   36.63   36.63   36.55   36.55
   36.54   33.84   33.36    32.7    32.8    32.6   32.83   32.96   33.13   33.61
   35.61   35.11      35   34.93    35.1   35.03   35.12    35.6    35.3
    35.8      34    33.9    33.5    33.4    31.8    31.5    32.8    33.4    33.3
      33    31.4    31.1      31    31.4    32.1    33.1   31.93    32.2   31.74
   31.49   32.22   32.02   29.06   29.04   28.13   28.11   29.53   29.45   24.11
   24.15   24.17   28.16   31.85   31.04   29.34   30.91   32.94    32.4    33.6
    35.6    35.1    34.9   34.92   34.99   35.02   35.11   35.28    35.3
    3358  3654.2  3819.2  4050.3  4055.3  4075.3  4115.3  4140.3  4225.3  4380.3
  4388.1  4408.1  4418.1  4438.1  4448.1  4458.1  4553.1  4621.1  4638.2  4685.3
  4729.7  4775.1  4829.7 4844.39  4844.5    4849 4849.11  4849.2 5204.39  5204.5
  5204.8 5204.91  5232.2    5271  5310.3  5361.7  5406.1  5429.7  5457.6  5522.6
  5717.7  5836.5  5884.6  5898.3  5958.3  5978.3  6048.3  6183.3  6198.3
    35.8      34    33.9   33.51   33.41   32.26   32.18   32.81   33.41   33.31
   33.01   31.89   31.86    31.8   31.77   32.11   33.11   31.94   32.21   31.75
   31.53    32.3    33.5   33.83   36.53   36.63   36.63   36.63   36.55   36.55
   36.54   33.84   33.36    32.7    32.8    32.6   32.83   32.96   33.13   33.61
   35.61   35.11      35   34.93    35.1   35.03   35.12    35.6    35.3
    35.8      34    33.9    33.5    33.4    31.8    31.5    32.8    33.4    33.3
      33    31.4    31.1      31    31.4    32.1    33.1   31.93    32.2   31.74
   31.49   32.22   32.02   29.06   29.04   28.13   28.11   29.53   29.45   24.11
   24.15   24.17   28.16   31.85   31.04   29.34   30.91   32.94    32.4    33.6
    35.6    35.1    34.9   34.92   34.99   35.02   35.11   35.28    35.3
Pier Skew, UpSta & Num, DnSta & Num=  ,4964.6, 2 ,4964.6, 2 , 0 , 0 , 0 ,,
       4       4
     5.8    30.5
       4       4
     5.8    30.5
Pier Skew, UpSta & Num, DnSta & Num=  ,5084.4, 2 ,5084.4, 2 , 0 , 0 , 0 ,,
       4       4
    7.14   30.48
       4       4
    7.14   30.48
Abutment Skew #Up #Dn= , 2 , 2
    4849  4935.1
   29.53    8.02
    4849  4935.1
   29.53    8.02
Abutment Skew #Up #Dn= , 2 , 2
  5105.6 5204.59
    8.68   29.45
  5105.6 5204.59
    8.68   29.45
BR Coef= 1 , 1 , 0 ,1.25, 0 ,,,0.8,0,2,0,
WSPro=,,,, 1 ,,,, 0 ,,,, 0 ,,,,-1 ,-1 ,-1 , 0 , 0 , 0 , 0 , 0
BR U #Sta/Elev= 83
    3358    35.8    3508    34.9  3654.2      34  3819.2    33.9  4008.7   33.62
  4020.3    33.6  4050.3    33.5  4055.3    33.4  4075.3    31.8  4115.3    31.5
  4140.3    32.8  4153.7   32.89  4225.3    33.4  4248.7   33.38  4280.4   33.36
  4380.3    33.3  4388.1      33  4408.1    31.4  4418.1    31.1  4438.1      31
  4448.1    31.4  4458.1    32.1  4553.1    33.1  4621.1   31.93  4626.2   32.01
  4638.2    32.2  4645.4   32.13  4685.3   31.74  4690.9   31.71  4729.7   31.49
  4737.1   31.61  4775.1   32.22  4782.8   32.19  4829.7   32.02 4844.39   29.06
  4844.5   29.04 4844.61   29.02    4849   28.13 4849.11   28.11  4849.2   28.09
  4872.7   23.36    4935    8.02  4935.1    8.02  4940.6    7.81  4946.1    7.31
  4964.6    7.08  5036.8   -3.17  5057.4   -2.02  5059.5    8.54  5084.4     8.1
  5105.5    8.68  5105.6    8.68  5135.1   13.95 5204.39   24.09  5204.5   24.11
 5204.59   24.12  5204.7   24.14  5204.8   24.15 5204.91   24.17  5232.2   28.16
  5270.4   31.79    5271   31.85  5308.4   31.08  5310.3   31.04  5361.6   29.34
  5361.7   29.34  5406.1   30.91  5412.7   31.48  5429.7   32.94  5457.6    32.4
  5522.6    33.6  5621.5   34.61  5717.7    35.6  5836.5    35.1  5884.6    34.9
  5888.3    34.9  5898.3   34.92  5958.3   34.99  5978.3   35.02  5998.3   35.04
  6048.3   35.11  6183.3   35.28  6198.3    35.3
BR U #Mann= 3
    3358      .1  4829.7    .035  5232.2      .1
BR U Banks=4829.7,5232.2
BR D #Sta/Elev= 83
    3358    35.8    3508    34.9  3654.2      34  3819.2    33.9  4008.7   33.62
  4020.3    33.6  4050.3    33.5  4055.3    33.4  4075.3    31.8  4115.3    31.5
  4140.3    32.8  4153.7   32.89  4225.3    33.4  4248.7   33.38  4280.4   33.36
  4380.3    33.3  4388.1      33  4408.1    31.4  4418.1    31.1  4438.1      31
  4448.1    31.4  4458.1    32.1  4553.1    33.1  4621.1   31.93  4626.2   32.01
  4638.2    32.2  4645.4   32.13  4685.3   31.74  4690.9   31.71  4729.7   31.49
  4737.1   31.61  4775.1   32.22  4782.8   32.19  4829.7   32.02 4844.39   29.06
  4844.5   29.04 4844.61   29.02    4849   28.13 4849.11   28.11  4849.2   28.09
  4872.7   23.36    4935    8.02  4935.1    8.02  4940.6    7.81  4946.1    7.31
  4964.6    7.08  5036.8   -3.17  5057.4   -2.02  5059.5    8.54  5084.4     8.1
  5105.5    8.68  5105.6    8.68  5135.1   13.95 5204.39   24.09  5204.5   24.11
 5204.59   24.12  5204.7   24.14  5204.8   24.15 5204.91   24.17  5232.2   28.16
  5270.4   31.79    5271   31.85  5308.4   31.08  5310.3   31.04  5361.6   29.34
  5361.7   29.34  5406.1   30.91  5412.7   31.48  5429.7   32.94  5457.6    32.4
  5522.6    33.6  5621.5   34.61  5717.7    35.6  5836.5    35.1  5884.6    34.9
  5888.3    34.9  5898.3   34.92  5958.3   34.99  5978.3   35.02  5998.3   35.04
  6048.3   35.11  6183.3   35.28  6198.3    35.3
BR D #Mann= 3
    3358      .1  4829.7    .035  5232.2      .1
BR D Banks=4829.7,5232.2
BC Design=,, 0 ,, 0 ,,,,,,
BC HTab HWMax=35.82
BC Use User HTab Curves=0
BC User HTab FreeFlow(D)= 0