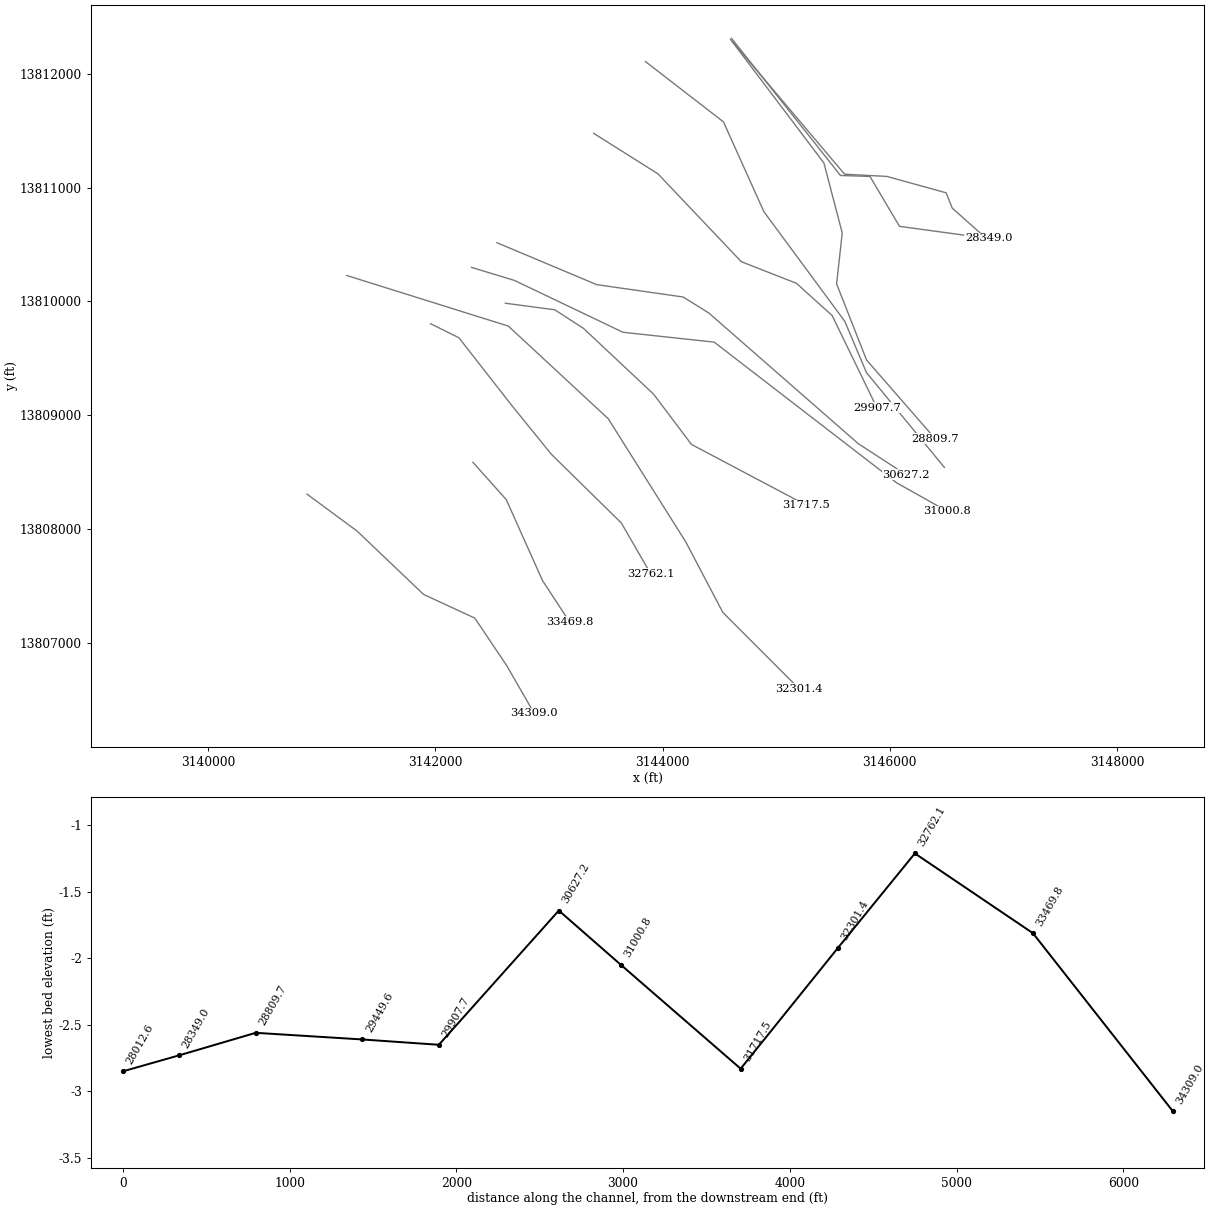
HEC-RAS study C100-00-00.prj: C100-00-00

--- C100-00-00.g01 (geometry) --- (continued)

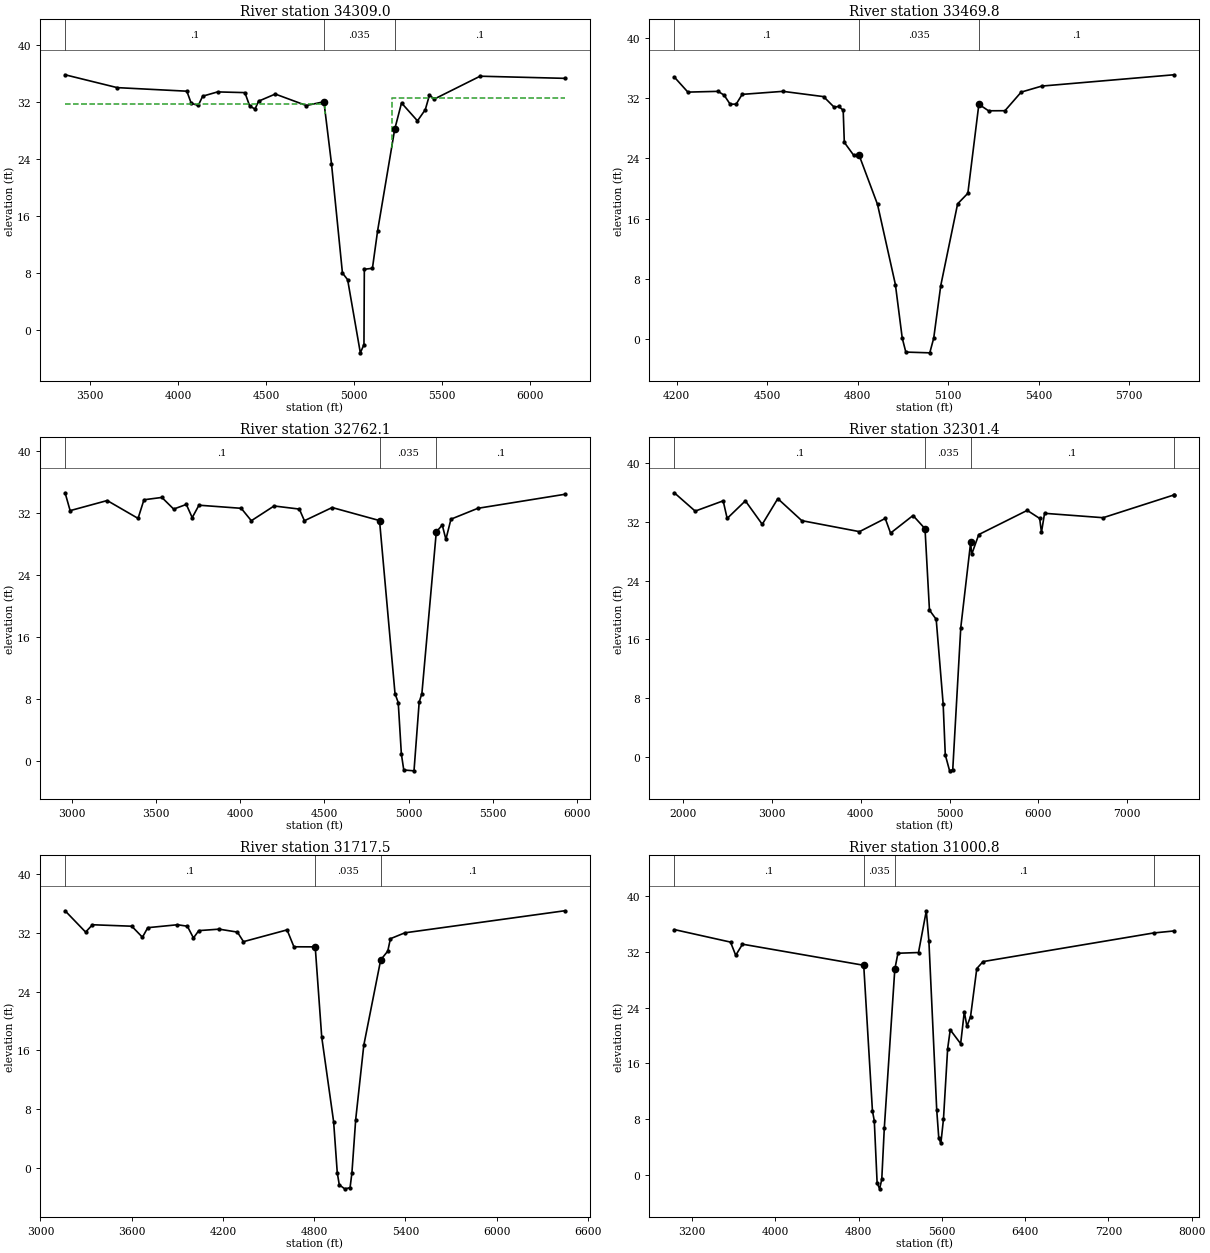
Type RM Length L Ch R = 1 ,34309.0 ,839.2,839.2,839.2
BEGIN DESCRIPTION:
Downstream Section of Bridge/Culvert/Weir
END DESCRIPTION:
XS GIS Cut Line= 6
      3140871.66     13808305.75      3141311.49     13807981.89
      3141897.16     13807424.34      3142348.03     13807216.34
      3142630.56     13806795.72      3142871.08     13806378.52
#Sta/Elev= 30
    3358   35.82  3654.2   34.02  4050.3   33.52  4075.3   31.82  4115.3   31.52
  4140.3   32.82  4225.3   33.42  4380.3   33.32  4408.1   31.42  4438.1   31.02
  4458.1   32.12  4553.1   33.12  4729.7   31.51  4829.7   32.04  4872.7   23.38
    4935    8.04  4964.6     7.1  5036.8   -3.15  5057.4      -2  5059.5    8.56
  5105.6     8.7  5135.1   13.97  5232.2   28.18    5271   31.87  5361.7   29.36
  5406.1   30.93  5429.7   32.96  5457.6   32.42  5717.7   35.62  6198.3   35.32
#Mann= 3 , 1 , 0
    3358      .1       0  4829.7    .035       0  5232.2      .1       0
#XS Ineff= 2 , 0
       0    4838   31.71    5214       0    32.6
Permanent Ineff=
       F       F
Bank Sta=4829.7,5232.2
XS Rating Curve= 0 ,0
Exp/Cntr=0.5,0.3

Type RM Length L Ch R = 1 ,33469.8 ,635.7,707.7,794.1
BEGIN DESCRIPTION:
Cross Section 33469.8
END DESCRIPTION:
XS GIS Cut Line= 4
      3142331.54     13808585.88      3142624.79     13808258.14
      3142943.04     13807547.89      3143182.68     13807181.59
#Sta/Elev= 30
  4192.3    34.8  4237.3    32.8  4337.3    32.9  4357.3    32.4  4377.3    31.2
  4397.3    31.2  4417.3    32.5  4552.3    32.9  4687.1    32.2  4722.1    30.8
  4737.1    30.9  4752.1    30.4  4755.8   26.13  4786.8   24.42  4805.1    24.4
  4865.9   17.89  4925.1    7.26  4947.8     .15  4959.7   -1.71  5039.1   -1.81
  5052.2     .15  5075.5    7.12  5131.4   17.97  5165.3   19.37  5201.8   31.18
    5234   30.32  5288.3   30.33  5342.1    32.8  5410.4    33.6  5848.1    35.1
#Mann= 3 , 1 , 0
  4192.3      .1       0  4805.1    .035       0  5201.8      .1       0
Bank Sta=4805.1,5201.8
XS Rating Curve= 0 ,0
Exp/Cntr=0.3,0.1

Type RM Length L Ch R = 1 ,32762.1 ,522.8,460.7,420.5
BEGIN DESCRIPTION:
Cross Section 32762.1
END DESCRIPTION:
XS GIS Cut Line= 6
      3141958.92     13809804.62      3142208.05     13809681.07
      3142671.36     13809088.71      3143020.67      13808657.9
      3143637.77     13808052.44      3143895.81     13807606.74
#Sta/Elev= 30
  2961.5    34.6  2991.5    32.3  3211.5    33.6  3394.6    31.3  3429.6    33.7
  3535.9      34  3605.9    32.5  3680.9    33.1  3715.9    31.4  3755.9      33
  4006.7    32.6  4066.7      31  4201.7    32.9  4351.7    32.5  4381.7      31
  4546.3    32.7  4827.5   31.02  4919.4    8.73  4938.5    7.58    4957     .98
  4971.3    -1.1  5032.1   -1.21  5062.8    7.65  5078.9    8.75  5164.3   29.55
  5199.7   30.45  5221.3    28.6  5251.3    31.2  5410.8    32.6  5925.8    34.4
#Mann= 3 , 1 , 0
  2961.5      .1       0  4827.5    .035       0  5164.3      .1       0
Bank Sta=4827.5,5164.3
XS Rating Curve= 0 ,0
Exp/Cntr=0.3,0.1

Type RM Length L Ch R = 1 ,32301.4 ,477.5,583.9,569.5
BEGIN DESCRIPTION:
Cross Section 32301.4-Interpolated
END DESCRIPTION:
XS GIS Cut Line= 6
      3141221.58      13810228.5      3142643.02     13809783.62
      3143521.92     13808969.82      3144205.52     13807884.75
      3144531.04     13807266.26      3145203.78     13806593.52
#Sta/Elev= 30
  1901.4      36  2136.4    33.5  2451.4    34.9  2496.4    32.5  2701.4    34.9
  2891.4    31.7  3066.4    35.2  3336.4    32.2  3985.8    30.7  4275.8    32.5
  4335.8    30.5  4588.6    32.9  4723.6    31.1  4773.6      20  4849.5   18.74
  4927.8    7.21  4951.8     .26  5000.5   -1.92  5035.8   -1.77  5126.2   17.62
  5237.3   29.23  5248.6    27.6  5328.7    30.3  5874.4    33.6  6014.4    32.5
  6034.4    30.6  6069.4    33.2  6728.3    32.6  7524.6    35.7  7524.7    35.7
#Mann= 4 , 1 , 0
  1901.4      .1       0  4723.6    .035       0  5237.3      .1       0
  7524.6      .2       0
Bank Sta=4723.6,5237.3
XS Rating Curve= 0 ,0
Exp/Cntr=0.3,0.1

Type RM Length L Ch R = 1 ,31717.5 ,570.5,716.7,850
BEGIN DESCRIPTION:
Cross Section 31717.5
END DESCRIPTION:
XS GIS Cut Line= 6
      3142616.91     13809984.79      3143051.72     13809927.05
      3143303.99     13809764.04       3143921.1     13809185.74
      3144254.88     13808743.29      3145267.46       13808208.
#Sta/Elev= 30
  3162.2      35  3297.2    32.1  3342.2    33.1  3600.8    32.9  3670.8    31.4
  3705.8    32.7  3901.2    33.1  3966.2    32.9  4006.2    31.3  4041.2    32.3
  4175.1    32.5  4295.1    32.1  4335.1    30.8  4621.7    32.4  4666.7    30.1
  4806.8   30.09  4849.5   17.83  4927.8     6.3  4951.8    -.65    4965   -2.28
  5000.5   -2.83  5035.8   -2.68  5048.1    -.66  5072.9     6.6  5126.2   16.71
  5237.3   28.32  5283.8   29.51  5301.1    31.2  5396.1      32  6446.5      35
#Mann= 3 , 1 , 0
  3162.2      .1       0  4806.8    .035       0  5237.3      .1       0
Bank Sta=4806.8,5237.3
XS Rating Curve= 0 ,0
Exp/Cntr=0.3,0.1

Type RM Length L Ch R = 1 ,31000.8 ,380.5,373.6,111.1
BEGIN DESCRIPTION:
Cross Section 31000.8-Interpolated
END DESCRIPTION:
XS GIS Cut Line= 6
      3142319.22     13810299.86      3142697.27      13810185.1
      3143652.13     13809729.37      3144455.08     13809642.56
      3146060.99     13808405.58      3146505.86     13808156.02
#Sta/Elev= 30
  3030.4    35.2  3570.4    33.4  3620.4    31.5  3685.4    33.1  4849.9   30.07
  4933.7    9.14  4951.4    7.73  4978.6    -1.2  5002.3   -2.05  5023.2     -.7
  5047.5    6.66  5148.5    29.5  5178.5    31.8  5376.1    31.9  5451.1    37.9
  5476.1    33.5  5551.1     9.3  5571.1     5.2  5591.1     4.5  5616.1       8
  5656.1    18.1  5681.1    20.8  5781.1    18.8  5816.1    23.4  5841.1    21.3
  5876.1    22.7  5936.1    29.6  5996.1    30.6  7633.5   34.71  7828.9      35
#Mann= 4 , 1 , 0
  3030.4      .1       0  4849.9    .035       0  5148.5      .1       0
  7633.5      .2       0
Bank Sta=4849.9,5148.5
XS Rating Curve= 0 ,0
Exp/Cntr=0.3,0.1

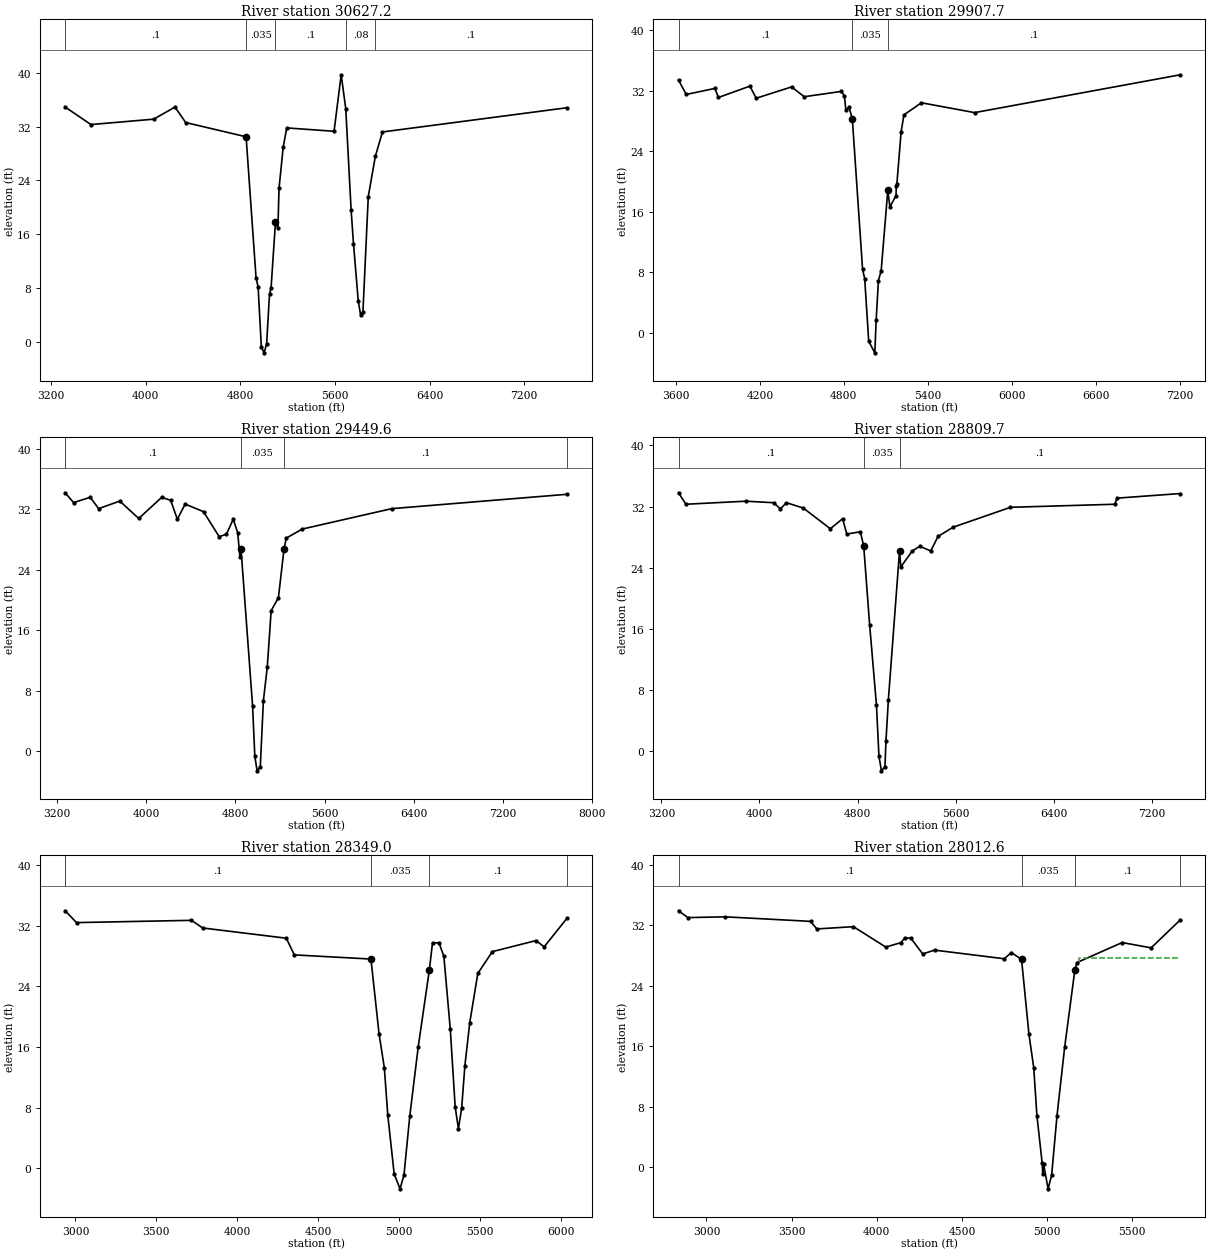
Type RM Length L Ch R = 1 ,30627.2 ,828,719.5,650
BEGIN DESCRIPTION:
Cross Section 30627.2
END DESCRIPTION:
XS GIS Cut Line= 6
      3142542.28     13810517.04      3143420.43     13810148.27
      3144181.14      13810039.6      3144406.24     13809899.88
      3145723.99     13808749.26      3146143.39      13808477.1
#Sta/Elev= 30
  3321.6    34.9  3539.1    32.3  4069.1    33.1  4249.1    34.9  4339.4    32.6
  4849.9   30.48  4933.7    9.55  4951.4    8.14  4978.6    -.79  5002.3   -1.64
  5023.2    -.29  5047.5    7.07  5060.9    8.06  5097.8   17.75  5118.6   16.87
  5127.9    22.8  5162.9    28.9  5192.9    31.8  5592.9    31.3  5652.9    39.7
  5691.6   34.67  5736.9    19.6  5756.9    14.6  5796.9     6.1  5816.9       4
  5836.9     4.5  5881.9    21.6  5941.6   27.58  6001.9    31.2  7560.5    34.8
#Mann= 5 , 1 , 0
  3321.6      .1       0  4849.9    .035       0  5097.8      .1       0
  5691.6     .08       0  5941.6      .1       0
Bank Sta=4849.9,5097.8
XS Rating Curve= 0 ,0
Exp/Cntr=0.3,0.1

Type RM Length L Ch R = 1 ,29907.7 ,489.2,458.1,450
BEGIN DESCRIPTION:
Cross Section 29907.7
END DESCRIPTION:
XS GIS Cut Line= 6
      3143394.64     13811478.36      3143959.91     13811122.45
      3144693.45     13810350.09       3145178.6     13810159.92
      3145492.97     13809876.59      3145887.72     13809064.46
#Sta/Elev= 30
  3618.6    33.4  3673.6    31.5  3878.6    32.3  3903.6    31.1  4128.6    32.6
  4173.6      31  4426.6    32.5  4516.6    31.2  4781.6    31.9  4803.9    31.3
  4813.9   29.48  4836.2   29.81  4860.3   28.31  4933.6    8.41  4948.9    7.15
  4977.6   -1.12  5021.2   -2.65  5030.9    1.72    5047    6.91  5066.6    8.21
  5113.8   18.82    5129   16.64    5173   18.14  5173.9    19.4  5178.9    19.7
  5208.9    26.5  5228.9    28.8  5354.4    30.4  5734.4    29.1  7204.2    34.1
#Mann= 3 , 1 , 0
  3618.6      .1       0  4860.3    .035       0  5113.8      .1       0
Bank Sta=4860.3,5113.8
XS Rating Curve= 0 ,0
Exp/Cntr=0.3,0.1

Type RM Length L Ch R = 1 ,29449.6 ,663.1,639.9,579.1
BEGIN DESCRIPTION:
Cross Section 29449.6-Interpolated
END DESCRIPTION:
XS GIS Cut Line= 6
       3143850.7     13812108.93      3144536.46     13811579.41
      3144892.37     13810789.48      3145604.17     13809825.94
      3145795.14     13809374.55      3146480.91     13808541.22
#Sta/Elev= 30
    3272    34.2    3347    32.9    3497    33.6    3572    32.1    3762    33.1
    3932    30.8  4138.4    33.6  4218.4    33.2  4278.4    30.7  4348.4    32.7
  4513.4    31.7  4653.4    28.4  4718.4    28.7  4780.1    30.7  4820.1    28.9
  4840.1    25.7  4849.6   26.78  4953.5    5.99  4973.8     -.7  4994.2   -2.61
  5022.7   -2.07  5050.6    6.68  5085.3    11.1  5120.3    18.6  5185.3    20.3
  5235.3    26.7  5255.3    28.2  5400.3    29.4  6202.5    32.1  7774.9      34
#Mann= 5 , 1 , 0
    3272      .2       0    3272      .1       0  4849.6    .035       0
  5235.3      .1       0  7774.9      .2       0
Bank Sta=4849.6,5235.3
XS Rating Curve= 0 ,0
Exp/Cntr=0.3,0.1

Type RM Length L Ch R = 1 ,28809.7 ,110.2,460.7,1407.7
BEGIN DESCRIPTION:
Cross Section 28809.7
END DESCRIPTION:
XS GIS Cut Line= 6
      3144598.77     13812304.33      3145420.47     13811218.24
      3145581.93     13810602.22      3145532.25      13810155.1
      3145795.98     13809485.64      3146400.78     13808792.34
#Sta/Elev= 30
  3340.1    33.8  3400.1    32.3  3890.1    32.7  4115.1    32.5  4170.1    31.7
  4220.1    32.5  4357.3    31.8  4577.3    29.1  4677.3    30.4    4712    28.4
    4822    28.7  4849.6   26.83    4898   16.51  4953.5    6.04  4973.8    -.65
  4994.2   -2.56  5022.7   -2.02  5030.8    1.29  5050.6    6.73  5141.4   26.16
    5152    24.1  5245.8    26.2  5305.8    26.8    5396    26.2    5456    28.1
  5578.9    29.3    6046    31.9  6895.5    32.3  6915.5    33.1  7430.5    33.7
#Mann= 3 , 1 , 0
  3340.1      .1       0  4849.6    .035       0  5141.4      .1       0
Bank Sta=4849.6,5141.4
XS Rating Curve= 0 ,0
Exp/Cntr=0.3,0.1

Type RM Length L Ch R = 1 ,28349.0 ,240,336.4,391.8
BEGIN DESCRIPTION:
Cross Section 28349.0 - Interpolated
END DESCRIPTION:
XS GIS Cut Line= 6
      3144607.31     13812313.81      3145340.18     13811393.46
        3145566.     13811107.99      3145825.91     13811099.47
      3146085.82      13810660.6      3146869.82     13810554.08
#Sta/Elev= 30
  2936.4   33.96  3006.4    32.4  3716.4    32.7  3786.4   31.69  4302.9   30.34
  4352.9   28.14  4826.4   27.59  4876.4   17.73    4909   13.27  4930.6    6.96
    4970    -.77  5006.2   -2.73  5030.4    -.92  5066.5    6.89  5118.8   16.03
  5187.4   26.15  5206.9   29.72    5247   29.74    5277   27.95    5317    18.3
    5347    8.09    5367     5.2    5387     7.9    5407   13.51    5437   19.17
    5487    25.7    5577   28.57    5847   30.03    5897    29.2  6038.2   32.97
#Mann= 5 , 1 , 0
  2936.4      .2       0  2936.4      .1       0  4826.4    .035       0
  5187.4      .1       0  6038.2      .2       0
Bank Sta=4826.4,5187.4
XS Rating Curve= 0 ,0
Exp/Cntr=0.5,0.3

Type RM Length L Ch R = 1 ,28012.6 ,115,115,115
BEGIN DESCRIPTION:
Upstream Section of Bridge/Culvert/Weir
END DESCRIPTION:
XS GIS Cut Line= 6
      3144616.42      13812284.5      3145602.52     13811119.12
       3145974.7     13811099.67      3146496.18     13810955.72
       3146549.9     13810821.13       3146818.1     13810582.72
#Sta/Elev= 30
  2836.5    33.9  2891.5      33  3111.5    33.1  3611.5    32.5    3648    31.5
    3863    31.8    4053    29.1    4143    29.7    4163    30.3  4199.3    30.3
  4269.3    28.2  4339.3    28.7 4747.99   27.56 4789.82   28.38 4849.66   27.47
 4892.96   17.61 4921.19   13.15  4939.8    6.84 4970.56     .57 4974.02    -.89
 4978.61     .46 5005.37   -2.85 5026.33   -1.04 5057.49    6.77 5102.88   15.91
 5162.29   26.03 5174.93   27.06  5440.1    29.7  5610.1      29  5781.5    32.7
#Mann= 4 , 1 , 0
  2836.5      .1       0 4849.66    .035       0 5162.29      .1       0
  5781.5      .2       0
#XS Ineff= 2 , 0
       0    4834   27.64    5186       0   27.69
Permanent Ineff=
       F       F
Bank Sta=4849.66,5162.29
XS Rating Curve= 0 ,0
Exp/Cntr=0.5,0.3