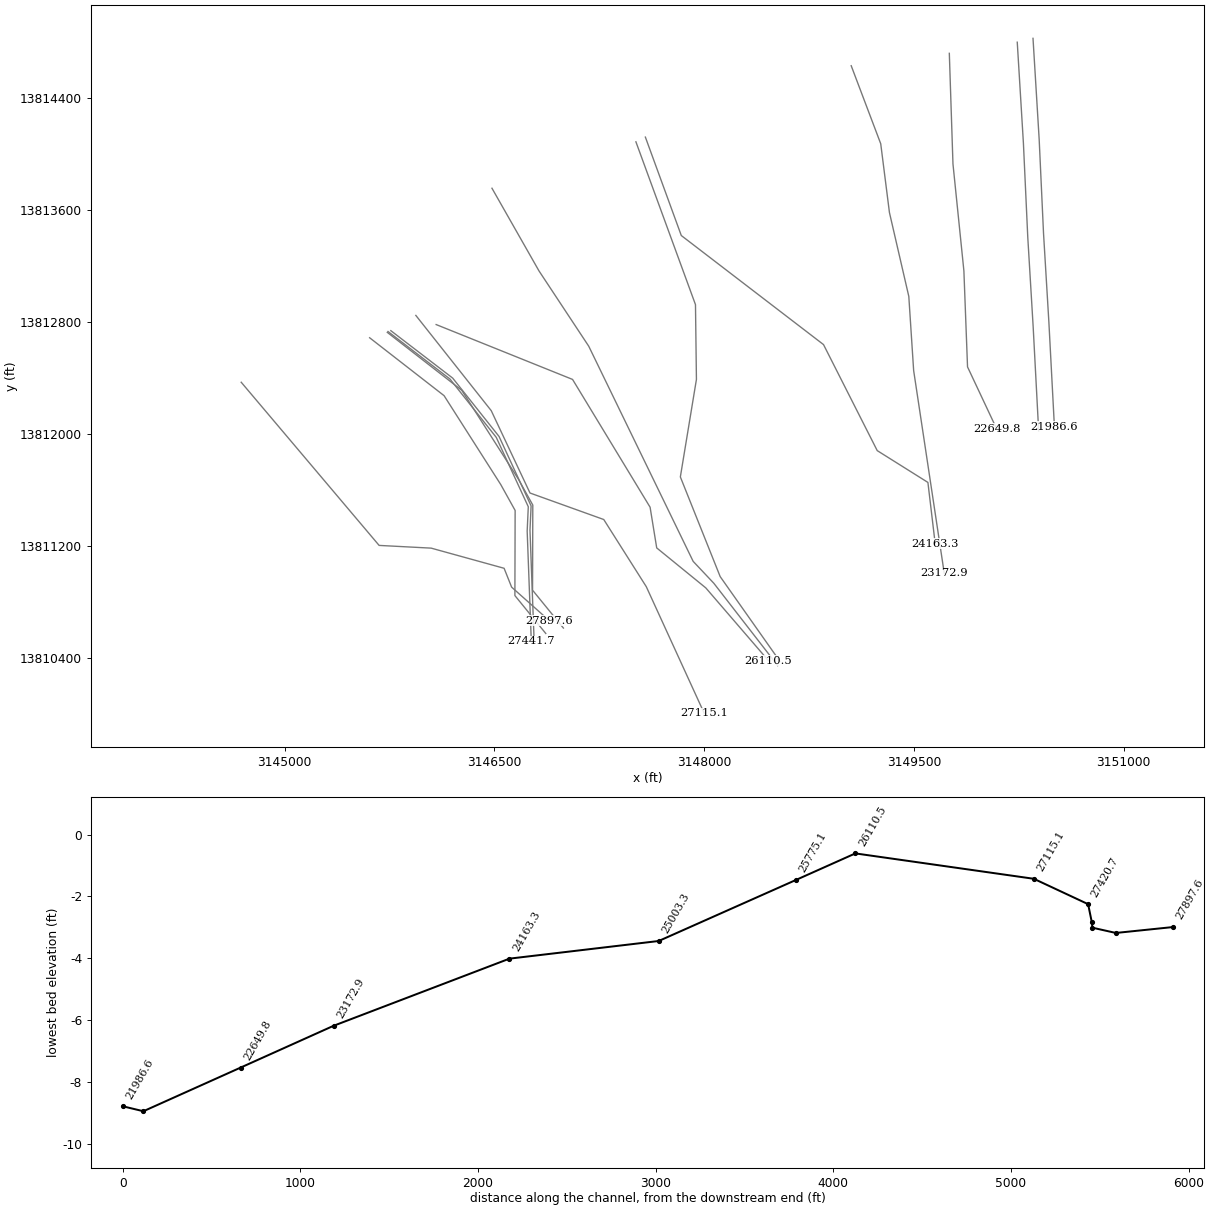
HEC-RAS study C100-00-00.prj: C100-00-00

--- C100-00-00.g01 (geometry) --- (continued)

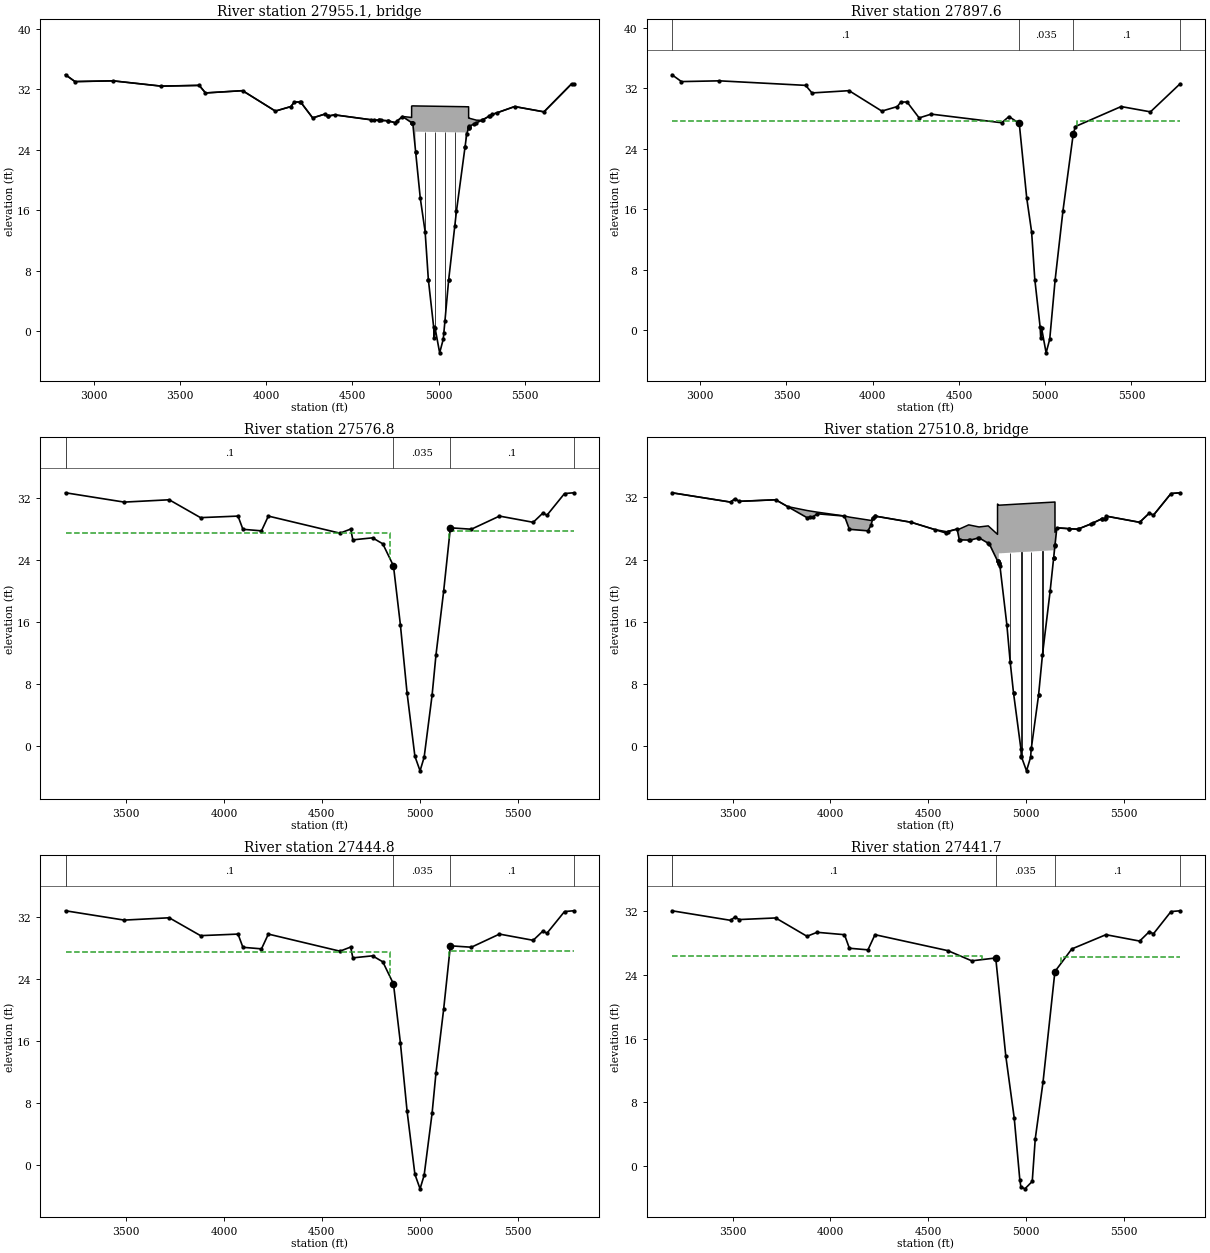
Type RM Length L Ch R = 3 ,27955.1 ,,,
BEGIN DESCRIPTION:
BELLFORT ROAD
Structure ID: C00-16
END DESCRIPTION:
Bridge Culvert--1,0,-1,-1, 0
Deck Dist Width WeirC Skew NumUp NumDn MinLoCord MaxHiCord MaxSubmerge Is_Ogee
10,95,2.6,0, 37, 37, , , 0.95, 0, 1,1,,
  2836.5  2891.5  3111.5  3391.5  3611.5    3648    3863    4053    4143    4163
  4199.3  4269.3  4339.3  4359.3  4396.5    4623  4705.3 4747.99 4789.82 4842.79
  4842.9 4849.66 4865.94 4866.03 5152.31 5152.42 5162.29  5173.3 5173.41 5174.93
 5218.92 5249.15 5311.59  5440.1  5610.1  5770.1  5781.5
    33.9      33    33.1    32.4    32.5    31.5    31.8    29.1    29.7    30.3
    30.3    28.2    28.7   28.49   28.61   27.91   27.83   27.57   28.39   28.26
   29.76   29.79   29.78   29.78   29.68   29.68   29.67   29.67   28.17   28.17
    27.9   27.88   28.67    29.7      29    32.7    32.7
    33.9      33    33.1    32.4    32.5    31.5    31.8    29.1    29.7    30.3
    30.3    28.2    28.7    28.4    28.6    27.9   27.82   27.56   28.38   27.57
   27.57   27.47   23.76   26.38   26.28   24.35   26.03   26.93   26.94   27.06
   27.56   27.87   28.66    29.7      29    32.7    32.7
  2836.5  2891.5  3111.5  3391.5  3611.5    3648    3863    4053    4143    4163
  4199.3  4269.3  4339.3  4359.3  4396.5    4623  4705.3 4747.99 4789.82 4842.79
  4842.9 4849.66 4865.94 4866.03 5152.31 5152.42 5162.29  5173.3 5173.41 5174.93
 5218.92 5249.15 5311.59  5440.1  5610.1  5770.1  5781.5
    33.9      33    33.1    32.4    32.5    31.5    31.8    29.1    29.7    30.3
    30.3    28.2    28.7   28.49   28.61   27.91   27.83   27.57   28.39   28.26
   29.76   29.79   29.78   29.78   29.68   29.68   29.67   29.67   28.17   28.17
    27.9   27.88   28.67    29.7      29    32.7    32.7
   33.77   32.87   32.97   32.27   32.37   31.37   31.67   28.97   29.57   30.17
   30.17   28.07   28.57   28.27   28.47   27.77   27.69   27.43   28.25   27.44
   27.44   27.34   23.63   26.25   26.15   24.22    25.9    26.8   26.81   26.93
   27.43   27.74   28.53   29.57   28.87   32.57   32.57
Pier Skew, UpSta & Num, DnSta & Num=  ,4921.2, 2 ,4921.2, 2 , 0 , 0 , 0 ,,
     1.4     1.4
   11.91   27.36
     1.4     1.4
   11.78   27.23
Pier Skew, UpSta & Num, DnSta & Num=  ,4978.7, 2 ,4978.7, 2 , 0 , 0 , 0 ,,
     1.4     1.4
    -.72   27.34
     1.4     1.4
    -.85   27.21
Pier Skew, UpSta & Num, DnSta & Num=  ,5036.1, 2 ,5036.1, 2 , 0 , 0 , 0 ,,
     1.4     1.4
     .22   27.32
     1.4     1.4
       9   27.19
Pier Skew, UpSta & Num, DnSta & Num=  ,5093.3, 2 ,5093.3, 2 , 0 , 0 , 0 ,,
     1.4     1.4
   12.81    27.3
     1.4     1.4
   12.68   27.17
Abutment Skew #Up #Dn= , 2 , 2
 4865.83  4939.9
   26.38    6.82
 4865.83  4939.9
   26.25    6.69
Abutment Skew #Up #Dn= , 2 , 2
 5057.59 5152.51
    6.79   26.28
 5057.59 5152.51
    6.66   26.15
BR Coef= 1 , 1 , 0 ,1.25, 0 ,,,0.8,-1,2,0,
WSPro=,,,, 1 ,,,, 0 ,,,, 0 ,,,,-1 ,-1 ,-1 , 0 , 0 , 0 , 0 , 0
BR U #Sta/Elev= 69
  2836.5    33.9  2891.5      33  3111.5    33.1  3391.5    32.4  3611.5    32.5
    3648    31.5    3863    31.8    4053    29.1    4143    29.7    4163    30.3
    4198    30.3  4199.3    30.3  4269.3    28.2  4339.3    28.7  4357.7   28.42
  4359.3    28.4  4396.5    28.6  4607.3   27.95    4623    27.9 4651.43   27.92
  4654.8   27.91 4663.65   27.89  4705.3   27.82  4706.2   27.81 4747.99   27.56
  4756.6   27.73 4789.82   28.38 4842.79   27.57  4842.9   27.57 4843.01   27.57
  4845.3   27.54 4849.66   27.47 4865.94   23.76 4866.03   23.74 4892.96   17.61
 4921.19   13.15  4939.8    6.84  4939.9    6.82 4970.56     .57 4974.02    -.89
 4978.61     .46 5005.37   -2.85 5026.33   -1.04 5029.53    -.24 5036.11    1.39
 5057.49    6.77 5057.59    6.79 5093.27   13.95 5102.88   15.91 5152.31   24.33
 5152.42   24.35 5162.29   26.03 5173.19   26.92  5173.3   26.93 5173.41   26.94
 5174.93   27.06    5176   27.07  5207.1   27.43 5218.92   27.56 5249.15   27.87
  5254.3   27.94  5289.8   28.39 5298.08    28.5 5311.59   28.66  5338.5   28.88
  5440.1    29.7  5610.1      29  5770.1    32.7  5781.5    32.7
BR U #Mann= 4
  2836.5      .1 4849.66    .035 5162.29      .1  5781.5      .2
BR U Banks=4849.66,5162.29
BR D #Sta/Elev= 69
  2836.5   33.77  2891.5   32.87  3111.5   32.97  3391.5   32.27  3611.5   32.37
    3648   31.37    3863   31.67    4053   28.97    4143   29.57    4163   30.17
    4198   30.17  4199.3   30.17  4269.3   28.07  4339.3   28.57  4357.7   28.29
  4359.3   28.27  4396.5   28.47  4607.3   27.82    4623   27.77 4651.43   27.79
  4654.8   27.78 4663.65   27.76  4705.3   27.69  4706.2   27.68 4747.99   27.43
  4756.6    27.6 4789.82   28.25 4842.79   27.44  4842.9   27.44 4843.01   27.44
  4845.3   27.41 4849.66   27.34 4865.94   23.63 4866.03   23.61 4892.96   17.48
 4921.19   13.02  4939.8    6.71  4939.9    6.69 4970.56     .44 4974.02   -1.02
 4978.61     .33 5005.37   -2.98 5026.33   -1.17 5029.53    -.37 5036.11    1.26
 5057.49    6.64 5057.59    6.66 5093.27   13.82 5102.88   15.78 5152.31    24.2
 5152.42   24.22 5162.29    25.9 5173.19   26.79  5173.3    26.8 5173.41   26.81
 5174.93   26.93    5176   26.94  5207.1    27.3 5218.92   27.43 5249.15   27.74
  5254.3   27.81  5289.8   28.26 5298.08   28.37 5311.59   28.53  5338.5   28.75
  5440.1   29.57  5610.1   28.87  5770.1   32.57  5781.5   32.57
BR D #Mann= 4
  2836.5      .1 4849.66    .035 5162.29      .1  5781.5      .2
BR D Banks=4849.66,5162.29
BC Design=,, 0 ,, 0 ,,,,,,
BC HTab HWMax=33.9
BC Use User HTab Curves=0
BC User HTab FreeFlow(D)= 0

Type RM Length L Ch R = 1 ,27897.6 ,320.8,320.8,320.8
BEGIN DESCRIPTION:
Downstream Section of Bridge/Culvert/Weir
END DESCRIPTION:
XS GIS Cut Line= 6
      3144690.33      13812372.6      3145676.42     13811207.22
       3146048.6     13811187.77      3146570.08     13811043.82
       3146623.8     13810909.23      3146892.01     13810670.83
#Sta/Elev= 30
  2836.5   33.76  2891.5   32.86  3111.5   32.96  3611.5   32.36    3648   31.36
    3863   31.66    4053   28.96    4143   29.56    4163   30.16  4199.3   30.16
  4269.3   28.06  4339.3   28.56 4747.99   27.42 4789.82   28.24 4849.66   27.33
 4892.96   17.47 4921.19   13.01  4939.8     6.7 4970.56     .43 4974.02   -1.03
 4978.61     .32 5005.37   -2.99 5026.33   -1.18 5057.49    6.63 5102.88   15.77
 5162.29   25.89 5174.93   26.92  5440.1   29.56  5610.1   28.86  5781.5   32.56
#Mann= 4 , 1 , 0
  2836.5      .1       0 4849.66    .035       0 5162.29      .1       0
  5781.5      .2       0
#XS Ineff= 2 , 0
       0    4834   27.64    5186       0   27.69
Permanent Ineff=
       F       F
Bank Sta=4849.66,5162.29
XS Rating Curve= 0 ,0
Exp/Cntr=0.5,0.3

Type RM Length L Ch R = 1 ,27576.8 ,132,132,132
BEGIN DESCRIPTION:
Upstream Section of Bridge/Culvert/Weir
END DESCRIPTION:
XS GIS Cut Line= 6
      3145608.65     13812690.33      3146140.96     13812276.65
      3146545.98     13811642.13        3146649.     13811456.87
      3146647.23     13810848.98      3146867.82     13810578.45
#Sta/Elev= 30
    3190   32.61    3490   31.41    3720   31.71    3880   29.41  4071.6   29.61
  4096.6   27.91  4191.6   27.71  4226.6   29.61  4592.5   27.41  4647.3   27.94
  4658.4   26.55  4759.1   26.81  4811.5   26.04    4866    23.2  4901.3   15.64
  4935.4    6.86  4975.5    -1.3  5001.9   -3.18  5022.8   -1.43  5063.4    6.55
  5083.2   11.72  5122.4   19.92  5156.8    28.1  5264.1   27.92  5407.7   29.61
  5580.1   28.81  5630.1   30.01  5650.1   29.71  5740.1   32.51  5786.3   32.61
#Mann= 5 , 1 , 0
    3190      .2       0    3190      .1       0    4866    .035       0
  5156.8      .1       0  5786.3      .2       0
#XS Ineff= 2 , 0
       0    4849   27.49    5151       0   27.66
Permanent Ineff=
       F       F
Bank Sta=4866,5156.8
XS Rating Curve= 0 ,0
Exp/Cntr=0.5,0.3

Type RM Length L Ch R = 3 ,27510.8 ,,,
BEGIN DESCRIPTION:
TELEPHONE ROAD
Structure ID: C00-15
END DESCRIPTION:
Bridge Culvert--1,0,-1,-1, 0
Deck Dist Width WeirC Skew NumUp NumDn MinLoCord MaxHiCord MaxSubmerge Is_Ogee
10,112,2.6,0, 45, 45, , , 0.95, 0, 1,1,,
    3190    3490    3510    3535    3720  3781.7    3880  3911.6  3931.6  4071.6
  4096.6  4191.6  4206.6  4216.6  4226.6  4412.5  4534.7  4592.5  4599.6  4647.3
  4658.4  4706.4  4759.1  4806.4  4811.5 4853.69  4853.8 4860.11  4860.2  4975.9
 5140.49  5140.6  5147.3 5147.41  5156.8  5264.1  5333.5  5387.6  5404.3  5407.7
  5580.1  5630.1  5650.1  5740.1  5786.3
    32.6    31.4    31.8    31.5    31.7   30.82   30.32   30.19   30.11   29.61
   29.47    29.1   29.04   29.31   29.61   28.81   27.86    27.6   27.63   27.94
   27.93   28.47    28.2   28.34   28.22   27.25   31.15      31      31   31.17
    31.4    31.4   31.41   27.51    28.1   27.92   28.62   29.27   29.34    29.6
    28.8      30    29.7    32.5    32.6
    32.6    31.4    31.8    31.5    31.7   30.81    29.4    29.5    29.9    29.6
    27.9    27.7    28.4    29.3    29.6    28.8   27.85    27.4    27.6   27.93
   26.54   26.51    26.8    26.1   26.03   23.83   23.83    23.5    24.8   24.97
    25.2   24.24   25.83   25.86   28.09   27.91   28.61   29.26   29.17    29.6
    28.8      30    29.7    32.5    32.6
    3190    3490    3510    3535    3720  3781.7    3880  3911.6  3931.6  4071.6
  4096.6  4191.6  4206.6  4216.6  4226.6  4412.5  4534.7  4592.5  4599.6  4647.3
  4658.4  4706.4  4759.1  4806.4  4811.5 4853.69  4853.8 4860.11  4860.2  4975.9
 5140.49  5140.6  5147.3 5147.41  5156.8  5264.1  5333.5  5387.6  5404.3  5407.7
  5580.1  5630.1  5650.1  5740.1  5786.3
    32.6    31.4    31.8    31.5    31.7   30.82   30.32   30.19   30.11   29.61
   29.47    29.1   29.04   29.31   29.61   28.81   27.86    27.6   27.63   27.94
   27.93   28.47    28.2   28.34   28.22   27.25   31.15      31      31   31.17
    31.4    31.4   31.41   27.51    28.1   27.92   28.62   29.27   29.34    29.6
    28.8      30    29.7    32.5    32.6
   32.22   31.02   31.42   31.12   31.32   30.43   29.02   29.12   29.52   29.22
   27.52   27.32   28.02   28.92   29.22   28.42   27.47   27.02   27.22   27.55
   26.16   26.13   26.42   25.72   25.65   23.45   23.45   23.12   24.42   24.59
   24.82   23.86   25.45   25.48   27.71   27.53   28.23   28.88   28.79   29.22
   28.42   29.62   29.32   32.12   32.22
Pier Skew, UpSta & Num, DnSta & Num=  ,4918.3, 2 ,4918.3, 2 , 0 , 0 , 0 ,,
       2       2
    9.62   25.88
       2       2
    9.24    25.5
Pier Skew, UpSta & Num, DnSta & Num=  ,4975.9, 2 ,4975.9, 2 , 0 , 0 , 0 ,,
       2       2
   -2.45   25.97
       2       2
   -2.83   25.59
Pier Skew, UpSta & Num, DnSta & Num=  ,5025.8, 2 ,5025.8, 2 , 0 , 0 , 0 ,,
       2       2
   -1.75   26.04
       2       2
   -2.13   25.66
Pier Skew, UpSta & Num, DnSta & Num=  ,5083.2, 2 ,5083.2, 2 , 0 , 0 , 0 ,,
       2       2
   10.45   26.12
       2       2
   10.07   25.74
Abutment Skew #Up #Dn= , 2 , 2
    4860  4935.5
    24.8    6.83
    4860  4935.5
   24.42    6.45
Abutment Skew #Up #Dn= , 2 , 2
  5063.5 5140.69
    6.57    25.2
  5063.5 5140.69
    6.19   24.82
BR Coef= 1 , 1 , 0 ,1.25, 0 ,,,0.8,-1,2,0,
WSPro=,,,, 1 ,,,, 0 ,,,, 0 ,,,,-1 ,-1 ,-1 , 0 , 0 , 0 , 0 , 0
BR U #Sta/Elev= 76
    3190    32.6    3490    31.4    3510    31.8    3535    31.5    3720    31.7
  3781.7   30.81    3880    29.4  3896.6    29.5  3911.6    29.5  3931.6    29.9
  4071.6    29.6  4096.6    27.9  4191.6    27.7  4206.6    28.4  4216.6    29.3
  4216.7    29.3  4226.6    29.6  4227.5    29.6  4412.5    28.8  4534.7   27.85
  4592.5    27.4  4599.6    27.6  4647.3   27.93  4658.4   26.54  4661.7   26.54
  4706.4   26.51  4713.5    26.5  4754.2   26.77  4759.1    26.8  4806.4    26.1
  4811.5   26.03 4853.69   23.83  4853.8   23.83 4853.91   23.82    4860    23.5
 4860.11    23.5  4860.2   23.49    4866   23.19  4901.3   15.63  4918.3   10.85
  4935.4    6.85  4935.5    6.83  4973.2    -.36  4975.5   -1.31  4975.9   -1.38
  5001.9   -3.19  5022.8   -1.44  5025.8     -.4  5026.8    -.21  5063.4    6.54
  5063.5    6.57  5083.2   11.71  5122.4   19.91 5140.49   24.21  5140.6   24.24
  5140.7   24.26 5147.19    25.8  5147.3   25.83 5147.41   25.86  5156.8   28.09
    5220   27.96  5220.1   27.96  5264.1   27.91  5268.1   27.95  5333.5   28.61
  5341.3    28.7  5387.6   29.26  5387.9   29.26  5404.3   29.17  5405.7   29.35
  5407.7    29.6  5580.1    28.8  5630.1      30  5650.1    29.7  5740.1    32.5
  5786.3    32.6
BR U #Mann= 5
    3190      .2    3190      .1    4866    .035  5156.8      .1  5786.3      .2
BR U Banks=4866,5156.8
BR D #Sta/Elev= 76
    3190   32.22    3490   31.02    3510   31.42    3535   31.12    3720   31.32
  3781.7   30.43    3880   29.02  3896.6   29.12  3911.6   29.12  3931.6   29.52
  4071.6   29.22  4096.6   27.52  4191.6   27.32  4206.6   28.02  4216.6   28.92
  4216.7   28.92  4226.6   29.22  4227.5   29.22  4412.5   28.42  4534.7   27.47
  4592.5   27.02  4599.6   27.22  4647.3   27.55  4658.4   26.16  4661.7   26.16
  4706.4   26.13  4713.5   26.12  4754.2   26.39  4759.1   26.42  4806.4   25.72
  4811.5   25.65 4853.69   23.45  4853.8   23.45 4853.91   23.44    4860   23.12
 4860.11   23.12  4860.2   23.11    4866   22.81  4901.3   15.25  4918.3   10.47
  4935.4    6.47  4935.5    6.45  4973.2    -.74  4975.5   -1.69  4975.9   -1.76
  5001.9   -3.57  5022.8   -1.82  5025.8    -.78  5026.8    -.59  5063.4    6.16
  5063.5    6.19  5083.2   11.33  5122.4   19.53 5140.49   23.83  5140.6   23.86
  5140.7   23.88 5147.19   25.42  5147.3   25.45 5147.41   25.48  5156.8   27.71
    5220   27.58  5220.1   27.58  5264.1   27.53  5268.1   27.57  5333.5   28.23
  5341.3   28.32  5387.6   28.88  5387.9   28.88  5404.3   28.79  5405.7   28.97
  5407.7   29.22  5580.1   28.42  5630.1   29.62  5650.1   29.32  5740.1   32.12
  5786.3   32.22
BR D #Mann= 5
    3190      .2    3190      .1    4866    .035  5156.8      .1  5786.3      .2
BR D Banks=4866,5156.8
BC Design=,, 0 ,, 0 ,,,,,,
BC HTab HWMax=32.61
BC Use User HTab Curves=0
BC User HTab FreeFlow(D)= 0

Type RM Length L Ch R = 1 ,27444.8 ,3.1,3.1,3.1
BEGIN DESCRIPTION:
Downstream Section of Bridge/Culvert/Weir
END DESCRIPTION:
XS GIS Cut Line= 6
       3145734.9     13812728.84      3146267.22     13812315.17
      3146672.24     13811680.65      3146775.26     13811495.39
      3146773.49      13810887.5      3146994.07     13810616.97
#Sta/Elev= 30
    3190   32.78    3490   31.58    3720   31.88    3880   29.58  4071.6   29.78
  4096.6   28.08  4191.6   27.88  4226.6   29.78  4592.5   27.58  4647.3   28.11
  4658.4   26.72  4759.1   26.98  4811.5   26.21    4866   23.37  4901.3   15.81
  4935.4    7.03  4975.5   -1.13  5001.9   -3.01  5022.8   -1.26  5063.4    6.72
  5083.2   11.89  5122.4   20.09  5156.8   28.27  5264.1   28.09  5407.7   29.78
  5580.1   28.98  5630.1   30.18  5650.1   29.88  5740.1   32.68  5786.3   32.78
#Mann= 5 , 1 , 0
    3190      .2       0    3190      .1       0    4866    .035       0
  5156.8      .1       0  5786.3      .2       0
#XS Ineff= 2 , 0
       0    4849   27.49    5151       0   27.66
Permanent Ineff=
       F       F
Bank Sta=4866,5156.8
XS Rating Curve= 0 ,0
Exp/Cntr=0.5,0.3

Type RM Length L Ch R = 1 ,27441.7 ,21,21,21
BEGIN DESCRIPTION:
Upstream Section of Bridge/Culvert/Weir
END DESCRIPTION:
XS GIS Cut Line= 6
      3145740.13     13812734.81      3146182.44     13812396.03
      3146514.01     13811979.01      3146743.02     13811483.37
      3146735.07     13811309.45      3146764.47      13810523.7
#Sta/Elev= 30
    3190   32.04    3490   30.84    3510   31.24    3535   30.94    3720   31.14
    3880   28.84  3931.6   29.34  4071.6   29.04  4096.6   27.34  4191.6   27.14
  4227.5   29.04  4599.6   27.04  4722.2   25.76  4844.5   26.12    4896   13.81
  4939.2    6.01  4967.5   -1.67    4973   -2.59  4993.5   -2.84  5031.1   -1.91
  5046.5    3.43  5086.3   10.56    5147   24.42  5233.2   27.25  5407.7   29.04
  5580.1   28.24  5630.1   29.44  5650.1   29.14  5740.1   31.94  5786.3   32.04
#Mann= 5 , 1 , 0
    3190      .2       0    3190      .1       0  4844.5    .035       0
    5147      .1       0  5786.3      .2       0
#XS Ineff= 2 , 0
       0    4772    26.4    5179       0    26.2
Permanent Ineff=
       F       F
Bank Sta=4844.5,5147
XS Rating Curve= 0 ,0
Exp/Cntr=0.5,0.3

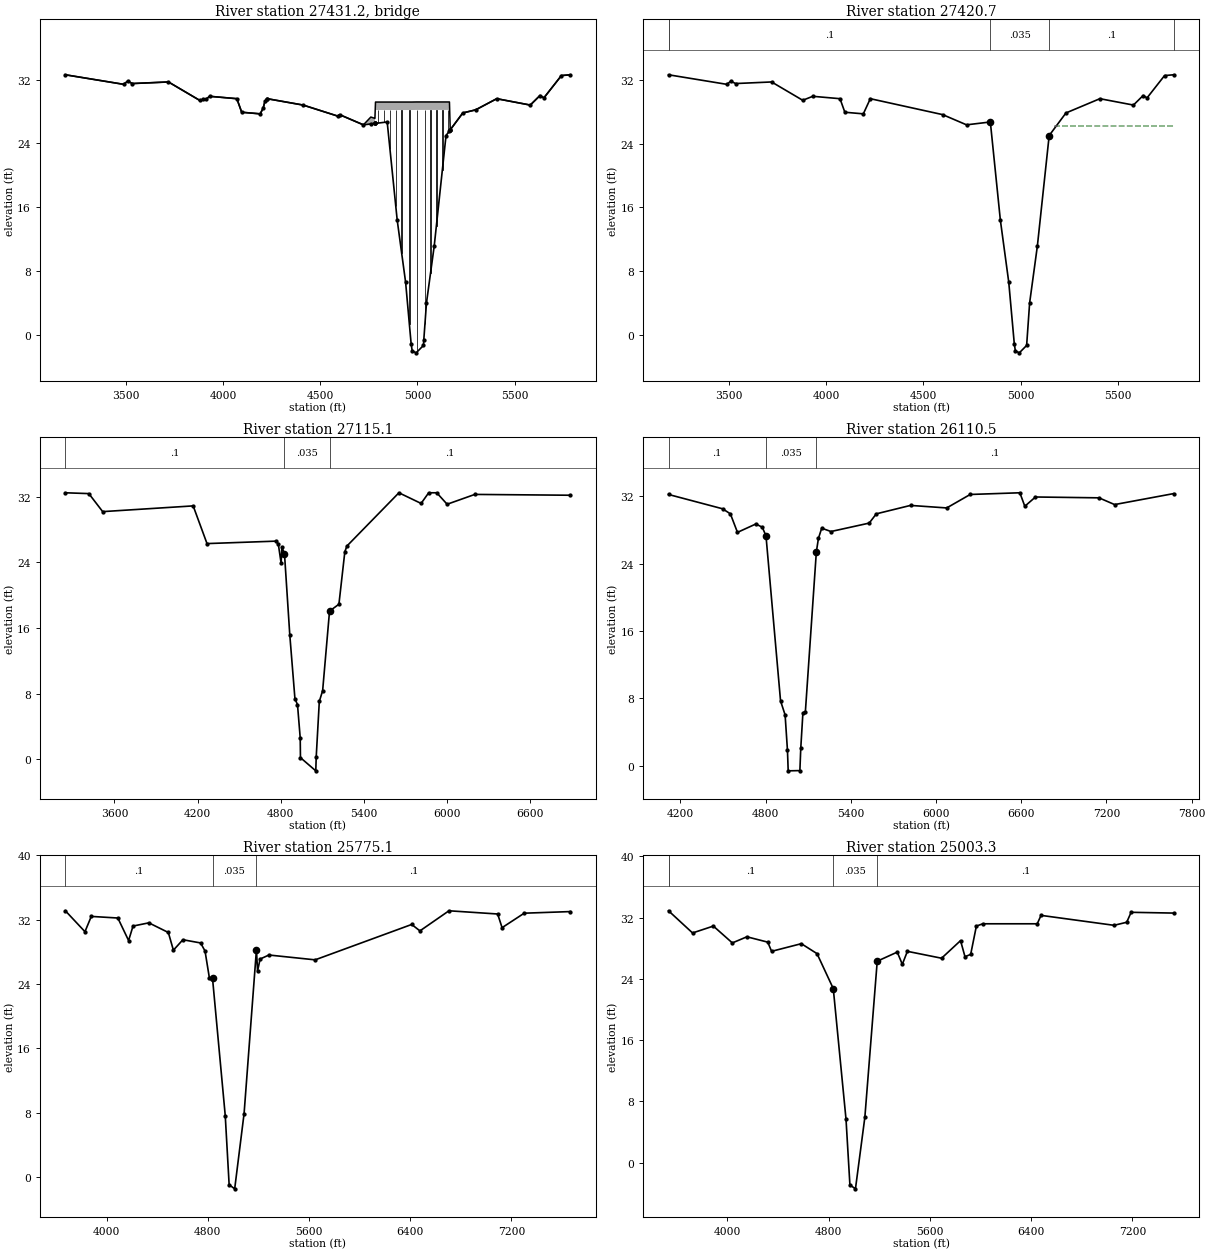
Type RM Length L Ch R = 3 ,27431.2 ,,,
BEGIN DESCRIPTION:
12" DIA. PIPE DS OF TELEPHONE RD
END DESCRIPTION:
Bridge Culvert--1,0,-1,-1, 0
Deck Dist Width WeirC Skew NumUp NumDn MinLoCord MaxHiCord MaxSubmerge Is_Ogee
10,1,2.6,0, 48, 48, , , 0.95, 0, 1,1,,
    3190    3490    3510    3535    3720    3880  3896.6  3911.6  3931.6  4071.6
  4096.6  4191.6  4206.6  4216.6  4226.6  4227.5  4412.5  4592.5  4599.6  4722.2
  4760.4  4781.4 4781.51  4781.6  4784.4  4844.5    4896  4939.2  4967.5    4973
  4993.5  5031.1  5032.5  5046.5  5086.3    5147  5164.6 5168.29  5168.4  5168.5
  5233.2  5299.3  5407.7  5580.1  5630.1  5650.1  5740.1  5786.3
    32.6    31.4    31.8    31.5    31.7    29.4    29.5    29.5    29.9    29.6
    27.9    27.7    28.4    29.3    29.6    29.6    28.8    27.4    27.6   26.32
    27.3   27.13   27.21   27.27   29.18   29.18   29.18   29.18   29.18   29.18
   29.19   29.19   29.19   29.19   29.19   29.19   29.19   25.97   25.87   25.69
   27.81    28.2    29.6    28.8      30    29.7    32.5    32.6
    32.6    31.4    31.8    31.5    31.7    29.4    29.5    29.5    29.9    29.6
    27.9    27.7    28.4    29.3    29.6    29.6    28.8    27.4    27.6   26.32
   26.43   26.49   26.49   26.49   28.18   28.18   28.18   28.18   28.18   28.18
   28.19   28.19   28.19   28.19   28.19   28.19   28.19   25.68   25.68   25.69
   27.81    28.2    29.6    28.8      30    29.7    32.5    32.6
    3190    3490    3510    3535    3720    3880  3896.6  3911.6  3931.6  4071.6
  4096.6  4191.6  4206.6  4216.6  4226.6  4227.5  4412.5  4592.5  4599.6  4722.2
  4760.4  4781.4 4781.51  4781.6  4784.4  4844.5    4896  4939.2  4967.5    4973
  4993.5  5031.1  5032.5  5046.5  5086.3    5147  5164.6 5168.29  5168.4  5168.5
  5233.2  5299.3  5407.7  5580.1  5630.1  5650.1  5740.1  5786.3
    32.6    31.4    31.8    31.5    31.7    29.4    29.5    29.5    29.9    29.6
    27.9    27.7    28.4    29.3    29.6    29.6    28.8    27.4    27.6   26.32
    27.3   27.13   27.21   27.27   29.18   29.18   29.18   29.18   29.18   29.18
   29.19   29.19   29.19   29.19   29.19   29.19   29.19   25.97   25.87   25.69
   27.81    28.2    29.6    28.8      30    29.7    32.5    32.6
    32.6    31.4    31.8    31.5    31.7    29.4    29.5    29.5    29.9    29.6
    27.9    27.7    28.4    29.3    29.6    29.6    28.8    27.4    27.6   26.32
   26.43   26.49   26.49   26.49   28.18   28.18   28.18   28.18   28.18   28.18
   28.19   28.19   28.19   28.19   28.19   28.19   28.19   25.68   25.68   25.69
   27.81    28.2    29.6    28.8      30    29.7    32.5    32.6
Pier Skew, UpSta & Num, DnSta & Num=  ,4797.9, 2 ,4797.9, 2 , 0 , 0 , 0 ,,
     1.4     1.4
   25.54   29.18
     1.4     1.4
   25.54   29.18
Pier Skew, UpSta & Num, DnSta & Num=  ,4828.5, 2 ,4828.5, 2 , 0 , 0 , 0 ,,
     1.4     1.4
   25.63   29.18
     1.4     1.4
   25.63   29.18
Pier Skew, UpSta & Num, DnSta & Num=  ,4858.5, 2 ,4858.5, 2 , 0 , 0 , 0 ,,
     1.4     1.4
   22.17   29.18
     1.4     1.4
   22.17   29.18
Pier Skew, UpSta & Num, DnSta & Num=  ,4888.5, 2 ,4888.5, 2 , 0 , 0 , 0 ,,
     1.4     1.4
      15   29.18
     1.4     1.4
      15   29.18
Pier Skew, UpSta & Num, DnSta & Num=  ,4918.7, 2 ,4918.7, 2 , 0 , 0 , 0 ,,
     1.4     1.4
    9.15   29.18
     1.4     1.4
    9.15   29.18
Pier Skew, UpSta & Num, DnSta & Num=  ,4958.7, 2 ,4958.7, 2 , 0 , 0 , 0 ,,
     1.4     1.4
       9   29.18
     1.4     1.4
       9   29.18
Pier Skew, UpSta & Num, DnSta & Num=  ,4998.1, 2 ,4998.1, 2 , 0 , 0 , 0 ,,
     1.4     1.4
   -3.18   29.19
     1.4     1.4
   -3.18   29.19
Pier Skew, UpSta & Num, DnSta & Num=  ,5038.8, 2 ,5038.8, 2 , 0 , 0 , 0 ,,
     1.4     1.4
     .16   29.19
     1.4     1.4
     .16   29.19
Pier Skew, UpSta & Num, DnSta & Num=  ,5067.6, 2 ,5067.6, 2 , 0 , 0 , 0 ,,
     1.4     1.4
    6.64   29.19
     1.4     1.4
    6.64   29.19
Pier Skew, UpSta & Num, DnSta & Num=  ,5097.5, 2 ,5097.5, 2 , 0 , 0 , 0 ,,
     1.4     1.4
   12.52   29.19
     1.4     1.4
   12.52   29.19
Pier Skew, UpSta & Num, DnSta & Num=  ,5128.2, 2 ,5128.2, 2 , 0 , 0 , 0 ,,
     1.4     1.4
   19.53   29.19
     1.4     1.4
   19.53   29.19
Pier Skew, UpSta & Num, DnSta & Num=  ,5158.1, 2 ,5158.1, 2 , 0 , 0 , 0 ,,
     1.4     1.4
   24.32   29.19
     1.4     1.4
   24.32   29.19
BR Coef= 1 , 1 , 0 ,1.25, 0 ,,,0.8,0,2,0,
WSPro=,,,, 1 ,,,, 0 ,,,, 0 ,,,,-1 ,-1 ,-1 , 0 , 0 , 0 , 0 , 0
BR U #Sta/Elev= 48
    3190    32.6    3490    31.4    3510    31.8    3535    31.5    3720    31.7
    3880    29.4  3896.6    29.5  3911.6    29.5  3931.6    29.9  4071.6    29.6
  4096.6    27.9  4191.6    27.7  4206.6    28.4  4216.6    29.3  4226.6    29.6
  4227.5    29.6  4412.5    28.8  4592.5    27.4  4599.6    27.6  4722.2   26.32
  4760.4   26.43  4781.4   26.49 4781.51   26.49  4781.6   26.49  4784.4    26.5
  4844.5   26.68    4896   14.37  4939.2    6.57  4967.5   -1.11    4973   -2.03
  4993.5   -2.28  5031.1   -1.35  5032.5    -.73  5046.5    3.99  5086.3   11.12
    5147   24.98  5164.6   25.56 5168.29   25.68  5168.4   25.68  5168.5   25.69
  5233.2   27.81  5299.3    28.2  5407.7    29.6  5580.1    28.8  5630.1      30
  5650.1    29.7  5740.1    32.5  5786.3    32.6
BR U #Mann= 5
    3190      .2    3190      .1  4844.5    .035    5147      .1  5786.3      .2
BR U Banks=4844.5,5147
BR D #Sta/Elev= 48
    3190    32.6    3490    31.4    3510    31.8    3535    31.5    3720    31.7
    3880    29.4  3896.6    29.5  3911.6    29.5  3931.6    29.9  4071.6    29.6
  4096.6    27.9  4191.6    27.7  4206.6    28.4  4216.6    29.3  4226.6    29.6
  4227.5    29.6  4412.5    28.8  4592.5    27.4  4599.6    27.6  4722.2   26.32
  4760.4   26.43  4781.4   26.49 4781.51   26.49  4781.6   26.49  4784.4    26.5
  4844.5   26.68    4896   14.37  4939.2    6.57  4967.5   -1.11    4973   -2.03
  4993.5   -2.28  5031.1   -1.35  5032.5    -.73  5046.5    3.99  5086.3   11.12
    5147   24.98  5164.6   25.56 5168.29   25.68  5168.4   25.68  5168.5   25.69
  5233.2   27.81  5299.3    28.2  5407.7    29.6  5580.1    28.8  5630.1      30
  5650.1    29.7  5740.1    32.5  5786.3    32.6
BR D #Mann= 5
    3190      .2    3190      .1  4844.5    .035    5147      .1  5786.3      .2
BR D Banks=4844.5,5147
BC Design=,, 0 ,, 0 ,,,,,,
BC HTab HWMax=32.04
BC Use User HTab Curves=0
BC User HTab FreeFlow(D)= 0

Type RM Length L Ch R = 1 ,27420.7 ,305.6,305.6,305.6
BEGIN DESCRIPTION:
Downstream Section of Bridge/Culvert/Weir
END DESCRIPTION:
XS GIS Cut Line= 6
      3145760.22     13812740.94      3146202.52     13812402.15
      3146534.09     13811985.13       3146763.1     13811489.49
      3146755.15     13811315.57      3146784.56     13810529.83
#Sta/Elev= 30
    3190   32.63    3490   31.43    3510   31.83    3535   31.53    3720   31.73
    3880   29.43  3931.6   29.93  4071.6   29.63  4096.6   27.93  4191.6   27.73
  4227.5   29.63  4599.6   27.63  4722.2   26.35  4844.5   26.71    4896    14.4
  4939.2     6.6  4967.5   -1.08    4973      -2  4993.5   -2.25  5031.1   -1.32
  5046.5    4.02  5086.3   11.15    5147   25.01  5233.2   27.84  5407.7   29.63
  5580.1   28.83  5630.1   30.03  5650.1   29.73  5740.1   32.53  5786.3   32.63
#Mann= 5 , 1 , 0
    3190      .2       0    3190      .1       0  4844.5    .035       0
    5147      .1       0  5786.3      .2       0
#XS Ineff= 2 , 0
       0    4772    26.4    5179       0    26.2
Permanent Ineff=
       F       F
Bank Sta=4844.5,5147
XS Rating Curve= 0 ,0
Exp/Cntr=0.5,0.3

Type RM Length L Ch R = 1 ,27115.1 ,1001.3,1004.6,1011.9
BEGIN DESCRIPTION:
Cross Section 27115.1
END DESCRIPTION:
XS GIS Cut Line= 6
      3145939.09     13812849.76      3146478.13     13812169.61
      3146755.33     13811581.41      3147282.68      13811392.1
      3147586.92     13810912.08      3148001.29     13810007.55
#Sta/Elev= 30
  3245.5    32.5    3415    32.4    3515    30.2  4168.4    30.9  4268.4    26.3
  4768.6    26.6  4783.6    26.2  4803.6    23.9  4808.9   25.88  4827.9   25.04
  4866.1   15.16  4903.3    7.37  4921.8    6.65  4941.4    2.59  4943.1     .18
  5053.8   -1.43    5057     .28  5079.3    7.04  5103.3    8.35  5153.1   18.06
  5220.9    18.9  5263.6    25.3  5278.6      26  5654.2    32.5  5814.2    31.2
  5869.2    32.5  5927.3    32.5  6002.3    31.1  6202.3    32.3  6892.3    32.2
#Mann= 3 , 1 , 0
  3245.5      .1       0  4827.9    .035       0  5153.1      .1       0
Bank Sta=4827.9,5153.1
XS Rating Curve= 0 ,0
Exp/Cntr=0.3,0.1

Type RM Length L Ch R = 1 ,26110.5 ,439.9,335.4,225.5
BEGIN DESCRIPTION:
Cross Section 26110.5
END DESCRIPTION:
XS GIS Cut Line= 6
      3146084.28     13812784.54      3147059.57     13812392.72
      3147613.96       13811480.      3147661.29     13811189.28
      3148012.25     13810903.75      3148459.58     13810384.96
#Sta/Elev= 30
  4115.6    32.2  4496.3    30.5  4551.3    29.9  4601.3    27.7  4731.3    28.7
  4776.3    28.3  4802.1   27.29  4904.7    7.69  4936.8    6.03  4953.4    1.81
  4958.5    -.61  5040.8    -.58  5047.1    2.08  5062.1    6.26  5079.5     6.4
  5156.7   25.37  5171.4   26.98  5194.6    28.2  5259.6    27.8    5529    28.8
    5579    29.9  5819.9    30.9  6074.9    30.6  6240.4    32.2    6590    32.4
    6625    30.8    6700    31.9  7147.4    31.8  7257.4      31  7672.4    32.3
#Mann= 3 , 1 , 0
  4115.6      .1       0  4802.1    .035       0  5156.7      .1       0
Bank Sta=4802.1,5156.7
XS Rating Curve= 0 ,0
Exp/Cntr=0.3,0.1

Type RM Length L Ch R = 1 ,25775.1 ,873.5,771.8,692.2
BEGIN DESCRIPTION:
Cross Section 25775.1-Interpolated
END DESCRIPTION:
XS GIS Cut Line= 6
      3146483.33     13813758.22      3146819.45     13813167.95
      3147175.35     13812629.76      3147921.88      13811093.3
      3148069.45     13810937.05      3148526.31     13810348.67
#Sta/Elev= 30
  3674.1    33.1  3829.1    30.5  3879.1    32.4  4089.1    32.2  4174.1    29.4
  4209.1    31.2  4334.1    31.6  4488.3    30.4  4528.3    28.2  4603.3    29.5
  4743.3    29.1  4778.3    28.1  4813.3    24.7  4837.6    24.7  4938.2    7.63
    4969    -.96  5012.8   -1.47  5087.1    7.89  5184.8   28.28  5193.6    25.6
  5213.6    27.1  5283.6    27.6  5648.8      27  6412.3    31.4  6477.3    30.6
  6706.9    33.1  7091.8    32.7  7126.8      31  7301.8    32.8  7666.8      33
#Mann= 3 , 1 , 0
  3674.1      .1       0  4837.6    .035       0  5184.8      .1       0
Bank Sta=4837.6,5184.8
XS Rating Curve= 0 ,0
Exp/Cntr=0.3,0.1

Type RM Length L Ch R = 1 ,25003.3 ,689.2,840,1086.3
BEGIN DESCRIPTION:
Cross Section 25003.3
END DESCRIPTION:
XS GIS Cut Line= 6
      3147512.55     13814089.71      3147938.49     13812926.83
      3147945.25     13812392.72      3147830.31     13811696.35
      3148115.06     13810984.47      3148541.68     13810379.85
#Sta/Elev= 30
    3536    32.9    3726      30  3890.2    30.9  4040.2    28.7  4155.2    29.5
  4320.2    28.8  4350.2    27.6  4585.2    28.6  4709.1    27.3  4837.6   22.73
  4938.2    5.66    4969   -2.93  5012.8   -3.44  5087.1    5.92  5184.8   26.31
    5343    27.5    5383    25.9    5423    27.6    5693    26.7    5843      29
    5878    26.9    5923    27.2    5968    30.9  6018.8    31.2  6448.8    31.2
  6478.8    32.3  7055.5      31  7155.5    31.4  7190.5    32.7  7525.5    32.6
#Mann= 4 , 1 , 0
    3536      .2       0    3536      .1       0  4837.6    .035       0
  5184.8      .1       0
Bank Sta=4837.6,5184.8
XS Rating Curve= 0 ,0
Exp/Cntr=0.3,0.1

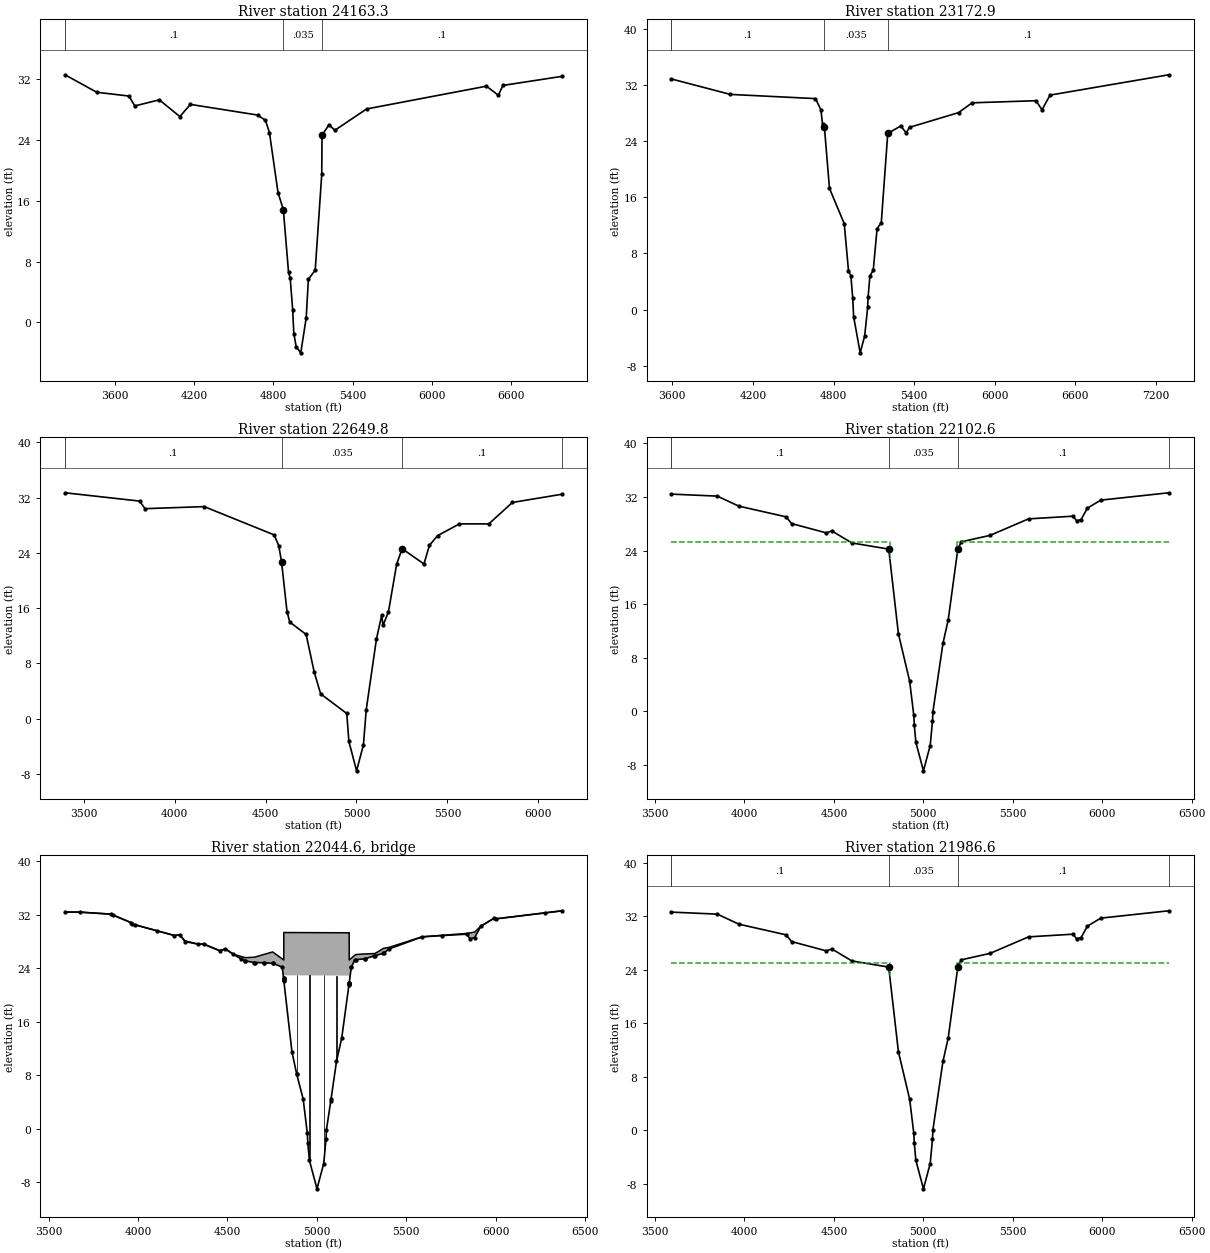
Type RM Length L Ch R = 1 ,24163.3 ,1117.9,990.4,884.7
BEGIN DESCRIPTION:
Cross Section 24163.3
END DESCRIPTION:
XS GIS Cut Line= 6
      3147580.16     13814123.52      3147837.07     13813420.38
      3148853.92     13812641.52      3149237.94      13811884.3
      3149600.32     13811657.13      3149652.34     13811220.22
#Sta/Elev= 30
  3224.5    32.6  3464.5    30.3  3708.1    29.8  3753.1    28.5  3938.1    29.3
  4093.6    27.1  4173.6    28.7  4681.2    27.3  4741.2    26.6  4771.2      25
  4836.2    17.1  4876.6   14.84  4915.7     6.6  4928.4    5.83    4947    1.69
  4955.7   -1.47    4974   -3.22  5008.3   -4.01  5049.4     .58  5065.9    5.68
  5117.6    6.87  5167.1    19.5    5169   24.64  5221.2      26  5266.9    25.3
  5506.5    28.1  6413.1    31.1  6503.1    29.9  6538.1    31.2  6987.3    32.4
#Mann= 4 , 1 , 0
  3224.5      .2       0  3224.5      .1       0  4876.6    .035       0
    5169      .1       0
Bank Sta=4876.6,5169
XS Rating Curve= 0 ,0
Exp/Cntr=0.3,0.1

Type RM Length L Ch R = 1 ,23172.9 ,484.9,523.1,483.1
BEGIN DESCRIPTION:
Cross Section 23172.9
END DESCRIPTION:
XS GIS Cut Line= 6
      3149051.88     13814633.24      3149263.03     13814075.92
      3149325.34     13813584.37      3149463.81     13812985.52
      3149498.42     13812455.89      3149717.07      13811009.2
#Sta/Elev= 30
  3593.8    32.9  4032.1    30.7  4665.7    30.1  4706.2    28.5  4718.2   26.46
  4731.9    26.1    4770   17.29  4879.7   12.26  4911.5    5.55  4929.1    4.82
  4942.8    1.69  4949.8   -1.02  4998.4   -6.18  5031.8   -3.79  5054.2     .32
  5057.2    1.74  5070.8    4.81  5095.6    5.59  5124.2   11.53  5155.5   12.41
  5203.7   25.13  5300.8    26.2  5340.8    25.2  5365.8      26  5730.8    28.1
  5831.6    29.5  6306.6    29.8  6351.6    28.5  6411.6    30.6  7295.5    33.5
#Mann= 4 , 1 , 0
  3593.8      .2       0  3593.8      .1       0  4731.9    .035       0
  5203.7      .1       0
Bank Sta=4731.9,5203.7
XS Rating Curve= 0 ,0
Exp/Cntr=0.3,0.1

Type RM Length L Ch R = 1 ,22649.8 ,494,547.2,604.8
BEGIN DESCRIPTION:
Cross Section 22649.8-Interpolated
END DESCRIPTION:
XS GIS Cut Line= 5
      3149753.48     13814721.77      3149779.52     13813931.84
      3149857.64     13813167.95      3149883.69     13812482.19
      3150092.02     13812039.48
#Sta/Elev= 30
  3397.7    32.7  3807.7    31.5  3837.7    30.4  4162.7    30.7  4548.1    26.6
  4573.1      25  4588.1    22.7  4618.1    15.5  4633.1      14  4723.1    12.2
  4768.1     6.7  4803.1     3.6  4946.5     .77  4958.2   -3.28  5000.5   -7.53
  5038.2   -3.75  5053.5    1.31  5109.6   11.53  5138.7   14.99  5145.9    13.5
  5175.9    15.5  5220.9    22.4  5250.9    24.6  5370.9    22.4  5400.9    25.1
  5445.9    26.5  5565.9    28.2  5727.2    28.2  5857.2    31.3  6131.5    32.5
#Mann= 5 , 1 , 0
  3397.7      .2       0  3397.7      .1       0  4588.1    .035       0
  5250.9      .1       0  6131.5      .2       0
Bank Sta=4588.1,5250.9
XS Rating Curve= 0 ,0
Exp/Cntr=0.5,0.3

Type RM Length L Ch R = 1 ,22102.6 ,116,116,116
BEGIN DESCRIPTION:
Upstream Section of Bridge/Culvert/Weir
END DESCRIPTION:
XS GIS Cut Line= 5
      3150239.17     13814801.31      3150283.25     13814079.45
      3150314.41      13813407.9      3150352.79      13812771.4
      3150392.33     13812024.88
#Sta/Elev= 30
  3591.6   32.43    3848   32.13  3968.4   30.63    4233   29.03    4263   28.03
    4458   26.63    4488   26.93  4600.2   25.13  4806.4   24.21  4860.6   11.54
  4923.3    4.48  4946.5    -.64  4949.4   -2.15  4958.2   -4.69  5000.5   -8.94
  5038.2   -5.16    5051   -1.51  5053.5     -.1  5109.6   10.12  5138.7   13.58
  5192.4   24.17  5212.1    25.3  5372.8   26.26    5588   28.73  5836.9   29.13
  5856.9   28.43  5881.9   28.63  5916.9   30.33  5991.9   31.53  6372.3   32.63
#Mann= 5 , 1 , 0
  3591.6      .2       0  3591.6      .1       0  4806.4    .035       0
  5192.4      .1       0  6372.3      .2       0
#XS Ineff= 2 , 0
       0    4813   25.29    5189       0   25.29
Permanent Ineff=
       F       F
Bank Sta=4806.4,5192.4
XS Rating Curve= 0 ,0
Exp/Cntr=0.5,0.3

Type RM Length L Ch R = 3 ,22044.6 ,,,
BEGIN DESCRIPTION:
BROADWAY BLVD
Structure ID: C00-14
END DESCRIPTION:
Bridge Culvert--1,0,-1,-1, 0
Deck Dist Width WeirC Skew NumUp NumDn MinLoCord MaxHiCord MaxSubmerge Is_Ogee
10,96,2.6,0, 41, 41, , , 0.95, 0, 1,1,,
  3591.6  3673.1    3848    3963  3968.4    4203    4233    4263    4338    4368
    4458    4488    4533  4577.3  4600.2  4651.2  4752.7  4806.4 4813.61  4813.7
 4814.79  4814.9 5179.29  5179.4  5180.6 5180.71  5192.5  5212.1  5216.8  5270.8
  5324.7  5372.2  5402.3    5588  5836.9  5856.9  5881.9  5916.9  5991.9  6003.7
  6372.3
    32.4    32.4    32.1   30.81   30.61   28.91   29.01    28.1   27.61   27.61
   26.65   26.91   26.11   25.76   25.59   25.66   26.45    25.4   25.25   25.25
   25.25   29.35   29.31   29.31   29.34   25.24   25.51   25.95   26.06   26.15
   26.21   26.98   27.12   28.71   29.21    29.3   29.42   30.31   31.51   31.41
    32.6
    32.4    32.4    32.1    30.8    30.6    28.9      29      28    27.6    27.6
    26.6    26.9    26.1   25.38    25.1   24.86   24.74   24.18   22.49   22.95
   22.95   22.95   22.91   21.58   21.81   21.83   24.16   25.27   25.28   25.43
    25.9   26.23   26.88    28.7    29.1    28.4    28.6    30.3    31.5    31.4
    32.6
  3591.6  3673.1    3848    3963  3968.4    4203    4233    4263    4338    4368
    4458    4488    4533  4577.3  4600.2  4651.2  4752.7  4806.4 4813.61  4813.7
 4814.79  4814.9 5179.29  5179.4  5180.6 5180.71  5192.5  5212.1  5216.8  5270.8
  5324.7  5372.2  5402.3    5588  5836.9  5856.9  5881.9  5916.9  5991.9  6003.7
  6372.3
   32.57   32.57   32.27   30.97   30.77   29.07   29.17   28.17   27.77   27.77
   26.77   27.07   26.27   25.76   25.59   25.66   26.45    25.4   25.25   25.25
   25.25   29.35   29.31   29.31   29.34   25.24   25.51   25.95   26.06   26.15
   26.21   26.98   27.12   28.87   29.27    29.3   29.42   30.47   31.67   31.57
   32.77
   32.57   32.57   32.27   30.97   30.77   29.07   29.17   28.17   27.77   27.77
   26.77   27.07   26.27   25.55   25.27   25.03   24.91   24.35   22.66   23.12
   23.12   23.12   23.08   21.75   21.98      22   24.33   25.44   25.45    25.6
   26.07    26.4   27.05   28.87   29.27   28.57   28.77   30.47   31.67   31.57
   32.77
Pier Skew, UpSta & Num, DnSta & Num=  ,4886.8, 2 ,4886.8, 2 , 0 , 0 , 0 ,,
     1.4     1.4
    7.15   23.94
     1.4     1.4
    7.32   24.11
Pier Skew, UpSta & Num, DnSta & Num=  ,4958.2, 2 ,4958.2, 2 , 0 , 0 , 0 ,,
     1.4     1.4
   -5.79   23.93
     1.4     1.4
   -5.62    24.1
Pier Skew, UpSta & Num, DnSta & Num=  ,5038.2, 2 ,5038.2, 2 , 0 , 0 , 0 ,,
     1.4     1.4
   -6.26   23.93
     1.4     1.4
   -6.09    24.1
Pier Skew, UpSta & Num, DnSta & Num=  ,5109.6, 2 ,5109.6, 2 , 0 , 0 , 0 ,,
     1.4     1.4
    8.96   23.92
     1.4     1.4
    9.13   24.09
Abutment Skew #Up #Dn= , 2 , 2
  4813.5  4887.6
   22.95    8.14
  4813.5  4887.6
   23.12    8.31
Abutment Skew #Up #Dn= , 2 , 2
  5077.6 5179.49
    4.17   22.91
  5077.6 5179.49
    4.34   23.08
BR Coef= 1 , 1 , 0 ,1.25, 0 ,,,0.8,-1,2,0,
WSPro=,,,, 1 ,,,, 0 ,,,, 0 ,,,,-1 ,-1 ,-1 , 0 , 0 , 0 , 0 , 0
BR U #Sta/Elev= 74
  3591.6    32.4  3673.1    32.4    3848    32.1  3860.5   31.96    3963    30.8
  3968.4    30.6  3983.4    30.5    4108    29.6    4203    28.9    4233      29
    4263      28    4338    27.6    4368    27.6    4458    26.6    4488    26.9
    4533    26.1  4577.3   25.38  4600.2    25.1  4600.4    25.1  4651.1   24.86
  4651.2   24.86  4703.9   24.83    4705   24.83  4752.7   24.74  4754.3   24.72
  4806.4   24.18  4813.5   22.52 4813.61   22.49  4813.7   22.47 4814.79   22.22
  4814.9   22.19 4815.01   22.17  4860.6   11.51  4886.8    8.22  4887.6    8.14
  4923.3    4.45  4946.5    -.67  4949.4   -2.18  4958.2   -4.72  5000.5   -8.97
  5038.2   -5.19    5051   -1.54  5053.5    -.13  5077.6    4.17  5079.3    4.47
  5109.6   10.09  5138.7   13.55 5179.29   21.55  5179.4   21.58  5179.5    21.6
 5180.49   21.79  5180.6   21.81 5180.71   21.83  5192.4   24.14  5192.5   24.16
  5212.1   25.27  5216.8   25.28  5270.4   25.43  5270.8   25.43  5321.3   25.88
  5324.7    25.9  5372.2   26.23  5372.8   26.23  5402.3   26.88    5588    28.7
  5701.9    28.9  5836.9    29.1  5856.9    28.4  5881.9    28.6  5916.9    30.3
  5991.9    31.5  6003.7    31.4  6273.4   32.28  6372.3    32.6
BR U #Mann= 5
  3591.6      .2  3591.6      .1  4806.4    .035  5192.4      .1  6372.3      .2
BR U Banks=4806.4,5192.4
BR D #Sta/Elev= 74
  3591.6   32.57  3673.1   32.57    3848   32.27  3860.5   32.13    3963   30.97
  3968.4   30.77  3983.4   30.67    4108   29.77    4203   29.07    4233   29.17
    4263   28.17    4338   27.77    4368   27.77    4458   26.77    4488   27.07
    4533   26.27  4577.3   25.55  4600.2   25.27  4600.4   25.27  4651.1   25.03
  4651.2   25.03  4703.9      25    4705      25  4752.7   24.91  4754.3   24.89
  4806.4   24.35  4813.5   22.69 4813.61   22.66  4813.7   22.64 4814.79   22.39
  4814.9   22.36 4815.01   22.34  4860.6   11.68  4886.8    8.39  4887.6    8.31
  4923.3    4.62  4946.5     -.5  4949.4   -2.01  4958.2   -4.55  5000.5    -8.8
  5038.2   -5.02    5051   -1.37  5053.5     .04  5077.6    4.34  5079.3    4.64
  5109.6   10.26  5138.7   13.72 5179.29   21.72  5179.4   21.75  5179.5   21.77
 5180.49   21.96  5180.6   21.98 5180.71      22  5192.4   24.31  5192.5   24.33
  5212.1   25.44  5216.8   25.45  5270.4    25.6  5270.8    25.6  5321.3   26.05
  5324.7   26.07  5372.2    26.4  5372.8    26.4  5402.3   27.05    5588   28.87
  5701.9   29.07  5836.9   29.27  5856.9   28.57  5881.9   28.77  5916.9   30.47
  5991.9   31.67  6003.7   31.57  6273.4   32.45  6372.3   32.77
BR D #Mann= 5
  3591.6      .2  3591.6      .1  4806.4    .035  5192.4      .1  6372.3      .2
BR D Banks=4806.4,5192.4
BC Design=,, 0 ,, 0 ,,,,,,
BC HTab HWMax=32.63
BC Use User HTab Curves=0
BC User HTab FreeFlow(D)= 0

Type RM Length L Ch R = 1 ,21986.6 ,851.4,851.4,851.4
BEGIN DESCRIPTION:
Downstream Section of Bridge/Culvert/Weir
END DESCRIPTION:
XS GIS Cut Line= 5
      3150351.85     13814828.88      3150395.93     13814107.01
      3150427.09     13813435.46      3150465.47     13812798.96
      3150505.01     13812052.45
#Sta/Elev= 30
  3591.6   32.59    3848   32.29  3968.4   30.79    4233   29.19    4263   28.19
    4458   26.79    4488   27.09  4600.2   25.29  4806.4   24.37  4860.6    11.7
  4923.3    4.64  4946.5    -.48  4949.4   -1.99  4958.2   -4.53  5000.5   -8.78
  5038.2      -5    5051   -1.35  5053.5     .06  5109.6   10.28  5138.7   13.74
  5192.4   24.33  5212.1   25.46  5372.8   26.42    5588   28.89  5836.9   29.29
  5856.9   28.59  5881.9   28.79  5916.9   30.49  5991.9   31.69  6372.3   32.79
#Mann= 5 , 1 , 0
  3591.6      .2       0  3591.6      .1       0  4806.4    .035       0
  5192.4      .1       0  6372.3      .2       0
#XS Ineff= 2 , 0
       0    4813   24.95    5189       0   24.95
Permanent Ineff=
       F       F
Bank Sta=4806.4,5192.4
XS Rating Curve= 0 ,0
Exp/Cntr=0.5,0.3