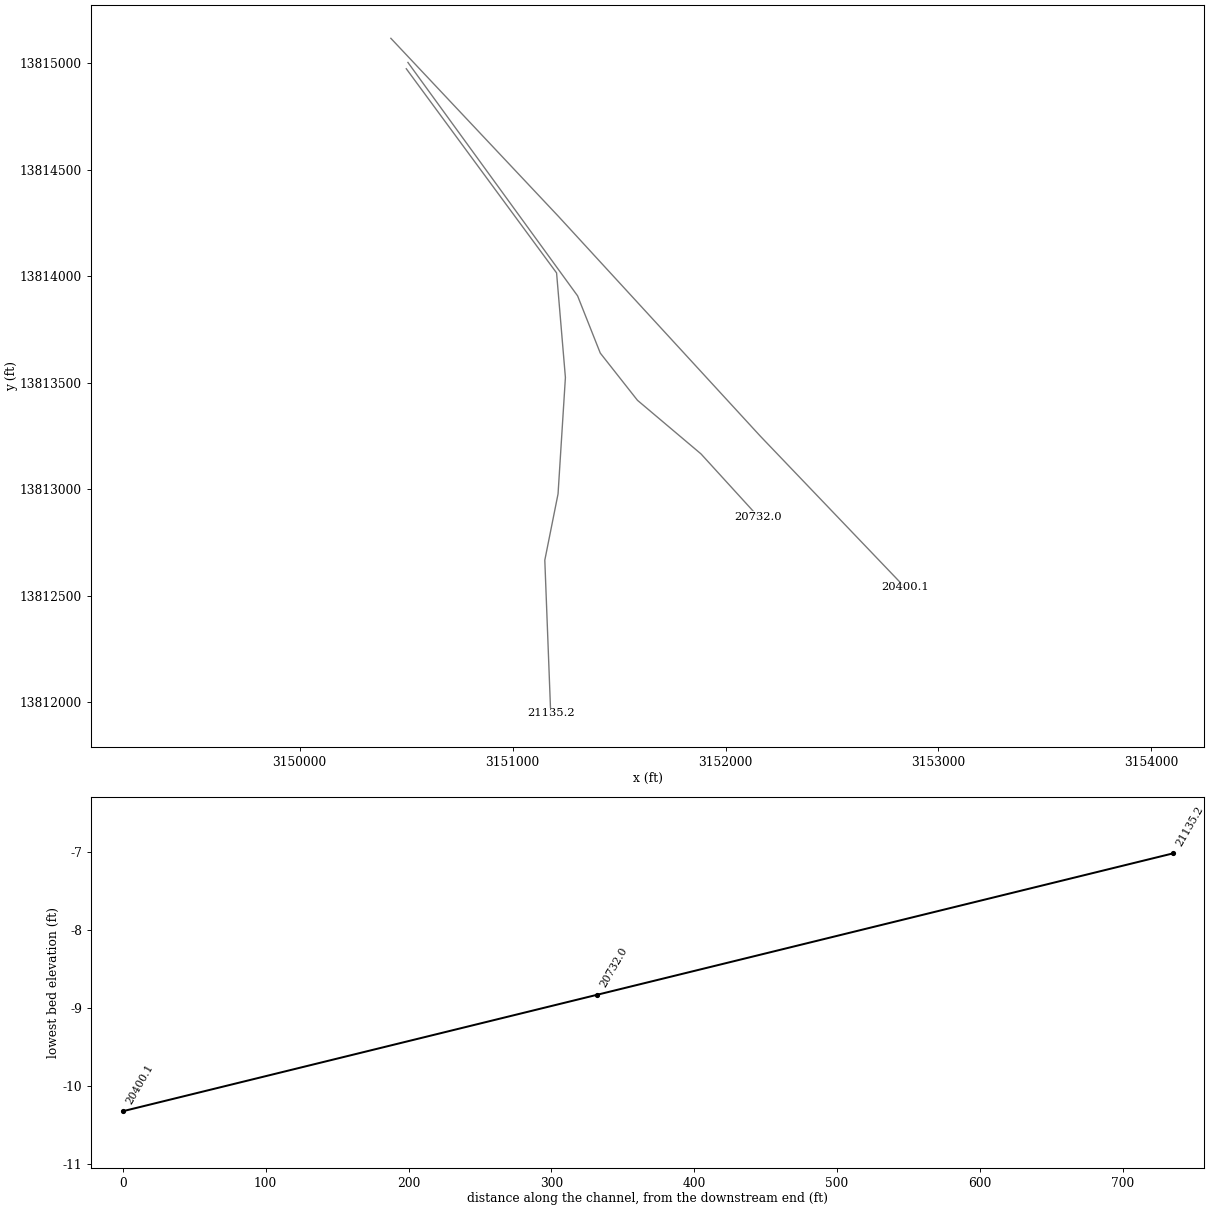
HEC-RAS study C100-00-00.prj: C100-00-00

--- C100-00-00.g01 (geometry) --- (continued)

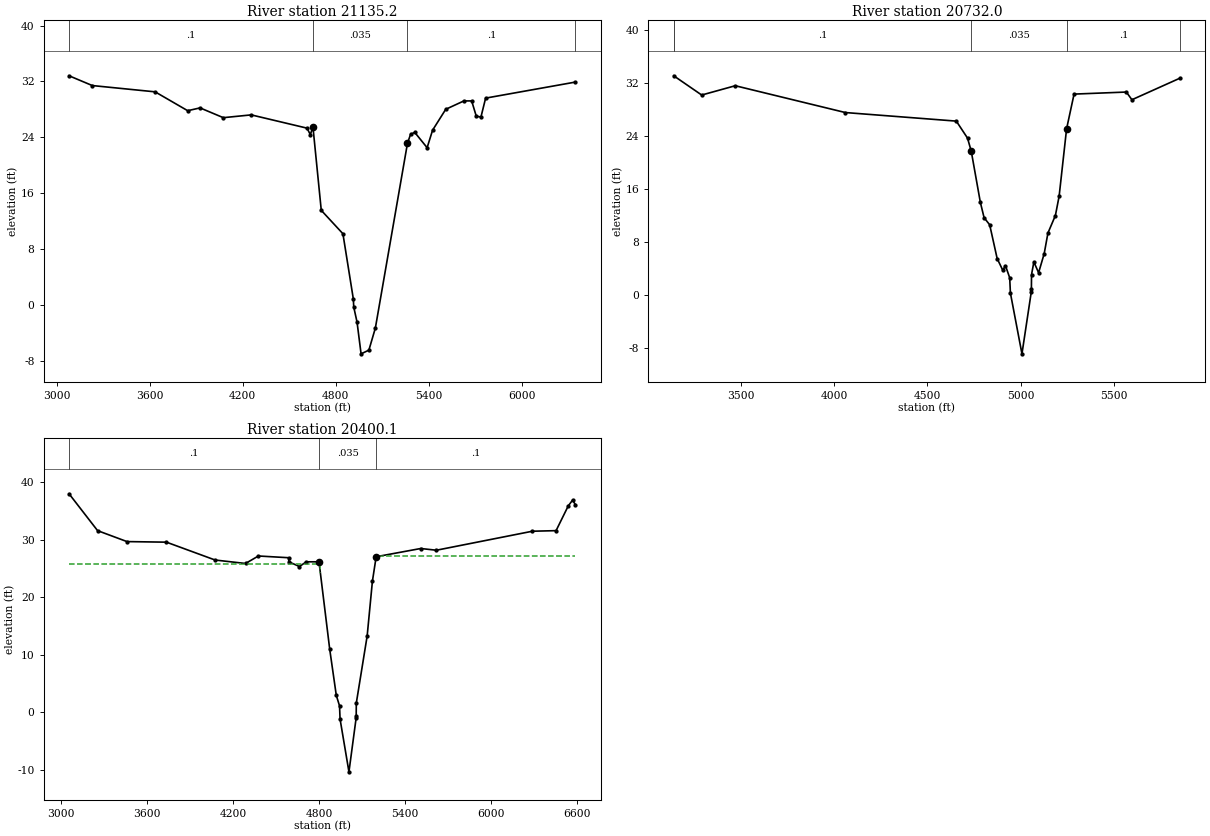
Type RM Length L Ch R = 1 ,21135.2 ,169,403.2,752.7
BEGIN DESCRIPTION:
Cross Section 21135.2
END DESCRIPTION:
XS GIS Cut Line= 6
      3150500.85      13814972.9      3151206.67       13814015.
      3151248.14     13813524.32      3151213.58     13812978.35
      3151151.38     13812667.35      3151179.03     13811948.61
#Sta/Elev= 30
  3080.2    32.8  3230.2    31.4  3635.2    30.5  3845.2    27.8  3925.2    28.2
  4075.2    26.8  4255.2    27.2    4615    25.3  4636.2   24.37  4653.1   25.49
  4706.8   13.53  4846.4   10.18  4913.5     .85  4916.4    -.34  4937.5   -2.47
  4963.5   -7.02  5013.9   -6.49  5055.7   -3.32  5262.8   23.14  5282.5    24.4
  5309.5    24.7  5389.5    22.5  5424.5      25  5509.5      28  5626.7    29.2
  5676.7    29.2  5706.7      27  5736.7    26.9  5766.7    29.6    6346    31.9
#Mann= 4 , 1 , 0
  3080.2      .1       0  4653.1    .035       0  5262.8      .1       0
    6346      .2       0
Bank Sta=4653.1,5262.8
XS Rating Curve= 0 ,0
Exp/Cntr=0.3,0.1

Type RM Length L Ch R = 1 ,20732.0 ,285.8,331.9,316.6
BEGIN DESCRIPTION:
Cross Section 20732.0 - Interpolated
END DESCRIPTION:
XS GIS Cut Line= 6
      3150508.57     13815002.39      3151305.35     13813907.36
      3151411.87     13813638.93      3151586.56     13813417.36
      3151884.82     13813165.97      3152153.25     13812871.97
#Sta/Elev= 30
  3141.1   33.06  3291.1   30.16  3471.1   31.56  4061.1   27.52  4655.5   26.23
  4715.5   23.67  4735.5    21.7  4784.3   13.99  4804.3   11.68  4834.3   10.61
  4874.3    5.53  4904.3    3.77    4919    4.45  4941.6    2.62  4945.3     .33
  5007.2   -8.83    5057     .46  5057.8     .87  5058.5     3.1    5071    5.01
  5096.4    3.39  5126.4    6.27  5146.4    9.37  5186.4   12.01  5206.4   14.92
  5246.4   25.07  5286.4    30.3  5566.5   30.61  5596.5   29.45  5854.6   32.71
#Mann= 5 , 1 , 0
  3141.1      .2       0  3141.1      .1       0  4735.5    .035       0
  5246.4      .1       0  5854.6      .2       0
Bank Sta=4735.5,5246.4
XS Rating Curve= 0 ,0
Exp/Cntr=0.5,0.3

Type RM Length L Ch R = 1 ,20400.1 ,297,297,297
BEGIN DESCRIPTION:
Upstream Section of Bridge/Culvert/Weir
END DESCRIPTION:
XS GIS Cut Line= 4
      3150428.46     13815115.58      3151216.31     13814279.35
      3152163.12     13813249.61      3152842.13     13812540.42
#Sta/Elev= 30
  3056.3   37.95  3255.2   31.55  3460.2   29.65  3735.2   29.55  4074.5   26.45
  4286.2   25.85  4376.2   27.15  4586.2   26.85  4588.6   26.14  4662.3   25.32
  4709.7   26.14  4798.6   26.14  4873.1   10.97    4919    2.96  4941.6    1.13
  4945.3   -1.16  5007.2  -10.32    5057   -1.03  5057.8    -.62  5058.5    1.61
  5134.2   13.27  5170.7   22.76  5196.9   27.02  5507.8   28.45  5616.6   28.15
  6285.9   31.45  6450.9   31.55  6535.9   35.85  6565.9   36.85  6585.9   36.05
#Mann= 3 , 1 , 0
  3056.3      .1       0  4798.6    .035       0  5196.9      .1       0
#XS Ineff= 2 , 0
       0    4808   25.69    5208       0   27.22
Permanent Ineff=
       F       F
Bank Sta=4798.6,5196.9
XS Rating Curve= 0 ,0
Exp/Cntr=0.5,0.3