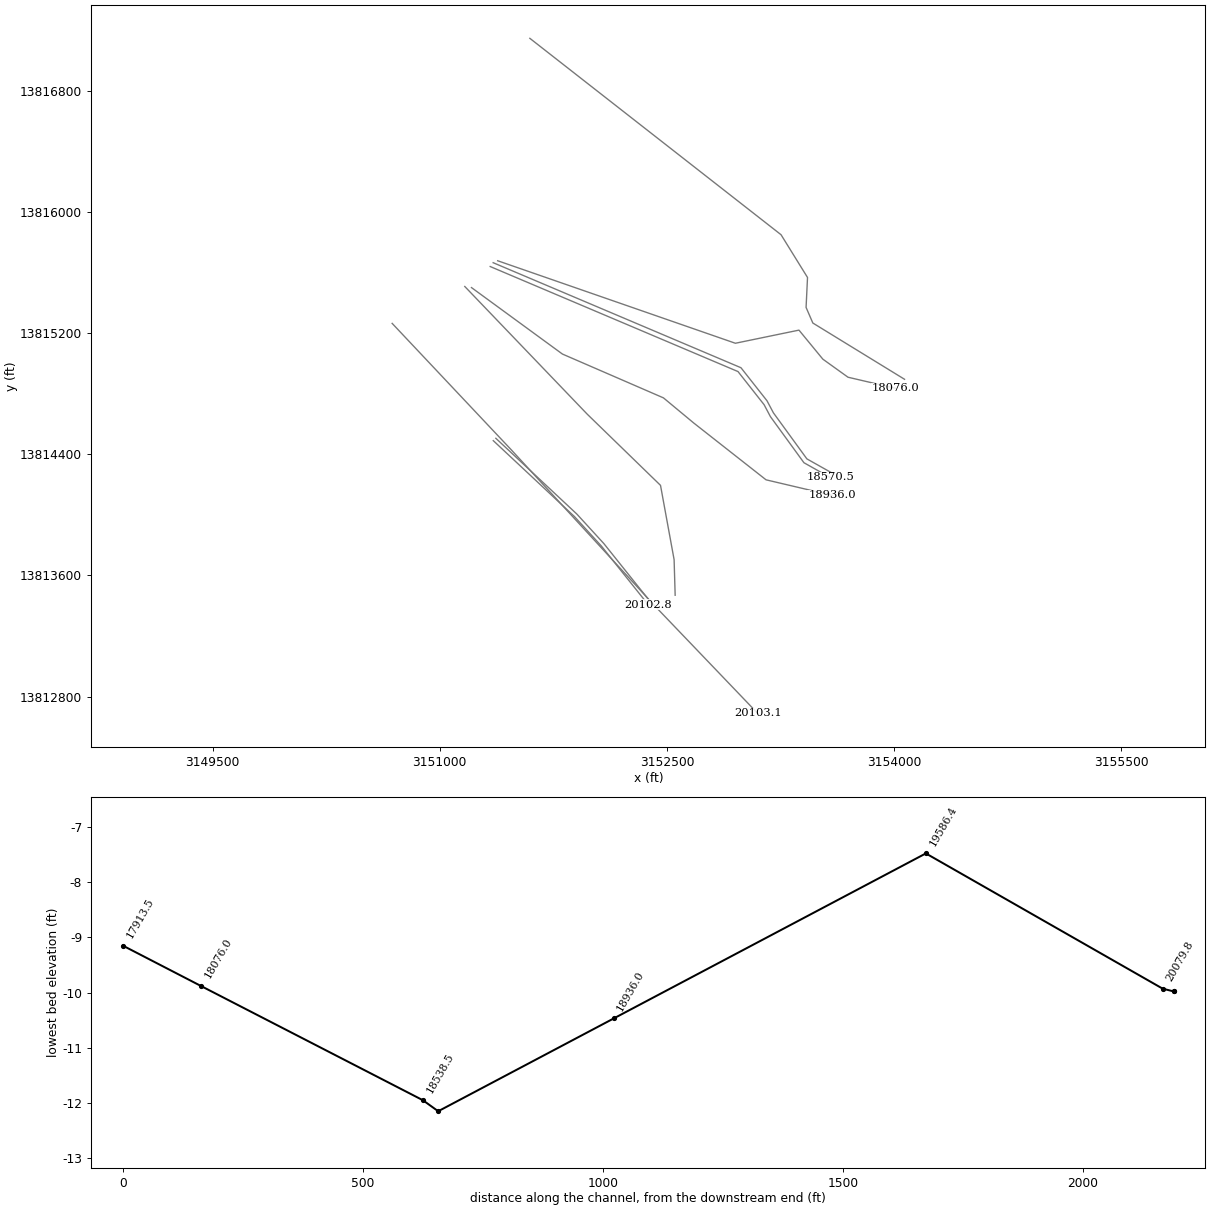
HEC-RAS study C100-00-00.prj: C100-00-00

--- C100-00-00.g01 (geometry) --- (continued)

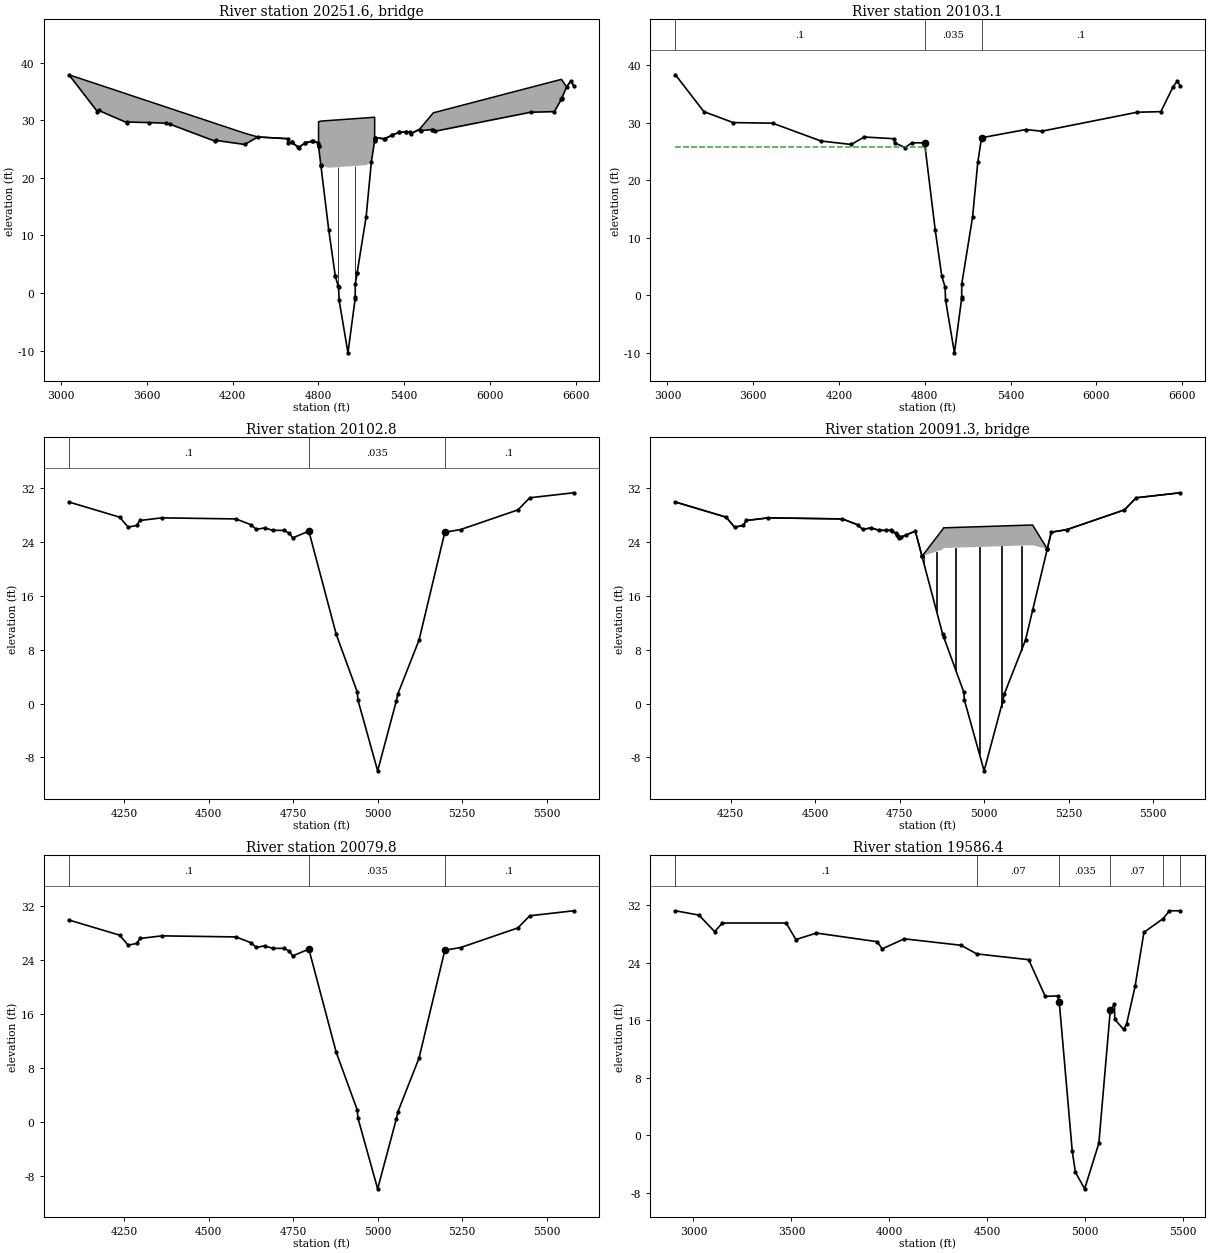
Type RM Length L Ch R = 3 ,20251.6 ,,,
BEGIN DESCRIPTION:
INTERSTATE 45
Structure ID: C00-13
END DESCRIPTION:
Bridge Culvert--1,0,-1,-1, 0
Deck Dist Width WeirC Skew NumUp NumDn MinLoCord MaxHiCord MaxSubmerge Is_Ogee
10,277,2.6,0, 43, 42, , , 0.95, 0, 1,1,,
  3056.3  3255.2  3265.2  3460.2  3465.2  3735.2  3764.5  4074.5  4084.5  4286.2
  4376.2  4586.2  4588.6    4616  4662.3  4709.7  4759.2  4798.6 4801.49  4801.6
    4818  4873.1  5134.2  5170.7    5194 5194.11  5196.9  5260.9  5364.7  5440.1
  5447.8  5507.8  5517.8  5596.6  5604.1  5616.6  6285.9  6450.9  6499.1  6503.5
  6535.9  6565.9  6585.9
    37.9   36.26   36.18   34.57   34.52    32.3   32.05    29.5   29.41   27.75
   27.11   26.81    26.1   26.17   25.28    26.1   26.39    26.1   25.75   29.75
   29.86   29.96   30.42   30.49   30.53   26.53   26.98   26.79   27.93      28
   27.71   28.44   28.74   31.08    31.3   31.38   35.72   36.79    37.1      37
    35.8    36.8      36
    37.9    31.5    31.7    29.6    29.7    29.5    29.3    26.4    26.5    25.8
    27.1    26.8   26.09   26.16   25.27   26.09   26.38   26.09    25.5   25.48
   22.14   21.76   22.22   22.71    26.5   26.52   26.97   26.78   27.92   27.99
    27.7    28.4    28.2    28.4   28.29    28.1    31.4    31.5   33.62   33.86
    35.8    36.8      36
  3056.3  3255.2  3265.2  3460.2  3465.2  3735.2  3764.5  4074.5  4084.5  4286.2
  4376.2  4586.2  4588.6    4616  4662.3  4709.7  4759.2  4798.6 4801.49  4801.6
    4818  4873.1  5134.2  5170.7    5194 5194.11  5196.9  5260.9  5364.7  5440.1
  5447.8  5507.8  5517.8  5596.6  5604.1  5616.6  6285.9  6450.9  6499.1  6535.9
  6565.9  6585.9
   38.29   36.26   36.18   34.57   34.52    32.3   32.05    29.5   29.41   27.75
   27.49   27.19   26.48   26.55   25.66   26.48   26.77   26.48   25.89   29.75
   29.86   29.96   30.42   30.49   30.53   26.91   27.36   27.17   28.31   28.38
   28.09   28.79   28.74   31.08    31.3   31.38   35.72   36.79    37.1   36.19
   37.19   36.39
   38.29   31.89   32.09   29.99   30.09   29.89   29.69   26.79   26.89   26.19
   27.49   27.19   26.48   26.55   25.66   26.48   26.77   26.48   25.89   25.87
   22.53   22.15   22.61    23.1   26.89   26.91   27.36   27.17   28.31   28.38
   28.09   28.79   28.59   28.79   28.68   28.49   31.79   31.89   34.01   36.19
   37.19   36.39
Pier Skew, UpSta & Num, DnSta & Num=  ,4937.9, 2 ,4937.9, 2 , 0 , 0 , 0 ,,
       3       3
      .2   22.87
       3       3
     .59   23.26
Pier Skew, UpSta & Num, DnSta & Num=  ,5057.8, 2 ,5057.8, 2 , 0 , 0 , 0 ,,
       3       3
   -2.21   23.09
       3       3
   -1.82   23.48
Abutment Skew #Up #Dn= , 2 , 2
  4817.8  4919.1
   22.14     2.9
  4817.8  4919.1
   22.53    3.29
Abutment Skew #Up #Dn= , 2 , 2
    5071 5197.79
    3.47   26.97
    5071 5197.79
    3.86   27.36
BR Coef= 1 , 1 , 0 ,1.25, 0 ,,,0.8,-1,2,0,
WSPro=,,,, 1 ,,,, 0 ,,,, 0 ,,,,-1 ,-1 ,-1 , 0 , 0 , 0 , 0 , 0
BR U #Sta/Elev= 73
  3056.3    37.9  3255.2    31.5  3265.2    31.7  3460.2    29.6  3465.2    29.7
  3615.2    29.6  3735.2    29.5  3764.5    29.3  4074.5    26.4  4084.5    26.5
  4286.2    25.8  4376.2    27.1  4586.2    26.8  4588.6   26.09    4616   26.16
  4616.7   26.15  4661.3   25.29  4662.3   25.27  4709.7   26.09  4709.8   26.09
  4759.2   26.38  4759.6   26.38  4798.6   26.09 4801.49    25.5  4801.6   25.48
 4801.71   25.46  4817.8   22.18 4817.91   22.16    4818   22.14  4873.1   10.92
    4919    2.91  4919.1     2.9  4937.9    1.29  4941.6    1.08  4945.3   -1.21
  5007.2  -10.37    5057   -1.08  5057.8    -.67  5058.5    1.56  5070.9    3.45
    5071    3.47  5134.2   13.22  5170.7   22.71 5193.89   26.48    5194    26.5
 5194.11   26.52  5196.9   26.97 5197.59   26.97  5197.7   26.97  5197.8   26.97
  5260.9   26.78  5264.8   26.82  5314.3   27.39  5314.4   27.39  5364.7   27.92
  5365.9   27.92  5412.3   27.94  5412.7   27.94  5440.1   27.99  5447.8    27.7
  5507.8    28.4  5517.8    28.2  5596.6    28.4  5604.1   28.29  5616.6    28.1
  6285.9    31.4  6450.9    31.5  6499.1   33.62  6500.9    33.7  6503.5   33.86
  6535.9    35.8  6565.9    36.8  6585.9      36
BR U #Mann= 3
  3056.3      .1  4798.6    .035  5196.9      .1
BR U Banks=4798.6,5196.9
BR D #Sta/Elev= 73
  3056.3   38.29  3255.2   31.89  3265.2   32.09  3460.2   29.99  3465.2   30.09
  3615.2   29.99  3735.2   29.89  3764.5   29.69  4074.5   26.79  4084.5   26.89
  4286.2   26.19  4376.2   27.49  4586.2   27.19  4588.6   26.48    4616   26.55
  4616.7   26.54  4661.3   25.68  4662.3   25.66  4709.7   26.48  4709.8   26.48
  4759.2   26.77  4759.6   26.77  4798.6   26.48 4801.49   25.89  4801.6   25.87
 4801.71   25.85  4817.8   22.57 4817.91   22.55    4818   22.53  4873.1   11.31
    4919     3.3  4919.1    3.29  4937.9    1.68  4941.6    1.47  4945.3    -.82
  5007.2   -9.98    5057    -.69  5057.8    -.28  5058.5    1.95  5070.9    3.84
    5071    3.86  5134.2   13.61  5170.7    23.1 5193.89   26.87    5194   26.89
 5194.11   26.91  5196.9   27.36 5197.59   27.36  5197.7   27.36  5197.8   27.36
  5260.9   27.17  5264.8   27.21  5314.3   27.78  5314.4   27.78  5364.7   28.31
  5365.9   28.31  5412.3   28.33  5412.7   28.33  5440.1   28.38  5447.8   28.09
  5507.8   28.79  5517.8   28.59  5596.6   28.79  5604.1   28.68  5616.6   28.49
  6285.9   31.79  6450.9   31.89  6499.1   34.01  6500.9   34.09  6503.5   34.25
  6535.9   36.19  6565.9   37.19  6585.9   36.39
BR D #Mann= 3
  3056.3      .1  4798.6    .035  5196.9      .1
BR D Banks=4798.6,5196.9
BC Design=,, 0 ,, 0 ,,,,,,
BC HTab HWMax=37.95
BC Use User HTab Curves=0
BC User HTab FreeFlow(D)= 0

Type RM Length L Ch R = 1 ,20103.1 ,0.3,0.3,0.3
BEGIN DESCRIPTION:
Downstream Section of Bridge/Culvert/Weir
END DESCRIPTION:
XS GIS Cut Line= 4
      3150685.62     13815264.16      3151473.47     13814427.93
      3152420.28     13813398.19      3153099.29       13812689.
#Sta/Elev= 30
  3056.3   38.29  3255.2   31.89  3460.2   29.99  3735.2   29.89  4074.5   26.79
  4286.2   26.19  4376.2   27.49  4586.2   27.19  4588.6   26.48  4662.3   25.66
  4709.7   26.48  4798.6   26.48  4873.1   11.31    4919     3.3  4941.6    1.47
  4945.3    -.82  5007.2   -9.98    5057    -.69  5057.8    -.28  5058.5    1.95
  5134.2   13.61  5170.7    23.1  5196.9   27.36  5507.8   28.79  5616.6   28.49
  6285.9   31.79  6450.9   31.89  6535.9   36.19  6565.9   37.19  6585.9   36.39
#Mann= 3 , 1 , 0
  3056.3      .1       0  4798.6    .035       0  5196.9      .1       0
#XS Ineff= 2 , 0
       0    4808   25.69    5208       0   27.22
Permanent Ineff=
       F       F
Bank Sta=4798.6,5196.9
XS Rating Curve= 0 ,0
Exp/Cntr=0.5,0.3

Type RM Length L Ch R = 1 ,20102.8 ,23,23,23
BEGIN DESCRIPTION:
Upstream Section of Bridge/Culvert/Weir
END DESCRIPTION:
XS GIS Cut Line= 4
      3151353.35     13814489.86      3151888.66      13813989.1
      3152066.46     13813794.71      3152376.46      13813406.7
#Sta/Elev= 27
  4086.9    29.9  4236.9   27.65  4261.9   26.17  4286.9   26.42  4296.9   27.16
  4361.9   27.55  4580.9   27.39  4625.9   26.52  4640.9   25.84  4665.9   26.06
  4689.2    25.7  4724.2   25.69  4739.2   25.24 4748.72   24.58 4796.52   25.58
 4877.52   10.27 4940.22    1.65 4941.32     .59 5000.02   -9.98 5055.02     .34
 5059.72    1.42 5122.52    9.43 5198.72   25.42 5245.22   25.81    5415   28.73
    5450   30.53    5580   31.27
#Mann= 3 , 1 , 0
  4086.9      .1       0 4796.52    .035       0 5198.72      .1       0
#XS Ineff= 2 , 0
       0    4806   21.85    5197       0   22.94
Permanent Ineff=
       F       F
Bank Sta=4796.52,5198.72
XS Rating Curve= 0 ,0
Exp/Cntr=0.5,0.3

Type RM Length L Ch R = 3 ,20091.3 ,,,
BEGIN DESCRIPTION:
36" DIA. PIPE @ I-45
END DESCRIPTION:
Bridge Culvert--1,0,-1,-1, 0
Deck Dist Width WeirC Skew NumUp NumDn MinLoCord MaxHiCord MaxSubmerge Is_Ogee
10,3,2.6,0, 41, 41, , , 0.95, 0, 1,1,,
  4086.9  4236.9  4261.9  4286.9  4296.9  4361.9  4580.9  4625.9  4640.9  4665.9
  4689.2  4708.5  4724.2  4728.5  4739.2  4743.5  4744.2 4748.72  4753.5  4768.5
 4796.52 4816.12 4816.23 4816.32 4877.52 4879.92 4940.22 4941.32 5000.02 5055.02
 5059.72 5122.52 5143.42 5186.91 5187.02 5187.12 5198.72 5245.22    5415    5450
    5580
    29.9   27.65   26.17   26.42   27.16   27.55   27.39   26.52   25.84   26.06
    25.7    25.7    25.7   25.57   25.25   24.97   24.92   24.59   24.69      25
   25.59   21.89   21.86   21.85   25.85   26.07   26.17   26.17   26.26   26.35
   26.36   26.46   26.49   22.95   22.97   22.99   25.42   25.81   28.73   30.53
   31.27
    29.9   27.65   26.17   26.42   27.16   27.55   27.39   26.52   25.84   26.06
    25.7   25.69   25.69   25.56   25.24   24.96   24.91   24.58   24.68   24.99
   25.58   21.88   21.85   21.84   22.85   23.07   23.17   23.17   23.26   23.35
   23.36   23.46   23.49   22.94   22.96   22.99   25.42   25.81   28.73   30.53
   31.27
  4086.9  4236.9  4261.9  4286.9  4296.9  4361.9  4580.9  4625.9  4640.9  4665.9
  4689.2  4708.5  4724.2  4728.5  4739.2  4743.5  4744.2 4748.72  4753.5  4768.5
 4796.52 4816.12 4816.23 4816.32 4877.52 4879.92 4940.22 4941.32 5000.02 5055.02
 5059.72 5122.52 5143.42 5186.91 5187.02 5187.12 5198.72 5245.22    5415    5450
    5580
    29.9   27.65   26.17   26.42   27.16   27.55   27.39   26.52   25.84   26.06
    25.7    25.7    25.7   25.57   25.25   24.97   24.92   24.59   24.69      25
   25.59   21.89   21.86   21.85   25.85   26.07   26.17   26.17   26.26   26.35
   26.36   26.46   26.49   22.95   22.97   22.99   25.42   25.81   28.73   30.53
   31.27
    29.9   27.65   26.17   26.42   27.16   27.55   27.39   26.52   25.84   26.06
    25.7   25.69   25.69   25.56   25.24   24.96   24.91   24.58   24.68   24.99
   25.58   21.88   21.85   21.84   22.85   23.07   23.17   23.17   23.26   23.35
   23.36   23.46   23.49   22.94   22.96   22.99   25.42   25.81   28.73   30.53
   31.27
Pier Skew, UpSta & Num, DnSta & Num=  ,4822.3, 2 ,4822.3, 2 , 0 , 0 , 0 ,,
       1       1
   19.61   22.95
       1       1
   19.61   22.95
Pier Skew, UpSta & Num, DnSta & Num=  ,4859.4, 2 ,4859.4, 2 , 0 , 0 , 0 ,,
       2       2
    12.5   23.57
       2       2
    12.5   23.57
Pier Skew, UpSta & Num, DnSta & Num=  ,4916.2, 2 ,4916.2, 2 , 0 , 0 , 0 ,,
       2       2
    3.81   24.13
       2       2
    3.81   24.13
Pier Skew, UpSta & Num, DnSta & Num=  ,4986.1, 2 ,4986.1, 2 , 0 , 0 , 0 ,,
       2       2
   -8.66   24.24
       2       2
   -8.66   24.24
Pier Skew, UpSta & Num, DnSta & Num=  ,5050.6, 2 ,5050.6, 2 , 0 , 0 , 0 ,,
       2       2
   -1.67   24.34
       2       2
   -1.67   24.34
Pier Skew, UpSta & Num, DnSta & Num=  ,5110.9, 2 ,5110.9, 2 , 0 , 0 , 0 ,,
       2       2
    6.82   24.44
       2       2
    6.82   24.44
BR Coef= 1 , 1 , 0 ,1.25, 0 ,,,0.8,-1,2,0,
WSPro=,,,, 1 ,,,, 0 ,,,, 0 ,,,,-1 ,-1 ,-1 , 0 , 0 , 0 , 0 , 0
BR U #Sta/Elev= 41
  4086.9    29.9  4236.9   27.65  4261.9   26.17  4286.9   26.42  4296.9   27.16
  4361.9   27.55  4580.9   27.39  4625.9   26.52  4640.9   25.84  4665.9   26.06
  4689.2    25.7  4708.5   25.69  4724.2   25.69  4728.5   25.56  4739.2   25.24
  4743.5   24.96  4744.2   24.91 4748.72   24.58  4753.5   24.68  4768.5   24.99
 4796.52   25.58 4816.12   21.88 4816.23   21.85 4816.32   21.84 4877.52   10.27
 4879.92    9.94 4940.22    1.65 4941.32     .59 5000.02   -9.98 5055.02     .34
 5059.72    1.42 5122.52    9.43 5143.42   13.82 5186.91   22.94 5187.02   22.96
 5187.12   22.99 5198.72   25.42 5245.22   25.81    5415   28.73    5450   30.53
    5580   31.27
BR U #Mann= 3
  4086.9      .1 4796.52    .035 5198.72      .1
BR U Banks=4796.52,5198.72
BR D #Sta/Elev= 41
  4086.9    29.9  4236.9   27.65  4261.9   26.17  4286.9   26.42  4296.9   27.16
  4361.9   27.55  4580.9   27.39  4625.9   26.52  4640.9   25.84  4665.9   26.06
  4689.2    25.7  4708.5   25.69  4724.2   25.69  4728.5   25.56  4739.2   25.24
  4743.5   24.96  4744.2   24.91 4748.72   24.58  4753.5   24.68  4768.5   24.99
 4796.52   25.58 4816.12   21.88 4816.23   21.85 4816.32   21.84 4877.52   10.27
 4879.92    9.94 4940.22    1.65 4941.32     .59 5000.02   -9.98 5055.02     .34
 5059.72    1.42 5122.52    9.43 5143.42   13.82 5186.91   22.94 5187.02   22.96
 5187.12   22.99 5198.72   25.42 5245.22   25.81    5415   28.73    5450   30.53
    5580   31.27
BR D #Mann= 3
  4086.9      .1 4796.52    .035 5198.72      .1
BR D Banks=4796.52,5198.72
BC Design=,, 0 ,, 0 ,,,,,,
BC HTab HWMax=31.27
BC Use User HTab Curves=0
BC User HTab FreeFlow(D)= 0

Type RM Length L Ch R = 1 ,20079.8 ,493.4,493.4,493.4
BEGIN DESCRIPTION:
Downstream Section of Bridge/Culvert/Weir
END DESCRIPTION:
XS GIS Cut Line= 4
       3151370.3     13814505.41      3151905.62     13814004.64
      3152083.42     13813810.25      3152393.41     13813422.25
#Sta/Elev= 27
  4086.9   29.95  4236.9    27.7  4261.9   26.22  4286.9   26.47  4296.9   27.21
  4361.9    27.6  4580.9   27.44  4625.9   26.57  4640.9   25.89  4665.9   26.11
  4689.2   25.75  4724.2   25.74  4739.2   25.29 4748.72   24.63 4796.52   25.63
 4877.52   10.32 4940.22     1.7 4941.32     .64 5000.02   -9.93 5055.02     .39
 5059.72    1.47 5122.52    9.48 5198.72   25.47 5245.22   25.86    5415   28.78
    5450   30.58    5580   31.32
#Mann= 3 , 1 , 0
  4086.9      .1       0 4796.52    .035       0 5198.72      .1       0
#XS Ineff= 2 , 0
       0    4806   21.85    5197       0   22.94
Permanent Ineff=
       F       F
Bank Sta=4796.52,5198.72
XS Rating Curve= 0 ,0
Exp/Cntr=0.5,0.3

Type RM Length L Ch R = 1 ,19586.4 ,529.6,650.4,837.7
BEGIN DESCRIPTION:
Cross Section 19586.4
END DESCRIPTION:
XS GIS Cut Line= 5
       3151165.2     13815507.77      3151973.79     13814664.63
      3152457.56     13814194.68       3152547.4       13813704.
      3152554.31     13813469.03
#Sta/Elev= 30
    2908    31.2    3028    30.6    3108    28.3    3148    29.5    3473    29.5
    3523    27.2    3628    28.1    3938    26.9    3963    25.9  4076.2    27.3
  4366.2    26.4  4446.1    25.2  4711.2    24.4  4795.7    19.3  4859.3   19.35
  4867.3   18.52  4933.5   -2.21  4949.7   -5.16  4996.9   -7.48  5069.4   -1.14
  5127.9   17.39  5149.1   18.17  5150.7    16.1  5195.7    14.7  5210.7    15.4
  5254.5    20.7  5299.5    28.2    5398   30.12  5429.5    31.2  5484.6    31.2
#Mann= 7 , 1 , 0
    2908      .2       0    2908      .1       0  4446.1     .07       0
  4867.3    .035       0  5127.9     .07       0    5398      .1       0
  5484.6      .2       0
Bank Sta=4867.3,5127.9
XS Rating Curve= 0 ,0
Exp/Cntr=0.3,0.1

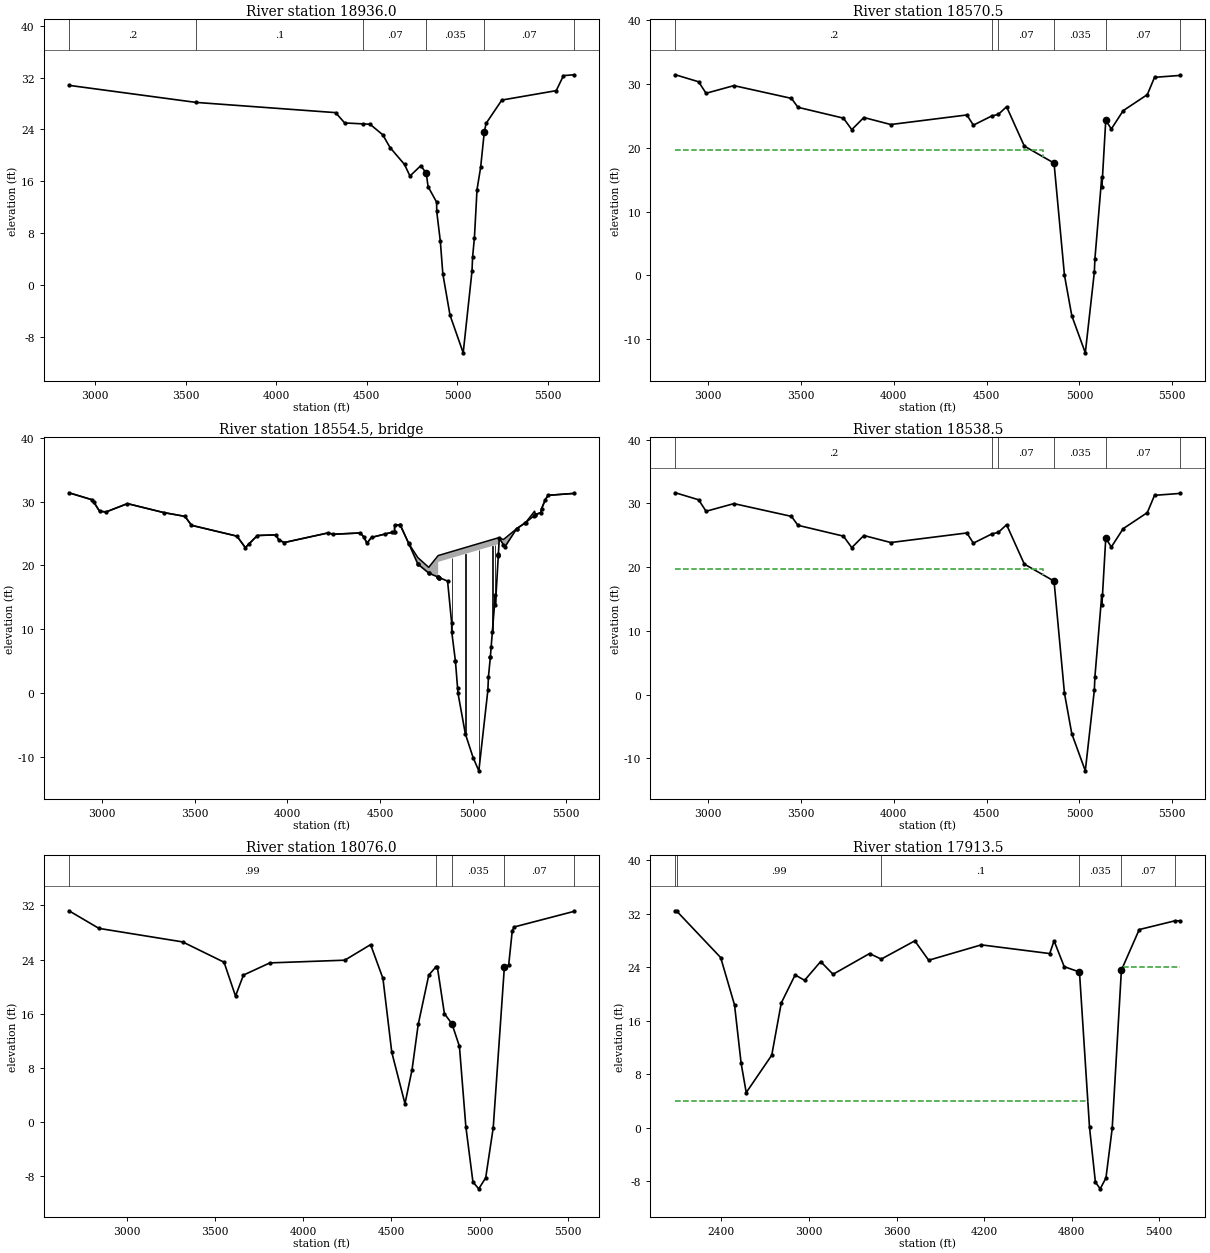
Type RM Length L Ch R = 1 ,18936.0 ,370.8,365.5,277.6
BEGIN DESCRIPTION:
Cross Section 18936.0 - Interpolated
END DESCRIPTION:
XS GIS Cut Line= 6
      3151209.42     13815500.55      3151809.85      13815061.7
      3152477.07     13814772.31      3152677.33     13814606.13
      3153154.55     13814231.18      3153589.15     13814128.92
#Sta/Elev= 30
  2856.6    30.8  3556.6   28.17  4327.6   26.59  4377.6      25  4481.2   24.85
  4517.6    24.8  4587.8   23.17  4627.8   21.21  4707.8   18.59  4737.8   16.81
  4797.8   18.41  4827.8   17.24  4837.8   15.17    4885   12.77  4885.5   11.34
  4905.4    6.73  4919.2    1.71  4958.7   -4.65  5031.5  -10.47  5080.1    2.15
  5083.3    4.29  5093.5    7.32  5107.8   14.72  5127.8   18.16  5147.8   23.58
  5157.8   24.93  5244.7   28.53  5544.7   29.98  5584.7    32.3  5641.2   32.43
#Mann= 6 , 1 , 0
  2856.6      .2       0  3556.6      .1       0  4481.2     .07       0
  4827.8    .035       0  5147.8     .07       0  5641.2      .2       0
Bank Sta=4827.8,5147.8
XS Rating Curve= 0 ,0
Exp/Cntr=0.5,0.3

Type RM Length L Ch R = 1 ,18570.5 ,32,32,32
BEGIN DESCRIPTION:
Upstream Section of Bridge/Culvert/Weir
END DESCRIPTION:
XS GIS Cut Line= 6
        3151333.     13815639.55      3152969.31     13814946.03
      3153141.55     13814727.39      3153183.39     13814648.39
      3153404.64     13814344.12      3153577.15     13814247.08
#Sta/Elev= 30
  2823.5   31.45  2948.5   30.35  2988.5   28.55  3138.5   29.75  3448.5   27.75
  3483.5   26.35  3728.5   24.65  3773.5   22.85  3838.5   24.75  3983.5   23.65
  4393.5   25.15  4428.5   23.55  4527.4   24.99    4563   25.24  4607.4   26.44
  4702.9   20.27  4863.1    17.6  4919.2     .03  4958.7   -6.33  5031.5  -12.15
  5080.1     .47  5083.3    2.61    5120   15.37  5120.9   13.82  5141.7   24.32
  5171.7   22.95  5235.5   25.82  5365.6   28.34  5404.4   31.05  5542.6   31.35
#Mann= 6 , 1 , 0
  2823.5      .2       0  4527.4      .1       0    4563     .07       0
  4863.1    .035       0  5141.7     .07       0  5542.6      .2       0
#XS Ineff= 2 , 0
       0    4802   19.69    5147       0   24.03
Permanent Ineff=
       F       F
Bank Sta=4863.1,5141.7
XS Rating Curve= 0 ,0
Exp/Cntr=0.5,0.3

Type RM Length L Ch R = 3 ,18554.5 ,,,
BEGIN DESCRIPTION:
GLENBROOK GOLFCOURSE FOOTBRIDGE #3 (DS TO US)
Structure ID: C00-12
END DESCRIPTION:
Bridge Culvert--1,0,-1,-1, 0
Deck Dist Width WeirC Skew NumUp NumDn MinLoCord MaxHiCord MaxSubmerge Is_Ogee
10,12,2.6,0, 43, 44, , , 0.95, 0, 1,1,,
  2823.5  2948.5  2988.5  3023.5  3138.5  3333.5  3448.5  3483.5  3728.5  3773.5
  3838.5  3938.5  3953.5  3983.5  4218.5  4248.5  4393.5  4413.5  4428.5  4453.5
  4577.6  4577.7  4607.4  4654.4  4702.9  4761.4 4812.41  4812.5 5136.26 5136.59
  5136.7  5141.7  5163.6  5171.7  5235.5  5283.7  5331.7  5336.6  5365.6  5369.4
  5389.4  5404.4  5542.6
    31.4    30.3    28.5    28.4    29.7    28.3    27.7    26.3    24.6    22.8
    24.7    24.8      24    23.6    25.1    24.9    25.1    24.4    23.5    24.4
   25.31    26.3    26.4   23.42   21.24   19.71   21.56   21.56   24.34   24.34
   24.34   24.29   24.08   24.25   25.78   26.73   28.51   28.04   28.29    28.9
    30.3      31    31.3
    31.4    30.3    28.5    28.4    29.7    28.3    27.7    26.3    24.6    22.8
    24.7    24.8      24    23.6    25.1    24.9    25.1    24.4    23.5    24.4
    25.3   26.29   26.39   23.41   20.22   18.82   18.18   20.56   23.34   23.34
   21.75   24.27   23.27    22.9   25.77   26.73   27.85   27.92   28.29    28.9
    30.3      31    31.3
  2823.5  2948.5  2958.5  2988.5  3023.5  3138.5  3333.5  3448.5  3483.5  3728.5
  3773.5  3838.5  3938.5  3953.5  3983.5  4218.5  4248.5  4393.5  4413.5  4428.5
  4453.5  4577.6  4577.7  4607.4  4654.4  4702.9  4761.4 4812.41  4812.5 5136.26
 5136.59  5136.7  5141.7  5163.6  5171.7  5235.5  5283.7  5331.7  5336.6  5365.6
  5369.4  5389.4  5404.4  5542.6
    31.6    30.5    30.1    28.7    28.6    29.9    28.5    27.9    26.5    24.8
      23    24.9      25    24.2    23.8    25.3    25.1    25.3    24.6    23.7
    24.6    25.5   26.49   26.59   23.61   21.24   19.71   21.56   21.56   24.34
   24.34   24.34   24.47   24.08   24.25   25.97   26.93   28.51   28.12   28.49
    29.1    30.5    31.2    31.5
    31.6    30.5    30.1    28.7    28.6    29.9    28.5    27.9    26.5    24.8
      23    24.9      25    24.2    23.8    25.3    25.1    25.3    24.6    23.7
    24.6    25.5   26.49   26.59   23.61   20.42   19.02   18.38   20.76   23.54
   23.54   21.95   24.47   23.47    23.1   25.97   26.93   28.05   28.12   28.49
    29.1    30.5    31.2    31.5
Pier Skew, UpSta & Num, DnSta & Num=  ,4885.5, 2 ,4885.5, 2 , 0 , 0 , 0 ,,
       2       2
    8.38   22.19
       2       2
    8.58   22.39
Pier Skew, UpSta & Num, DnSta & Num=  ,4958.7, 2 ,4958.7, 2 , 0 , 0 , 0 ,,
       2       2
   -7.47   22.82
       2       2
   -7.27   23.02
Pier Skew, UpSta & Num, DnSta & Num=  ,5031.5, 2 ,5031.5, 2 , 0 , 0 , 0 ,,
       2       2
  -13.13   23.44
       2       2
  -12.93   23.64
Pier Skew, UpSta & Num, DnSta & Num=  ,5104.2, 2 ,5104.2, 2 , 0 , 0 , 0 ,,
       2       2
    8.19   24.07
       2       2
    8.39   24.27
Pier Skew, UpSta & Num, DnSta & Num=  ,5120, 2 ,5120, 2 , 0 , 0 , 0 ,,
       1       1
   13.46    24.2
       1       1
   13.66    24.4
Abutment Skew #Up #Dn= , 2 , 2
  4812.3  4905.4
   20.56       5
  4812.3  4905.4
   20.76     5.2
Abutment Skew #Up #Dn= , 2 , 2
  5093.5 5136.79
    5.63   23.34
  5093.5 5136.79
    5.83   23.54
BR Coef= 1 , 1 , 0 ,1.25, 0 ,,,0.8,-1,2,0,
WSPro=,,,, 1 ,,,, 0 ,,,, 0 ,,,,-1 ,-1 ,-1 , 0 , 0 , 0 , 0 , 0
BR U #Sta/Elev= 79
  2823.5    31.4  2948.5    30.3  2958.5    29.9  2988.5    28.5  3023.5    28.4
  3138.5    29.7  3333.5    28.3  3448.5    27.7  3483.5    26.3  3728.5    24.6
  3773.5    22.8  3793.5    23.4  3838.5    24.7  3938.5    24.8  3953.5      24
  3983.5    23.6  4218.5    25.1  4248.5    24.9  4393.5    25.1  4413.5    24.4
  4428.5    23.5  4453.5    24.4  4527.4   24.94    4563   25.19  4572.6   25.26
  4577.6    25.3  4577.7   26.29  4605.1   26.38  4607.4   26.39  4653.4   23.47
  4654.4   23.41  4702.9   20.22  4704.5   20.18  4761.4   18.82  4762.6   18.79
  4812.3   18.18 4812.41   18.18  4812.5   18.17 4818.49    18.1  4818.6    18.1
 4818.71    18.1  4863.1   17.55    4885   11.04  4885.5    9.61  4905.3    5.02
  4905.4       5  4916.8     .86  4919.2    -.02  4958.7   -6.38  5000.8  -10.14
  5031.5   -12.2  5080.1     .42  5083.3    2.56  5093.4    5.59  5093.5    5.63
  5097.8    7.21  5104.2    9.56    5120   15.32  5120.9   13.77 5136.26   21.52
 5136.37   21.58 5136.48   21.63 5136.59   21.69  5136.7   21.75  5141.7   24.27
  5163.6   23.27  5171.7    22.9  5234.6   25.73  5235.5   25.77  5280.7   26.67
  5283.7   26.73  5329.9   27.83  5331.7   27.85  5336.6   27.92  5365.6   28.29
  5369.4    28.9  5389.4    30.3  5404.4      31  5542.6    31.3
BR U #Mann= 6
  2823.5      .2  4527.4      .1    4563     .07  4863.1    .035  5141.7     .07
  5542.6      .2
BR U Banks=4863.1,5141.7
BR D #Sta/Elev= 79
  2823.5    31.6  2948.5    30.5  2958.5    30.1  2988.5    28.7  3023.5    28.6
  3138.5    29.9  3333.5    28.5  3448.5    27.9  3483.5    26.5  3728.5    24.8
  3773.5      23  3793.5    23.6  3838.5    24.9  3938.5      25  3953.5    24.2
  3983.5    23.8  4218.5    25.3  4248.5    25.1  4393.5    25.3  4413.5    24.6
  4428.5    23.7  4453.5    24.6  4527.4   25.14    4563   25.39  4572.6   25.46
  4577.6    25.5  4577.7   26.49  4605.1   26.58  4607.4   26.59  4653.4   23.67
  4654.4   23.61  4702.9   20.42  4704.5   20.38  4761.4   19.02  4762.6   18.99
  4812.3   18.38 4812.41   18.38  4812.5   18.37 4818.49    18.3  4818.6    18.3
 4818.71    18.3  4863.1   17.75    4885   11.24  4885.5    9.81  4905.3    5.22
  4905.4     5.2  4916.8    1.06  4919.2     .18  4958.7   -6.18  5000.8   -9.94
  5031.5     -12  5080.1     .62  5083.3    2.76  5093.4    5.79  5093.5    5.83
  5097.8    7.41  5104.2    9.76    5120   15.52  5120.9   13.97 5136.26   21.72
 5136.37   21.78 5136.48   21.83 5136.59   21.89  5136.7   21.95  5141.7   24.47
  5163.6   23.47  5171.7    23.1  5234.6   25.93  5235.5   25.97  5280.7   26.87
  5283.7   26.93  5329.9   28.03  5331.7   28.05  5336.6   28.12  5365.6   28.49
  5369.4    29.1  5389.4    30.5  5404.4    31.2  5542.6    31.5
BR D #Mann= 6
  2823.5      .2  4527.4      .1    4563     .07  4863.1    .035  5141.7     .07
  5542.6      .2
BR D Banks=4863.1,5141.7
BC Design=,, 0 ,, 0 ,,,,,,
BC HTab HWMax=31.45
BC Use User HTab Curves=0
BC User HTab FreeFlow(D)= 0

Type RM Length L Ch R = 1 ,18538.5 ,462.5,462.5,462.5
BEGIN DESCRIPTION:
Downstream Section of Bridge/Culvert/Weir
END DESCRIPTION:
XS GIS Cut Line= 6
      3151352.52     13815664.91      3152988.83     13814971.39
      3153161.07     13814752.75      3153202.91     13814673.75
      3153424.16     13814369.48      3153596.67     13814272.44
#Sta/Elev= 30
  2823.5   31.65  2948.5   30.55  2988.5   28.75  3138.5   29.95  3448.5   27.95
  3483.5   26.55  3728.5   24.85  3773.5   23.05  3838.5   24.95  3983.5   23.85
  4393.5   25.35  4428.5   23.75  4527.4   25.19    4563   25.44  4607.4   26.64
  4702.9   20.47  4863.1    17.8  4919.2     .23  4958.7   -6.13  5031.5  -11.95
  5080.1     .67  5083.3    2.81    5120   15.57  5120.9   14.02  5141.7   24.52
  5171.7   23.15  5235.5   26.02  5365.6   28.54  5404.4   31.25  5542.6   31.55
#Mann= 6 , 1 , 0
  2823.5      .2       0  4527.4      .1       0    4563     .07       0
  4863.1    .035       0  5141.7     .07       0  5542.6      .2       0
#XS Ineff= 2 , 0
       0    4802   19.69    5147       0   24.03
Permanent Ineff=
       F       F
Bank Sta=4863.1,5141.7
XS Rating Curve= 0 ,0
Exp/Cntr=0.5,0.3

Type RM Length L Ch R = 1 ,18076.0 ,2562.5,162.5,169.9
BEGIN DESCRIPTION:
Cross Section 18076.0 - Interpolated
END DESCRIPTION:
XS GIS Cut Line= 6
       3151382.3     13815677.81      3152952.01     13815132.98
      3153371.85      13815219.7       3153529.5     13815027.96
      3153695.67     13814908.65      3154006.71     13814836.22
#Sta/Elev= 30
  2670.2    31.2  2840.2    28.6  3315.2    26.6  3550.2    23.6  3615.2    18.6
  3660.2    21.7  3810.2    23.5  4235.2    23.9  4381.8    26.2  4451.8    21.2
  4501.8    10.3  4576.8     2.7  4616.8     7.7  4651.8    14.4  4711.8    21.7
  4750.2   22.84  4760.5    22.9  4800.5      16  4843.4    14.5  4885.7   11.17
  4922.1    -.68  4962.4   -8.87  4995.3   -9.88  5034.8   -8.25  5077.5    -.85
  5140.6   22.84  5165.3    23.2  5185.3    28.2  5195.3    28.8  5534.2    31.1
#Mann= 5 ,-1 , 0
  2670.2     .99       0  4750.2      .1       0  4843.4    .035       0
  5140.6     .07       0  5534.2      .2       0
Bank Sta=4843.4,5140.6
XS Rating Curve= 0 ,0
Exp/Cntr=0.5,0.3

Type RM Length L Ch R = 1 ,17913.5 ,34,34,34
BEGIN DESCRIPTION:
Upstream Section of Bridge/Culvert/Weir
END DESCRIPTION:
XS GIS Cut Line= 6
      3151594.83     13817146.42      3153253.48     13815849.66
      3153428.33     13815567.31      3153418.83     13815369.61
      3153463.38     13815266.63      3154069.02     13814895.03
#Sta/Elev= 30
  2085.1   32.45  2094.6   32.38  2395.1   25.45  2490.1   18.35  2535.1    9.65
  2570.1    5.25  2745.1   10.85  2810.1   18.65  2905.1   22.85  2970.1   22.05
  3080.1   24.85  3165.1   22.95  3415.1   26.05  3495.1   25.22  3725.1   27.95
  3820.1   25.05  4180.7   27.35  4649.3   26.05  4679.3   27.95  4748.7   24.09
  4853.3   23.29  4922.1     .05  4962.4   -8.14  4995.3   -9.15  5034.8   -7.52
  5077.5    -.12  5140.6   23.57  5262.7   29.64  5507.7   30.95  5543.3   30.95
#Mann= 6 , 1 , 0
  2085.1     .15       0  2094.6     .99       0  3495.1      .1       0
  4853.3    .035       0  5140.6     .07       0  5507.7      .2       0
#XS Ineff= 2 , 0
       0    4911    4.04    5150       0   24.04
Permanent Ineff=
       F       F
Bank Sta=4853.3,5140.6
XS Rating Curve= 0 ,0
Exp/Cntr=0.5,0.3