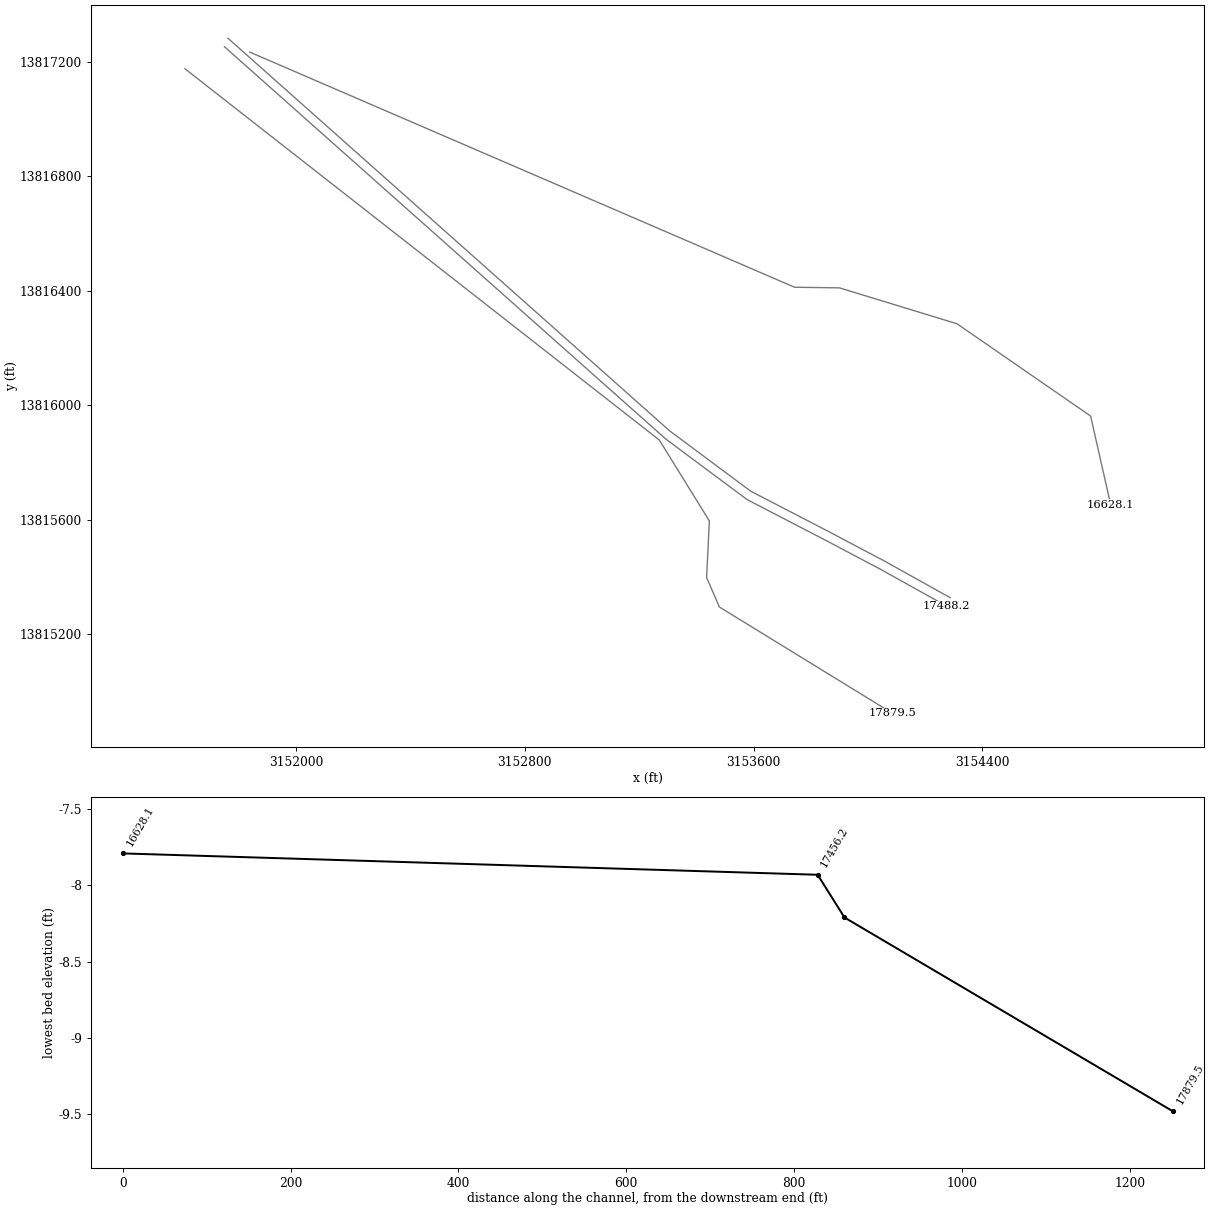
HEC-RAS study C100-00-00.prj: C100-00-00

--- C100-00-00.g01 (geometry) --- (continued)

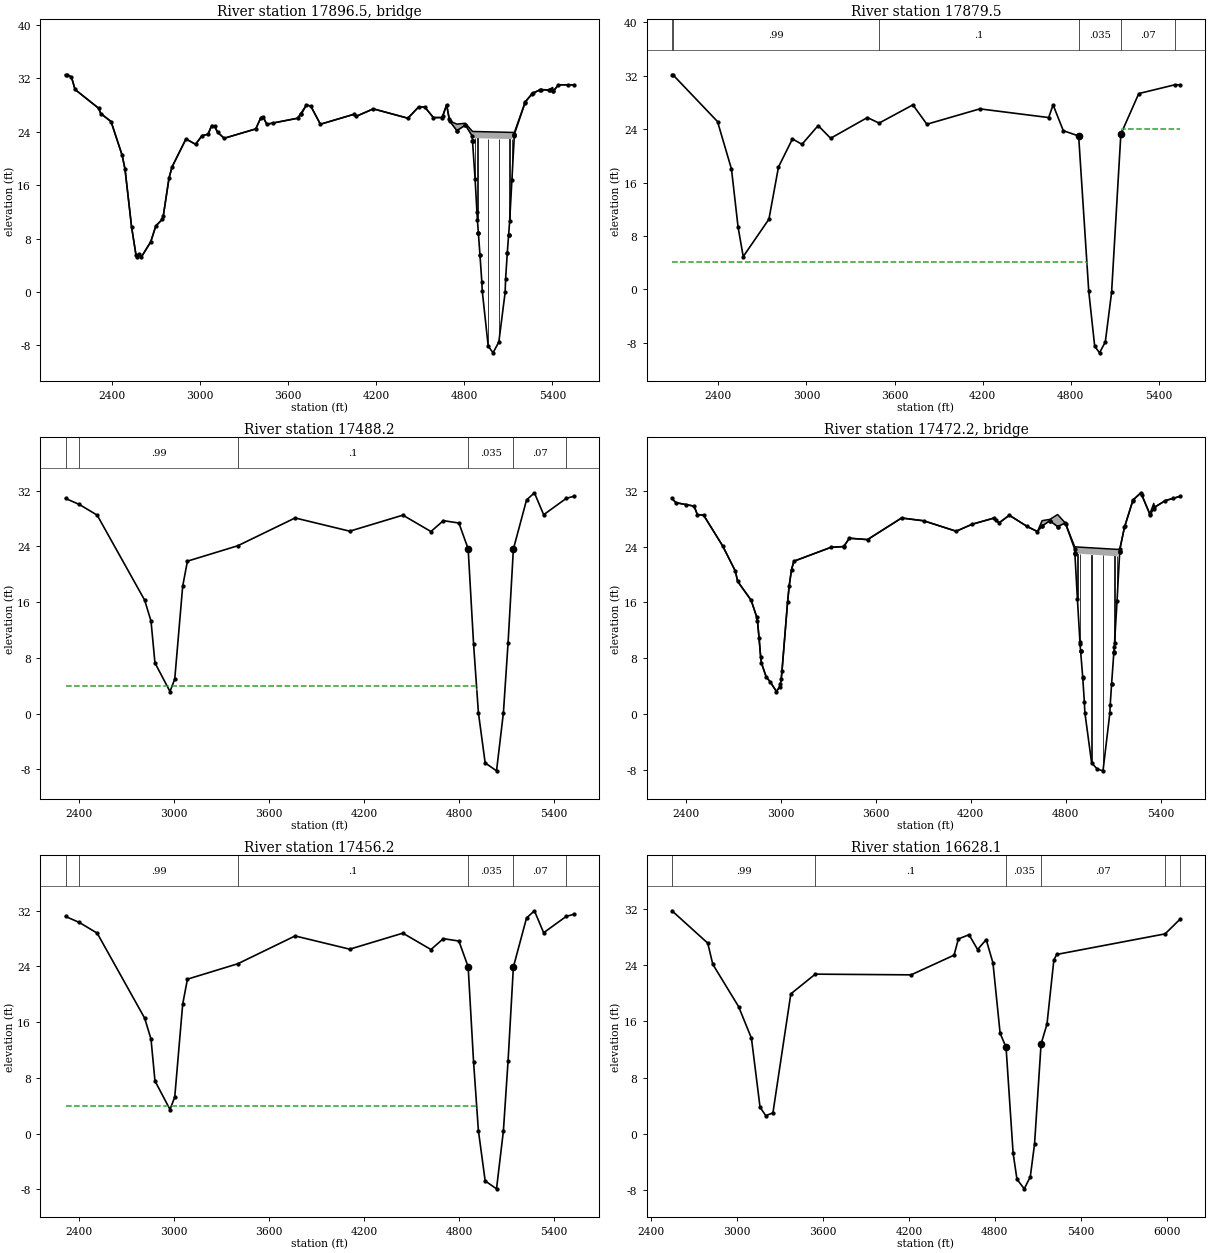
Type RM Length L Ch R = 3 ,17896.5 ,,,
BEGIN DESCRIPTION:
GLENBROOK GOLFCOURSE FOOTBRIDGE #2 (DS TO US)
Structure ID: C00-9
END DESCRIPTION:
Bridge Culvert--1,0,-1,-1, 0
Deck Dist Width WeirC Skew NumUp NumDn MinLoCord MaxHiCord MaxSubmerge Is_Ogee
10,14,2.6,0, 60, 60, , , 0.95, 0, 1,1,,
  2085.1  2125.1  2150.1  2310.1  2325.1  2395.1  2470.1  2490.1  2535.1  2565.1
  2570.1  2585.1  2600.1  2665.1  2700.1  2745.1  2750.1  2790.1  2810.1  2905.1
  2970.1  3015.1  3055.1  3080.1  3100.1  3120.1  3165.1  3380.1  3415.1  3430.1
  3455.1  3665.1  3725.1  3755.1  3820.1  4050.1  4065.1  4180.7  4415.7  4489.3
  4529.3  4589.3  4649.3  4679.3  4699.8  4748.7  4807.3  4853.3 4855.51  4855.6
  5123.8  5140.6  5215.3  5262.7  5317.8  5374.5    5401  5406.8  5440.2  5543.3
    32.5    32.2    30.3    27.5    26.7    25.5    20.5    18.4     9.7     5.5
     5.3     5.7     5.2     7.5     9.9    10.9    11.3    17.1    18.7    22.9
    22.1    23.4    23.6    24.9    24.8    23.9      23    24.4    26.1    26.2
    25.1      26      28    27.8    25.1    26.6    26.3    27.4      26    27.7
    27.7    26.1    26.1   28.01    25.6   25.12   25.25   24.07   24.02   24.02
   23.88   23.88   28.47    29.7   30.29   30.25    30.6   30.07      31      31
    32.5    32.2    30.3    27.5    26.7    25.5    20.5    18.4     9.7     5.5
     5.3     5.7     5.2     7.5     9.9    10.9    11.3    17.1    18.7    22.9
    22.1    23.4    23.6    24.9    24.8    23.9      23    24.4    26.1    26.2
    25.1      26      28    27.8    25.1    26.6    26.3    27.4      26    27.7
    27.7    26.1    26.1      28   25.59   24.14   24.96   23.34   22.62   23.02
   22.88   23.62   28.46   29.69   30.28   30.18   30.09   30.07      31      31
  2085.1  2125.1  2150.1  2310.1  2325.1  2395.1  2470.1  2490.1  2535.1  2565.1
  2570.1  2585.1  2600.1  2665.1  2700.1  2745.1  2750.1  2790.1  2810.1  2905.1
  2970.1  3015.1  3055.1  3080.1  3100.1  3120.1  3165.1  3380.1  3415.1  3430.1
  3455.1  3665.1  3725.1  3755.1  3820.1  4050.1  4065.1  4180.7  4415.7  4489.3
  4529.3  4589.3  4649.3  4679.3  4699.8  4748.7  4807.3  4853.3 4855.51  4855.6
  5123.8  5140.6  5215.3  5262.7  5317.8  5374.5    5401  5406.8  5440.2  5543.3
    32.5    32.2    30.3    27.5    26.7    25.5    20.5    18.4     9.7     5.5
     5.3     5.7     5.2     7.5     9.9    10.9    11.3    17.1    18.7    22.9
    22.1    23.4    23.6    24.9    24.8    23.9      23    24.4    26.1    26.2
    25.1      26      28    27.8    25.1    26.6    26.3    27.4      26    27.7
    27.7    26.1    26.1   28.01    25.6   25.12   25.25   24.07   24.02   24.02
   23.88   23.88   28.47    29.7   30.29   30.25    30.6   30.07      31      31
   32.09   31.79   29.89   27.09   26.29   25.09   20.09   17.99    9.29    5.09
    4.89    5.29    4.79    7.09    9.49   10.49   10.89   16.69   18.29   22.49
   21.69   22.99   23.19   24.49   24.39   23.49   22.59   23.99   25.69   25.79
   24.69   25.59   27.59   27.39   24.69   26.19   25.89   26.99   25.59   27.29
   27.29   25.69   25.69   27.59   25.18   23.73   24.55   22.93   22.21   22.61
   22.47   23.21   28.05   29.28   29.87   29.77   29.68   29.66   30.59   30.59
Pier Skew, UpSta & Num, DnSta & Num=  ,4873.2, 2 ,4873.2, 2 , 0 , 0 , 0 ,,
       1       1
   15.69   24.01
       1       1
   15.28    23.6
Pier Skew, UpSta & Num, DnSta & Num=  ,4889.1, 2 ,4889.1, 2 , 0 , 0 , 0 ,,
       2       2
    9.42      24
       2       2
    9.01   23.59
Pier Skew, UpSta & Num, DnSta & Num=  ,4962.4, 2 ,4962.4, 2 , 0 , 0 , 0 ,,
       2       2
   -9.12   23.96
       2       2
   -9.53   23.55
Pier Skew, UpSta & Num, DnSta & Num=  ,5034.8, 2 ,5034.8, 2 , 0 , 0 , 0 ,,
       2       2
   -8.51   23.93
       2       2
   -8.92   23.52
Pier Skew, UpSta & Num, DnSta & Num=  ,5108.3, 2 ,5108.3, 2 , 0 , 0 , 0 ,,
       2       2
    9.29   23.89
       2       2
    8.88   23.48
Pier Skew, UpSta & Num, DnSta & Num=  ,5123.8, 2 ,5123.8, 2 , 0 , 0 , 0 ,,
       1       1
    15.6    23.9
       1       1
   15.19   23.49
Abutment Skew #Up #Dn= , 2 , 2
  4855.4  4906.5
   23.02     5.5
  4855.4  4906.5
   22.61    5.09
Abutment Skew #Up #Dn= , 2 , 2
  5092.3 5140.29
    5.86   23.41
  5092.3 5140.29
    5.45      23
BR Coef= 1 , 1 , 0 ,1.25, 0 ,,,0.8,-1,2,0,
WSPro=,,,, 1 ,,,, 0 ,,,, 0 ,,,,-1 ,-1 ,-1 , 0 , 0 , 0 , 0 , 0
BR U #Sta/Elev= 98
  2085.1    32.5  2094.6   32.43  2125.1    32.2  2150.1    30.3  2310.1    27.5
  2325.1    26.7  2395.1    25.5  2470.1    20.5  2490.1    18.4  2535.1     9.7
  2565.1     5.5  2570.1     5.3  2585.1     5.7  2600.1     5.2  2665.1     7.5
  2700.1     9.9  2745.1    10.9  2750.1    11.3  2790.1    17.1  2810.1    18.7
  2905.1    22.9  2970.1    22.1  3015.1    23.4  3055.1    23.6  3080.1    24.9
  3100.1    24.8  3120.1    23.9  3165.1      23  3380.1    24.4  3415.1    26.1
  3430.1    26.2  3455.1    25.1  3495.1   25.27  3665.1      26  3685.1    26.6
  3690.1    26.6  3725.1      28  3755.1    27.8  3820.1    25.1  4050.1    26.6
  4065.1    26.3  4180.7    27.4  4415.7      26  4489.3    27.7  4529.3    27.7
  4589.3    26.1  4649.3    26.1  4652.2   26.28  4679.3      28  4697.9   25.81
  4699.8   25.59  4748.7   24.14  4749.3   24.15  4805.2   24.93  4807.3   24.96
  4853.3   23.34  4855.4   22.66 4855.51   22.62  4855.6   22.59  4873.2   16.89
  4885.7   11.95  4889.1   10.72 4895.39    8.83  4895.5     8.8 4895.61    8.77
  4906.4    5.53  4906.5     5.5    4919     1.5  4922.1      .1  4962.4   -8.09
  4995.3    -9.1  5034.8   -7.47  5077.5    -.07  5080.9    1.97  5092.2    5.83
  5092.3    5.86 5101.19    8.48  5101.3    8.51 5101.41    8.55  5108.3   10.58
  5123.8    16.8 5140.09   23.41  5140.2   23.46  5140.3    23.5  5140.6   23.62
  5212.3   28.27  5215.3   28.46  5262.7   29.69  5265.1   29.72  5317.8   30.28
  5320.5   30.28  5374.5   30.18  5382.3   30.17    5401   30.09  5406.8   30.07
  5440.2      31  5507.7      31  5543.3      31
BR U #Mann= 6
  2085.1     .15  2094.6     .99  3495.1      .1  4853.3    .035  5140.6     .07
  5507.7      .2
BR U Banks=4853.3,5140.6
BR D #Sta/Elev= 98
  2085.1   32.09  2094.6   32.02  2125.1   31.79  2150.1   29.89  2310.1   27.09
  2325.1   26.29  2395.1   25.09  2470.1   20.09  2490.1   17.99  2535.1    9.29
  2565.1    5.09  2570.1    4.89  2585.1    5.29  2600.1    4.79  2665.1    7.09
  2700.1    9.49  2745.1   10.49  2750.1   10.89  2790.1   16.69  2810.1   18.29
  2905.1   22.49  2970.1   21.69  3015.1   22.99  3055.1   23.19  3080.1   24.49
  3100.1   24.39  3120.1   23.49  3165.1   22.59  3380.1   23.99  3415.1   25.69
  3430.1   25.79  3455.1   24.69  3495.1   24.86  3665.1   25.59  3685.1   26.19
  3690.1   26.19  3725.1   27.59  3755.1   27.39  3820.1   24.69  4050.1   26.19
  4065.1   25.89  4180.7   26.99  4415.7   25.59  4489.3   27.29  4529.3   27.29
  4589.3   25.69  4649.3   25.69  4652.2   25.87  4679.3   27.59  4697.9    25.4
  4699.8   25.18  4748.7   23.73  4749.3   23.74  4805.2   24.52  4807.3   24.55
  4853.3   22.93  4855.4   22.25 4855.51   22.21  4855.6   22.18  4873.2   16.48
  4885.7   11.54  4889.1   10.31 4895.39    8.42  4895.5    8.39 4895.61    8.36
  4906.4    5.12  4906.5    5.09    4919    1.09  4922.1    -.31  4962.4    -8.5
  4995.3   -9.51  5034.8   -7.88  5077.5    -.48  5080.9    1.56  5092.2    5.42
  5092.3    5.45 5101.19    8.07  5101.3     8.1 5101.41    8.14  5108.3   10.17
  5123.8   16.39 5140.09      23  5140.2   23.05  5140.3   23.09  5140.6   23.21
  5212.3   27.86  5215.3   28.05  5262.7   29.28  5265.1   29.31  5317.8   29.87
  5320.5   29.87  5374.5   29.77  5382.3   29.76    5401   29.68  5406.8   29.66
  5440.2   30.59  5507.7   30.59  5543.3   30.59
BR D #Mann= 6
  2085.1     .15  2094.6     .99  3495.1      .1  4853.3    .035  5140.6     .07
  5507.7      .2
BR D Banks=4853.3,5140.6
BC Design=,, 0 ,, 0 ,,,,,,
BC HTab HWMax=32.45
BC Use User HTab Curves=0
BC User HTab FreeFlow(D)= 0

Type RM Length L Ch R = 1 ,17879.5 ,170.7,391.3,391.3
BEGIN DESCRIPTION:
Downstream Section of Bridge/Culvert/Weir
END DESCRIPTION:
XS GIS Cut Line= 6
       3151611.9     13817175.83      3153270.54     13815879.06
      3153445.39     13815596.71      3153435.89     13815399.01
      3153480.44     13815296.03      3154086.08     13814924.43
#Sta/Elev= 30
  2085.1   32.12  2094.6   32.05  2395.1   25.12  2490.1   18.02  2535.1    9.32
  2570.1    4.92  2745.1   10.52  2810.1   18.32  2905.1   22.52  2970.1   21.72
  3080.1   24.52  3165.1   22.62  3415.1   25.72  3495.1   24.89  3725.1   27.62
  3820.1   24.72  4180.7   27.02  4649.3   25.72  4679.3   27.62  4748.7   23.76
  4853.3   22.96  4922.1    -.28  4962.4   -8.47  4995.3   -9.48  5034.8   -7.85
  5077.5    -.45  5140.6   23.24  5262.7   29.31  5507.7   30.62  5543.3   30.62
#Mann= 6 ,-1 , 0
  2085.1     .15       0  2094.6     .99       0  3495.1      .1       0
  4853.3    .035       0  5140.6     .07       0  5507.7      .2       0
#XS Ineff= 2 , 0
       0    4911    4.04    5150       0   24.04
Permanent Ineff=
       F       F
Bank Sta=4853.3,5140.6
XS Rating Curve= 0 ,0
Exp/Cntr=0.5,0.3

Type RM Length L Ch R = 1 ,17488.2 ,32,32,32
BEGIN DESCRIPTION:
Upstream Section of Bridge/Culvert/Weir
END DESCRIPTION:
XS GIS Cut Line= 6
      3151750.29     13817252.56      3153294.09      13815881.8
      3153577.67     13815670.98      3153845.54     13815532.35
      3154044.92     13815427.12      3154275.32     13815298.96
#Sta/Elev= 30
  2313.9   30.87  2401.5      30  2513.9   28.47  2813.9   16.27  2853.9   13.27
  2878.9    7.27  2973.9    3.17  3003.9    4.97  3053.9   18.27  3083.9   21.87
  3402.1   24.08  3763.9   28.07  4108.9   26.17  4444.6   28.47  4621.9   26.12
  4700.3   27.68  4798.3   27.34  4856.9   23.64    4891   10.02  4921.6     .14
  4964.3   -7.07  5036.1   -8.21  5079.5     .11  5109.1   10.19  5142.5    23.6
  5225.5   30.64  5275.3   31.68  5333.7   28.53    5476   30.87  5522.5   31.17
#Mann= 6 , 1 , 0
  2313.9     .15       0  2401.5     .99       0  3402.1      .1       0
  4856.9    .035       0  5142.5     .07       0    5476      .2       0
#XS Ineff= 2 , 0
       0    4912       4    5152       0    23.6
Permanent Ineff=
       F       F
Bank Sta=4856.9,5142.5
XS Rating Curve= 0 ,0
Exp/Cntr=0.5,0.3

Type RM Length L Ch R = 3 ,17472.2 ,,,
BEGIN DESCRIPTION:
GLENBROOK GOLFCOURSE FOOTBRIDGE #1 (DS TO US)
Structure ID: C00-8
END DESCRIPTION:
Bridge Culvert--1,0,-1,-1, 0
Deck Dist Width WeirC Skew NumUp NumDn MinLoCord MaxHiCord MaxSubmerge Is_Ogee
10,12,2.6,0, 57, 57, , , 0.95, 0, 1,1,,
  2313.9  2338.9  2453.9  2473.9  2513.9  2633.9  2713.9  2728.9  2813.9  2848.9
  2853.9  2863.9  2873.9  2878.9  2908.9  2933.9  2973.9  2993.9  2998.9  3003.9
  3008.9  3043.9  3053.9  3068.9  3083.9  3318.9  3398.9  3433.9  3548.9  3763.9
  3903.9  4108.9  4208.9  4348.9  4359.6  4379.6  4444.6    4556  4621.9  4651.4
  4700.3  4749.5  4798.3  4856.9  4858.5  5124.7 5141.59  5142.5  5171.4  5225.5
  5275.3  5330.5  5333.7  5356.7  5361.3  5430.3  5522.5
    30.9    30.3    29.8    28.6    28.5    24.1    20.5      19    16.3    13.9
    13.3    10.9     8.2     7.3     5.3     4.6     3.2     3.9     4.3       5
     6.2      16    18.3    20.7    21.9    23.9      24    25.2      25    28.1
    27.7    26.2    27.2    28.1    27.8    27.4    28.5    26.9   26.15   27.72
    27.9    28.6   27.38   24.01   23.96    23.6    23.6   23.63   26.75   30.68
   31.72   28.74    28.8    30.2   29.64    30.6    31.2
    30.9    30.3    29.8    28.6    28.5    24.1    20.5      19    16.3    13.9
    13.3    10.9     8.2     7.3     5.3     4.6     3.2     3.9     4.3       5
     6.2      16    18.3    20.7    21.9    23.9      24    25.2      25    28.1
    27.7    26.2    27.2    28.1    27.8    27.4    28.5    26.9   26.15   26.93
   27.71   26.88   27.37   23.67   23.02    22.6   23.25   23.63   26.74   30.67
   31.71   28.73   28.56   29.46   29.64    30.6    31.2
  2313.9  2338.9  2453.9  2473.9  2513.9  2633.9  2713.9  2728.9  2813.9  2848.9
  2853.9  2863.9  2873.9  2878.9  2908.9  2933.9  2973.9  2993.9  2998.9  3003.9
  3008.9  3043.9  3053.9  3068.9  3083.9  3318.9  3398.9  3433.9  3548.9  3763.9
  3903.9  4108.9  4208.9  4348.9  4359.6  4379.6  4444.6    4556  4621.9  4651.4
  4700.3  4749.5  4798.3  4856.9  4858.5  5124.7 5141.59  5141.8  5142.5  5171.4
  5225.5  5275.3  5333.7  5356.7  5361.3  5430.3  5522.5
   31.15   30.55   30.05   28.85   28.75   24.35   20.75   19.25   16.55   14.15
   13.55   11.15    8.45    7.55    5.55    4.85    3.45    4.15    4.55    5.25
    6.45   16.25   18.55   20.95   22.15   24.15   24.25   25.45   25.25   28.35
   27.95   26.45   27.45   28.35   28.05   27.65   28.75   27.15    26.4   27.72
   27.96    28.6   27.62   24.01   23.96    23.6    23.6    23.6   23.88   26.99
   30.92   31.96   28.81    30.2   29.89   30.85   31.45
   31.15   30.55   30.05   28.85   28.75   24.35   20.75   19.25   16.55   14.15
   13.55   11.15    8.45    7.55    5.55    4.85    3.45    4.15    4.55    5.25
    6.45   16.25   18.55   20.95   22.15   24.15   24.25   25.45   25.25   28.35
   27.95   26.45   27.45   28.35   28.05   27.65   28.75   27.15    26.4   27.18
   27.96   27.13   27.62   23.92   23.27   22.85    23.5   23.59   23.88   26.99
   30.92   31.96   28.81   29.71   29.89   30.85   31.45
Pier Skew, UpSta & Num, DnSta & Num=  ,4874.6, 2 ,4874.6, 2 , 0 , 0 , 0 ,,
       1       1
   15.24   23.96
       1       1
   15.49   24.21
Pier Skew, UpSta & Num, DnSta & Num=  ,4890.3, 2 ,4890.3, 2 , 0 , 0 , 0 ,,
       2       2
    8.97   23.96
       2       2
    9.22   24.21
Pier Skew, UpSta & Num, DnSta & Num=  ,4964.3, 2 ,4964.3, 2 , 0 , 0 , 0 ,,
       2       2
   -8.06   23.84
       2       2
   -7.81   24.09
Pier Skew, UpSta & Num, DnSta & Num=  ,5036.1, 2 ,5036.1, 2 , 0 , 0 , 0 ,,
       2       2
   -9.17   23.72
       2       2
   -8.92   23.97
Pier Skew, UpSta & Num, DnSta & Num=  ,5109.1, 2 ,5109.1, 2 , 0 , 0 , 0 ,,
       2       2
     8.9    23.6
       2       2
    9.15   23.85
Pier Skew, UpSta & Num, DnSta & Num=  ,5124.7, 2 ,5124.7, 2 , 0 , 0 , 0 ,,
       1       1
   14.96   23.62
       1       1
   15.21   23.87
Abutment Skew #Up #Dn= , 2 , 2
  4858.3  4908.2
   23.02    5.21
  4858.3  4908.2
   23.27    5.46
Abutment Skew #Up #Dn= , 2 , 2
  5090.5 5141.79
    4.33   23.25
  5090.5 5141.79
    4.58    23.5
BR Coef= 1 , 1 , 0 ,1.25, 0 ,,,0.8,-1,2,0,
WSPro=,,,, 1 ,,,, 0 ,,,, 0 ,,,,-1 ,-1 ,-1 , 0 , 0 , 0 , 0 , 0
BR U #Sta/Elev= 93
  2313.9    30.9  2338.9    30.3  2401.5   30.03  2453.9    29.8  2473.9    28.6
  2513.9    28.5  2633.9    24.1  2713.9    20.5  2728.9      19  2813.9    16.3
  2848.9    13.9  2853.9    13.3  2863.9    10.9  2873.9     8.2  2878.9     7.3
  2908.9     5.3  2933.9     4.6  2973.9     3.2  2993.9     3.9  2998.9     4.3
  3003.9       5  3008.9     6.2  3043.9      16  3053.9    18.3  3068.9    20.7
  3083.9    21.9  3318.9    23.9  3398.9      24  3402.1   24.11  3433.9    25.2
  3548.9      25  3763.9    28.1  3903.9    27.7  4108.9    26.2  4208.9    27.2
  4348.9    28.1  4359.6    27.8  4379.6    27.4  4444.6    28.5    4556    26.9
  4621.9   26.15  4651.4   26.93  4651.7   26.94  4700.3   27.71  4700.8    27.7
  4748.8   26.87  4749.5   26.88  4798.3   27.37  4799.8   27.28  4856.9   23.67
 4858.41   23.05  4858.5   23.02  4858.6   22.97  4874.6   16.43  4890.4   10.36
    4891   10.05 4894.59    9.04  4894.7    9.01 4894.81    8.98  4908.1    5.24
  4908.2    5.21  4918.2    1.75  4921.6     .17  4964.3   -7.04  5000.5   -7.94
  5036.1   -8.18  5079.5     .14  5081.7    1.27  5090.4     4.3  5090.5    4.33
 5104.59    8.79  5104.7    8.82 5104.81    8.86  5107.1    9.58  5109.1   10.22
  5124.7   16.15 5141.59   23.25  5141.7   23.29  5141.8   23.34  5142.5   23.63
  5171.4   26.74  5173.7   26.91  5224.6    30.6  5225.5   30.67  5275.3   31.71
  5280.4   31.43  5330.5   28.73  5333.7   28.56  5356.7   29.46  5361.3   29.64
  5430.3    30.6    5476    30.9  5522.5    31.2
BR U #Mann= 6
  2313.9     .15  2401.5     .99  3402.1      .1  4856.9    .035  5142.5     .07
    5476      .2
BR U Banks=4856.9,5142.5
BR D #Sta/Elev= 93
  2313.9   31.15  2338.9   30.55  2401.5   30.28  2453.9   30.05  2473.9   28.85
  2513.9   28.75  2633.9   24.35  2713.9   20.75  2728.9   19.25  2813.9   16.55
  2848.9   14.15  2853.9   13.55  2863.9   11.15  2873.9    8.45  2878.9    7.55
  2908.9    5.55  2933.9    4.85  2973.9    3.45  2993.9    4.15  2998.9    4.55
  3003.9    5.25  3008.9    6.45  3043.9   16.25  3053.9   18.55  3068.9   20.95
  3083.9   22.15  3318.9   24.15  3398.9   24.25  3402.1   24.36  3433.9   25.45
  3548.9   25.25  3763.9   28.35  3903.9   27.95  4108.9   26.45  4208.9   27.45
  4348.9   28.35  4359.6   28.05  4379.6   27.65  4444.6   28.75    4556   27.15
  4621.9    26.4  4651.4   27.18  4651.7   27.19  4700.3   27.96  4700.8   27.95
  4748.8   27.12  4749.5   27.13  4798.3   27.62  4799.8   27.53  4856.9   23.92
 4858.41    23.3  4858.5   23.27  4858.6   23.22  4874.6   16.68  4890.4   10.61
    4891    10.3 4894.59    9.29  4894.7    9.26 4894.81    9.23  4908.1    5.49
  4908.2    5.46  4918.2       2  4921.6     .42  4964.3   -6.79  5000.5   -7.69
  5036.1   -7.93  5079.5     .39  5081.7    1.52  5090.4    4.55  5090.5    4.58
 5104.59    9.04  5104.7    9.07 5104.81    9.11  5107.1    9.83  5109.1   10.47
  5124.7    16.4 5141.59    23.5  5141.7   23.54  5141.8   23.59  5142.5   23.88
  5171.4   26.99  5173.7   27.16  5224.6   30.85  5225.5   30.92  5275.3   31.96
  5280.4   31.68  5330.5   28.98  5333.7   28.81  5356.7   29.71  5361.3   29.89
  5430.3   30.85    5476   31.15  5522.5   31.45
BR D #Mann= 6
  2313.9     .15  2401.5     .99  3402.1      .1  4856.9    .035  5142.5     .07
    5476      .2
BR D Banks=4856.9,5142.5
BC Design=,, 0 ,, 0 ,,,,,,
BC HTab HWMax=31.68
BC Use User HTab Curves=0
BC User HTab FreeFlow(D)= 0

Type RM Length L Ch R = 1 ,17456.2 ,220.6,828.1,828.1
BEGIN DESCRIPTION:
Downstream Section of Bridge/Culvert/Weir
END DESCRIPTION:
XS GIS Cut Line= 6
      3151762.67     13817282.06      3153306.47      13815911.3
      3153590.05     13815700.48      3153857.92     13815561.85
       3154057.3     13815456.62       3154287.7     13815328.47
#Sta/Elev= 30
  2313.9   31.15  2401.5   30.28  2513.9   28.75  2813.9   16.55  2853.9   13.55
  2878.9    7.55  2973.9    3.45  3003.9    5.25  3053.9   18.55  3083.9   22.15
  3402.1   24.36  3763.9   28.35  4108.9   26.45  4444.6   28.75  4621.9    26.4
  4700.3   27.96  4798.3   27.62  4856.9   23.92    4891    10.3  4921.6     .42
  4964.3   -6.79  5036.1   -7.93  5079.5     .39  5109.1   10.47  5142.5   23.88
  5225.5   30.92  5275.3   31.96  5333.7   28.81    5476   31.15  5522.5   31.45
#Mann= 6 ,-1 , 0
  2313.9     .15       0  2401.5     .99       0  3402.1      .1       0
  4856.9    .035       0  5142.5     .07       0    5476      .2       0
#XS Ineff= 2 , 0
       0    4912       4    5152       0    23.6
Permanent Ineff=
       F       F
Bank Sta=4856.9,5142.5
XS Rating Curve= 0 ,0
Exp/Cntr=0.5,0.3

Type RM Length L Ch R = 1 ,16628.1 ,2109.3,611.8,556.7
BEGIN DESCRIPTION:
Cross Section 16628.1
END DESCRIPTION:
XS GIS Cut Line= 6
      3151838.56     13817233.97      3153743.35     13816412.79
       3153900.6     13816410.53      3154311.33     13816285.22
      3154778.54     13815962.81      3154848.89     13815652.21
#Sta/Elev= 30
  2545.7    31.7  2795.7    27.1  2830.7    24.1  3010.7    18.1  3100.7    13.6
  3160.7     3.8  3200.7     2.6  3250.7       3  3375.7    19.9  3546.4    22.7
  4215.7    22.6  4515.7    25.4  4545.7    27.7    4620    28.3    4680    26.2
    4740    27.6  4787.2    24.3  4837.2    14.3  4878.6   12.33  4927.9   -2.71
  4954.8   -6.42  5005.7   -7.79  5047.9   -6.08  5077.7   -1.42  5123.3    12.8
  5164.5    15.6  5212.4    24.7  5232.4    25.5  5989.5   28.42  6093.5    30.5
#Mann= 6 ,-1 , 0
  2545.7     .99       0  3546.4      .1       0  4878.6    .035       0
  5123.3     .07       0  5989.5      .1       0  6093.5      .2       0
Bank Sta=4878.6,5123.3
XS Rating Curve= 0 ,0
Exp/Cntr=0.3,0.1