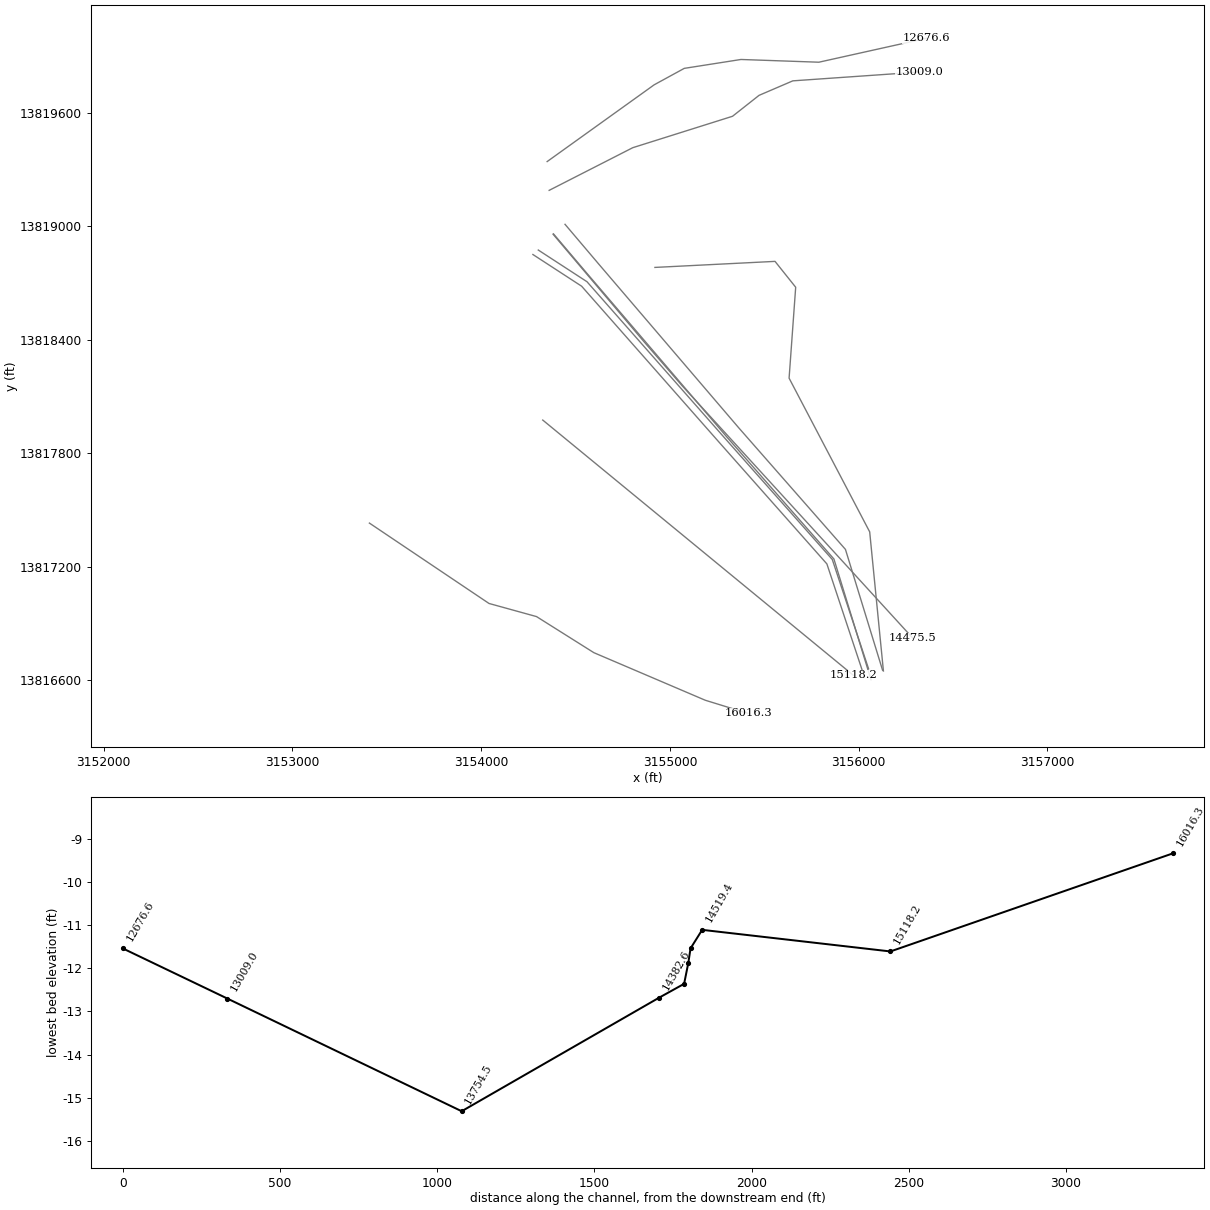
HEC-RAS study C100-00-00.prj: C100-00-00

--- C100-00-00.g01 (geometry) --- (continued)

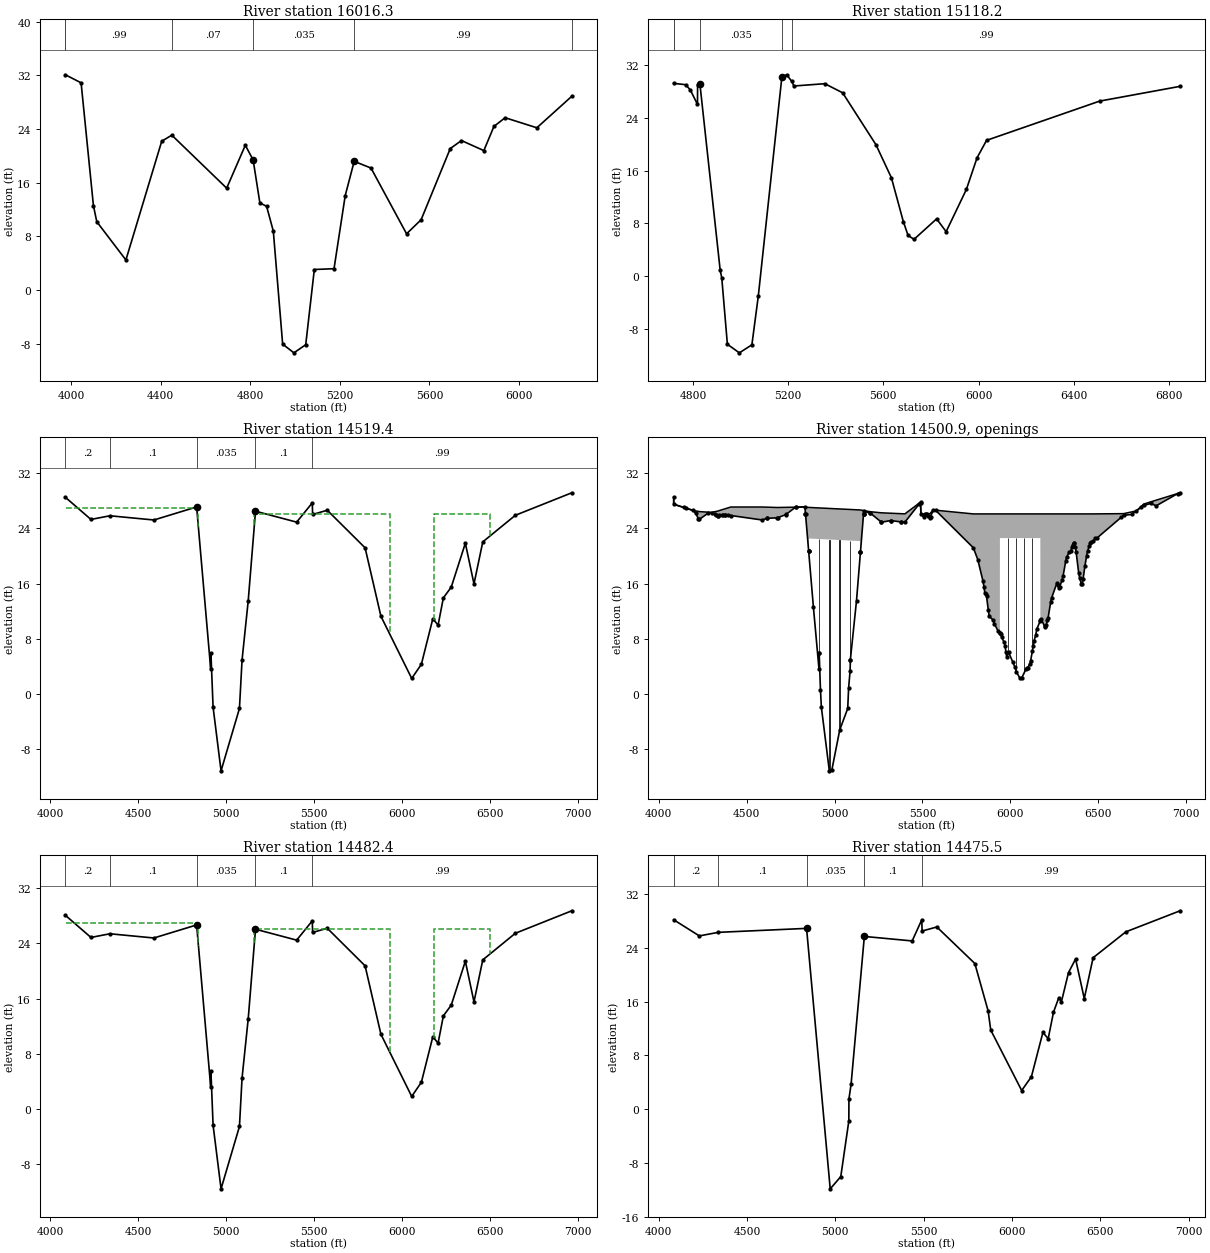
Type RM Length L Ch R = 1 ,16016.3 ,990,898.1,898
BEGIN DESCRIPTION:
Cross Section 16016.3-Interpolated
END DESCRIPTION:
XS GIS Cut Line= 6
      3153407.99     13817430.11      3154041.67     13817004.76
      3154293.41     13816935.31      3154597.23     13816744.34
       3155187.5     13816492.61       3155413.2     13816423.16
#Sta/Elev= 30
  3974.5    32.1  4044.5    30.9  4099.5    12.6  4114.5    10.2  4244.5     4.5
  4404.5    22.2  4449.5    23.1  4694.5    15.2  4777.7    21.6  4812.7    19.4
  4842.7      13  4872.7    12.5  4902.7     8.8  4944.4   -8.04  4994.7   -9.34
  5047.4   -8.13  5085.8    3.08  5173.8     3.2  5223.8    14.1  5263.8    19.2
  5338.8    18.2  5497.7     8.4  5562.7    10.5  5692.7    21.1  5742.7    22.3
  5842.7    20.8  5887.7    24.4  5937.7    25.7  6079.4    24.2  6235.5    28.9
#Mann= 6 , 1 , 0
  3974.5      .2       0  3974.5     .99       0  4449.5     .07       0
  4812.7    .035       0  5263.8     .99       0  6235.5      .2       0
Bank Sta=4812.7,5263.8
XS Rating Curve= 0 ,0
Exp/Cntr=0.3,0.1

Type RM Length L Ch R = 1 ,15118.2 ,591.6,598.8,538.9
BEGIN DESCRIPTION:
Cross Section 15118.2
END DESCRIPTION:
XS GIS Cut Line= 3
      3154326.36     13817975.24      3154709.09     13817661.11
      3155971.65     13816624.85
#Sta/Elev= 30
  4718.8    29.2  4768.8      29  4788.8    28.2  4818.8      26  4819.2      29
  4828.9   29.13  4914.2     .89  4920.9    -.28  4944.4  -10.31  4994.7  -11.61
  5047.4   -10.4  5074.4   -3.01  5173.6   30.21  5193.8    30.5  5215.1    29.5
  5223.9    28.8  5353.9   29.15  5428.9   27.77  5568.9   19.91  5633.9    14.9
  5683.9    8.28  5703.9    6.17  5728.9    5.58  5823.9    8.68  5863.9    6.74
  5948.9   13.13  5993.9   17.93  6033.9   20.57  6508.9   26.51  6847.3   28.75
#Mann= 5 , 1 , 0
  4718.8      .2       0  4718.8      .1       0  4828.9    .035       0
  5173.6      .1       0  5215.1     .99       0
Bank Sta=4828.9,5173.6
XS Rating Curve= 0 ,0
Exp/Cntr=0.5,0.3

Type RM Length L Ch R = 1 ,14519.4 ,37,37,37
BEGIN DESCRIPTION:
Upstream Section of Bridge/Culvert/Weir
END DESCRIPTION:
XS GIS Cut Line= 6
      3154274.21     13818851.32      3154532.36     13818683.58
      3155134.67     13818000.77      3155267.99     13817849.64
      3155831.81     13817213.95      3156024.02     13816635.57
#Sta/Elev= 30
  4085.6   28.49  4230.7   25.29  4338.5   25.82  4588.5   25.21  4831.6    27.1
  4911.5    3.66  4912.7    5.97  4925.1   -1.89  4970.4  -11.11    5075   -2.08
  5089.8    4.94  5124.9   13.53  5166.2   26.48  5400.2    24.9  5489.2   27.69
  5490.9   26.01  5574.3   26.62  5789.3   21.18  5879.3   11.27  6054.3    2.27
  6109.3    4.32  6174.3   10.91  6204.3    9.99  6234.3   13.93  6279.3    15.5
  6359.3   21.85  6408.4   15.96  6458.4   22.04  6643.4   25.89  6964.6   29.15
#Mann= 5 , 1 , 0
  4085.6      .2       0  4338.5      .1       0  4831.6    .035       0
  5166.2      .1       0  5489.2     .99       0
#XS Ineff= 3 ,-1
    4088    4842   26.94    5160    5930    26.1    6180    6500    26.1
Permanent Ineff=
       F       F       F
Bank Sta=4831.6,5166.2
XS Rating Curve= 0 ,0
Exp/Cntr=0.5,0.3

Type RM Length L Ch R = 4 ,14500.9 ,,,
BEGIN DESCRIPTION:
RAILROAD AT GALVESTON ROAD
Structure ID: C00-7A
END DESCRIPTION:
Bridge Culvert--1,0,-1,-1, 0
Deck Dist Width WeirC Skew NumUp NumDn MinLoCord MaxHiCord MaxSubmerge Is_Ogee
10,17,2.6,0, 60, 60, , , 0.95, 0, 1,1,,
  4085.6  4085.7  4195.7  4230.7  4300.7  4335.7  4410.2  4588.5  4675.3  4778.2
  4831.6 4852.71  4852.8 5147.29  5147.4  5166.2  5203.8  5266.6  5400.2  5489.1
  5490.9  5505.9  5520.9  5540.9  5560.9  5574.3  5789.3  5814.3  5844.3  5854.3
  5864.3  5879.3  5899.3 5940.11  5940.2 6170.09  6170.2  6174.3  6199.3  6214.3
  6234.3  6264.3  6274.3  6279.3  6294.3  6319.3  6344.3  6359.3  6368.4  6393.4
  6403.4  6408.4  6438.4  6458.4  6643.4  6715.1  6758.4  6798.4  6828.4  6964.6
    28.5    27.5   26.61   26.44   26.32   26.51    27.1    27.1   27.03   27.08
   27.12   27.04   27.04   26.67   26.67   26.58   26.42   26.26   26.11   27.81
    26.1    26.1   26.14    26.1   26.65   26.64    26.1    26.1    26.1    26.1
    26.1    26.1    26.1    26.1    26.1    26.1    26.1    26.1    26.1    26.1
    26.1    26.1    26.1    26.1    26.1    26.1    26.1    26.1    26.1    26.1
    26.1    26.1    26.1    26.1   26.14   26.53   27.53   27.85   28.09   29.16
    28.5    27.5    26.6    25.3    26.3    25.8   25.87   25.22   25.53   27.07
   27.11   20.76   22.54   22.17    20.6   26.49   26.21    24.9   24.91    27.8
   26.02    25.7   26.13   25.57   26.64   26.63   21.19   19.49   16.34   14.71
   14.15   11.28   10.78    8.85    22.6    22.6   10.67   10.92    9.68   11.08
   13.94    16.1    15.4   15.51   16.56   19.84   20.76   21.86   21.34   16.85
   15.93   15.97   20.73   22.05    25.9   26.52   27.33   27.62   27.27   29.16
  4085.6  4085.7  4195.7  4230.7  4300.7  4335.7  4410.2  4588.5  4675.3  4778.2
  4831.6 4852.71  4852.8 5147.29  5147.4  5166.2  5203.8  5266.6  5400.2  5489.1
  5490.9  5505.9  5520.9  5540.9  5560.9  5574.3  5789.3  5814.3  5844.3  5854.3
  5864.3  5879.3  5899.3 5940.11  5940.2 6170.09  6170.2  6174.3  6199.3  6214.3
  6234.3  6264.3  6274.3  6279.3  6294.3  6319.3  6344.3  6359.3  6368.4  6393.4
  6403.4  6408.4  6438.4  6458.4  6643.4  6715.1  6758.4  6798.4  6828.4  6964.6
   28.54   27.54   26.64   26.44   26.34   26.51    27.1    27.1   27.03   27.11
   27.15   27.04   27.04   26.67   26.67   26.58   26.42   26.26   26.11   27.84
    26.1    26.1   26.17    26.1   26.68   26.67    26.1    26.1    26.1    26.1
    26.1    26.1    26.1    26.1    26.1    26.1    26.1    26.1    26.1    26.1
    26.1    26.1    26.1    26.1    26.1    26.1    26.1    26.1    26.1    26.1
    26.1    26.1    26.1    26.1   26.14   26.56   27.53   27.85   28.09    29.2
   28.54   27.54   26.64   25.34   26.34   25.84   25.91   25.26   25.57   27.11
   27.15    20.8   22.58   22.21   20.64   26.53   26.25   24.94   24.95   27.84
   26.06   25.74   26.17   25.61   26.68   26.67   21.23   19.53   16.38   14.75
   14.19   11.32   10.82    8.89   22.64   22.64   10.71   10.96    9.72   11.12
   13.98   16.14   15.44   15.55    16.6   19.88    20.8    21.9   21.38   16.89
   15.97   16.01   20.77   22.09   25.94   26.56   27.37   27.66   27.31    29.2
Pier Skew, UpSta & Num, DnSta & Num=  ,4911.5, 2 ,4911.5, 2 , 0 , 0 , 0 ,,
       4       4
    3.23   23.47
       4       4
    3.27   23.51
Pier Skew, UpSta & Num, DnSta & Num=  ,4970.4, 2 ,4970.4, 2 , 0 , 0 , 0 ,,
       4       4
  -12.08   23.39
       4       4
  -12.04   23.43
Pier Skew, UpSta & Num, DnSta & Num=  ,5029.6, 2 ,5029.6, 2 , 0 , 0 , 0 ,,
       4       4
   -6.43   23.32
       4       4
   -6.39   23.36
Pier Skew, UpSta & Num, DnSta & Num=  ,5088.6, 2 ,5088.6, 2 , 0 , 0 , 0 ,,
       4       4
    1.83   23.24
       4       4
    1.87   23.28
Pier Skew, UpSta & Num, DnSta & Num=  ,5985.3, 2 ,5985.3, 2 , 0 , 0 , 0 ,,
       2       2
    4.72    23.6
       2       2
    4.76   23.64
Pier Skew, UpSta & Num, DnSta & Num=  ,6031.3, 2 ,6031.3, 2 , 0 , 0 , 0 ,,
       2       2
    2.38    23.6
       2       2
    2.42   23.64
Pier Skew, UpSta & Num, DnSta & Num=  ,6077.3, 2 ,6077.3, 2 , 0 , 0 , 0 ,,
       2       2
    1.99    23.6
       2       2
    2.03   23.64
Pier Skew, UpSta & Num, DnSta & Num=  ,6123.3, 2 ,6123.3, 2 , 0 , 0 , 0 ,,
       2       2
     4.9    23.6
       2       2
    4.94   23.64
Abutment Skew #Up #Dn= , 2 , 2
  4852.6  4912.8
   22.54    5.91
  4852.6  4912.8
   22.58    5.95
Abutment Skew #Up #Dn= , 2 , 2
  5089.9 5147.49
    4.97   22.17
  5089.9 5147.49
    5.01   22.21
Abutment Skew #Up #Dn= , 2 , 2
    5940  6014.2
    22.6     4.6
    5940  6014.2
   22.64    4.64
Abutment Skew #Up #Dn= , 2 , 2
  6094.2 6170.29
    3.76    22.6
  6094.2 6170.29
     3.8   22.64
BR Coef= 1 , 1 , 0 ,1.25, 0 ,,,0.8,-1,2,0,
WSPro=,,,, 1 ,,,, 0 ,,,, 0 ,,,,-1 ,-1 ,-1 , 0 , 0 , 0 , 0 , 0
BR Coef= 1 , 1 , 0 ,1.25, 0 ,,,0.8,0,2,0,
WSPro=,,,, 1 ,,,, 0 ,,,, 0 ,,,,-1 ,-1 ,-1 , 0 , 0 , 0 , 0 , 0
BC Mult= 3 ,3085.6,5675.97,3085.6,5675.97
BC Mult= 3 ,5411.73,7964.6,5411.73,7964.6
BR U #Sta/Elev= 167
  4085.6    28.5  4085.7    27.5  4142.9   27.03  4152.9   26.95  4195.7    26.6
  4210.7    26.2  4225.7    25.4  4230.7    25.3  4280.7    26.2  4300.7    26.3
  4317.9   26.05  4327.9   25.91  4335.7    25.8  4338.5   25.83  4345.7    25.9
  4357.9   25.94  4367.9   25.97    4376      26  4377.9   25.99  4393.4   25.94
  4410.2   25.87  4588.5   25.22  4615.6   25.47  4615.9   25.47  4675.3   25.53
  4677.2   25.55  4722.7   26.01  4723.4   26.02  4778.2   27.07  4780.7   27.07
  4831.6   27.11 4834.79   26.15  4834.9   26.12 4835.01   26.08  4852.6    20.8
 4852.71   20.76  4852.8   20.74    4880   12.56  4911.5    3.67  4912.7    5.98
  4912.8    5.91    4920     .62  4925.1   -1.88  4970.4   -11.1    4985  -10.94
  5029.6   -5.17    5075   -2.07    5080     .91  5088.6    3.41  5089.8    4.95
  5089.9    4.97  5124.9   13.54 5147.29   20.56  5147.4    20.6  5147.5   20.63
 5164.69   26.02  5164.8   26.05 5164.91   26.09  5166.2   26.49  5203.6   26.21
  5203.8   26.21  5265.3   24.93  5266.6    24.9  5319.8   25.14  5320.2   25.14
    5378   24.93  5379.9   24.93  5400.2   24.91  5480.2   27.51  5489.1    27.8
  5489.2    27.7  5490.9   26.02  5505.9    25.7  5515.9   26.06  5520.9   26.13
  5525.9   26.04  5530.9   25.78  5540.9   25.57  5545.9   25.72  5560.9   26.64
  5574.3   26.63  5789.3   21.19  5814.3   19.49  5844.3   16.34  5849.3   15.58
  5854.3   14.71  5859.3    14.5  5864.3   14.15  5874.3   12.15  5879.3   11.28
  5899.3   10.78  5909.3   10.15  5929.3    9.17 5940.11    8.85  5940.2    8.85
  5944.3    8.73  5949.3    8.31  5964.3     7.5  5969.3    7.01  5974.3     6.1
  5979.3    5.36  5989.3    6.08  6014.2     4.6  6024.3       4  6034.3    3.23
  6054.3    2.28  6064.3    2.36  6089.3    3.68  6094.2    3.76  6099.3    3.85
  6109.3    4.33  6114.3    4.76  6124.3    6.18  6129.3    7.01  6134.3     7.7
  6144.3    8.61  6149.3    9.38 6170.09   10.66  6170.2   10.67  6174.3   10.92
  6194.3     9.8  6199.3    9.68  6204.3      10  6209.3   10.68  6214.3   11.08
  6229.3   13.39  6234.3   13.94  6264.3    16.1  6269.3   15.82  6274.3    15.4
  6279.3   15.51  6294.3   16.56  6299.3   17.11  6314.3   19.25  6319.3   19.84
  6334.3   20.55  6344.3   20.76  6349.3   21.32  6354.3   21.66  6359.3   21.86
  6363.4   21.89  6368.4   21.34  6373.4   20.59  6388.4   17.49  6393.4   16.85
  6403.4   15.93  6408.4   15.97  6413.4   16.73  6423.4   18.53  6433.4   20.07
  6438.4   20.73  6448.4   21.42  6453.4   21.87  6458.4   22.05  6468.4   22.11
  6483.4   22.55  6493.4   22.64  6630.2   25.61  6643.4    25.9  6688.4   26.02
  6715.1   26.52  6745.1   27.08  6758.4   27.33  6798.4   27.62  6828.4   27.27
  6950.5   29.04  6964.6   29.16
BR U #Mann= 5
  4085.6      .2  4338.5      .1  4831.6    .035  5166.2      .1  5489.2     .99
BR U Banks=4831.6,5166.2
BR D #Sta/Elev= 167
  4085.6   28.54  4085.7   27.54  4142.9   27.07  4152.9   26.99  4195.7   26.64
  4210.7   26.24  4225.7   25.44  4230.7   25.34  4280.7   26.24  4300.7   26.34
  4317.9   26.09  4327.9   25.95  4335.7   25.84  4338.5   25.87  4345.7   25.94
  4357.9   25.98  4367.9   26.01    4376   26.04  4377.9   26.03  4393.4   25.98
  4410.2   25.91  4588.5   25.26  4615.6   25.51  4615.9   25.51  4675.3   25.57
  4677.2   25.59  4722.7   26.05  4723.4   26.06  4778.2   27.11  4780.7   27.11
  4831.6   27.15 4834.79   26.19  4834.9   26.16 4835.01   26.12  4852.6   20.84
 4852.71    20.8  4852.8   20.78    4880    12.6  4911.5    3.71  4912.7    6.02
  4912.8    5.95    4920     .66  4925.1   -1.84  4970.4  -11.06    4985   -10.9
  5029.6   -5.13    5075   -2.03    5080     .95  5088.6    3.45  5089.8    4.99
  5089.9    5.01  5124.9   13.58 5147.29    20.6  5147.4   20.64  5147.5   20.67
 5164.69   26.06  5164.8   26.09 5164.91   26.13  5166.2   26.53  5203.6   26.25
  5203.8   26.25  5265.3   24.97  5266.6   24.94  5319.8   25.18  5320.2   25.18
    5378   24.97  5379.9   24.97  5400.2   24.95  5480.2   27.55  5489.1   27.84
  5489.2   27.74  5490.9   26.06  5505.9   25.74  5515.9    26.1  5520.9   26.17
  5525.9   26.08  5530.9   25.82  5540.9   25.61  5545.9   25.76  5560.9   26.68
  5574.3   26.67  5789.3   21.23  5814.3   19.53  5844.3   16.38  5849.3   15.62
  5854.3   14.75  5859.3   14.54  5864.3   14.19  5874.3   12.19  5879.3   11.32
  5899.3   10.82  5909.3   10.19  5929.3    9.21 5940.11    8.89  5940.2    8.89
  5944.3    8.77  5949.3    8.35  5964.3    7.54  5969.3    7.05  5974.3    6.14
  5979.3     5.4  5989.3    6.12  6014.2    4.64  6024.3    4.04  6034.3    3.27
  6054.3    2.32  6064.3     2.4  6089.3    3.72  6094.2     3.8  6099.3    3.89
  6109.3    4.37  6114.3     4.8  6124.3    6.22  6129.3    7.05  6134.3    7.74
  6144.3    8.65  6149.3    9.42 6170.09    10.7  6170.2   10.71  6174.3   10.96
  6194.3    9.84  6199.3    9.72  6204.3   10.04  6209.3   10.72  6214.3   11.12
  6229.3   13.43  6234.3   13.98  6264.3   16.14  6269.3   15.86  6274.3   15.44
  6279.3   15.55  6294.3    16.6  6299.3   17.15  6314.3   19.29  6319.3   19.88
  6334.3   20.59  6344.3    20.8  6349.3   21.36  6354.3    21.7  6359.3    21.9
  6363.4   21.93  6368.4   21.38  6373.4   20.63  6388.4   17.53  6393.4   16.89
  6403.4   15.97  6408.4   16.01  6413.4   16.77  6423.4   18.57  6433.4   20.11
  6438.4   20.77  6448.4   21.46  6453.4   21.91  6458.4   22.09  6468.4   22.15
  6483.4   22.59  6493.4   22.68  6630.2   25.65  6643.4   25.94  6688.4   26.06
  6715.1   26.56  6745.1   27.12  6758.4   27.37  6798.4   27.66  6828.4   27.31
  6950.5   29.08  6964.6    29.2
BR D #Mann= 5
  4085.6      .2  4338.5      .1  4831.6    .035  5166.2      .1  5489.2     .99
BR D Banks=4831.6,5166.2
BC Design=,, 0 ,, 0 ,,,,,,
BC HTab HWMax=29.15
BC Use User HTab Curves=0
BC User HTab FreeFlow(D)= 0

Type RM Length L Ch R = 1 ,14482.4 ,6.9,6.9,6.9
BEGIN DESCRIPTION:
Downstream Section of Bridge/Culvert/Weir
END DESCRIPTION:
XS GIS Cut Line= 6
      3154302.67     13818874.97      3154560.82     13818707.24
      3155163.13     13818024.43      3155296.45      13817873.3
      3155860.27     13817237.61      3156052.48     13816659.23
#Sta/Elev= 30
  4085.6   28.06  4230.7   24.86  4338.5   25.39  4588.5   24.78  4831.6   26.67
  4911.5    3.23  4912.7    5.54  4925.1   -2.32  4970.4  -11.54    5075   -2.51
  5089.8    4.51  5124.9    13.1  5166.2   26.05  5400.2   24.47  5489.2   27.26
  5490.9   25.58  5574.3   26.19  5789.3   20.75  5879.3   10.84  6054.3    1.84
  6109.3    3.89  6174.3   10.48  6204.3    9.56  6234.3    13.5  6279.3   15.07
  6359.3   21.42  6408.4   15.53  6458.4   21.61  6643.4   25.46  6964.6   28.72
#Mann= 5 , 1 , 0
  4085.6      .2       0  4338.5      .1       0  4831.6    .035       0
  5166.2      .1       0  5489.2     .99       0
#XS Ineff= 3 ,-1
    4088    4842   26.94    5160    5930    26.1    6180    6500    26.1
Permanent Ineff=
       F       F       F
Bank Sta=4831.6,5166.2
XS Rating Curve= 0 ,0
Exp/Cntr=0.5,0.3

Type RM Length L Ch R = 1 ,14475.5 ,13.5,13.5,13.5
BEGIN DESCRIPTION:
Upstream Section of Bridge/Culvert/Weir
END DESCRIPTION:
XS GIS Cut Line= 4
      3154381.37     13818958.52       3154864.8     13818387.63
       3155063.6     13818158.32      3156287.55      13816820.5
#Sta/Elev= 30
  4085.7   28.19  4230.7   25.79  4338.5   26.32 4837.39   26.91 4971.09  -11.87
 5030.89  -10.05 5076.49   -1.75 5076.99     1.5 5089.29    3.72 5164.19   25.71
 5434.79   25.04  5489.2   28.19  5490.9   26.51  5574.3   27.12  5789.3   21.68
  5864.3   14.64  5879.3   11.77  6054.3    2.77  6109.3    4.82  6174.3   11.41
  6204.3   10.49  6234.3   14.43  6264.3   16.59  6279.3      16  6319.3   20.33
  6359.3   22.35  6408.4   16.46  6458.4   22.54  6643.4   26.39  6950.5   29.53
#Mann= 5 , 1 , 0
  4085.7      .2       0  4338.5      .1       0 4837.39    .035       0
 5164.19      .1       0  5489.2     .99       0
#XS Ineff= 3 ,-1
    4100    4831    26.4    5170    5788   21.22    6455    6640   21.85
Permanent Ineff=
       F       F       F
Bank Sta=4837.39,5164.19
XS Rating Curve= 0 ,0
Exp/Cntr=0.5,0.3

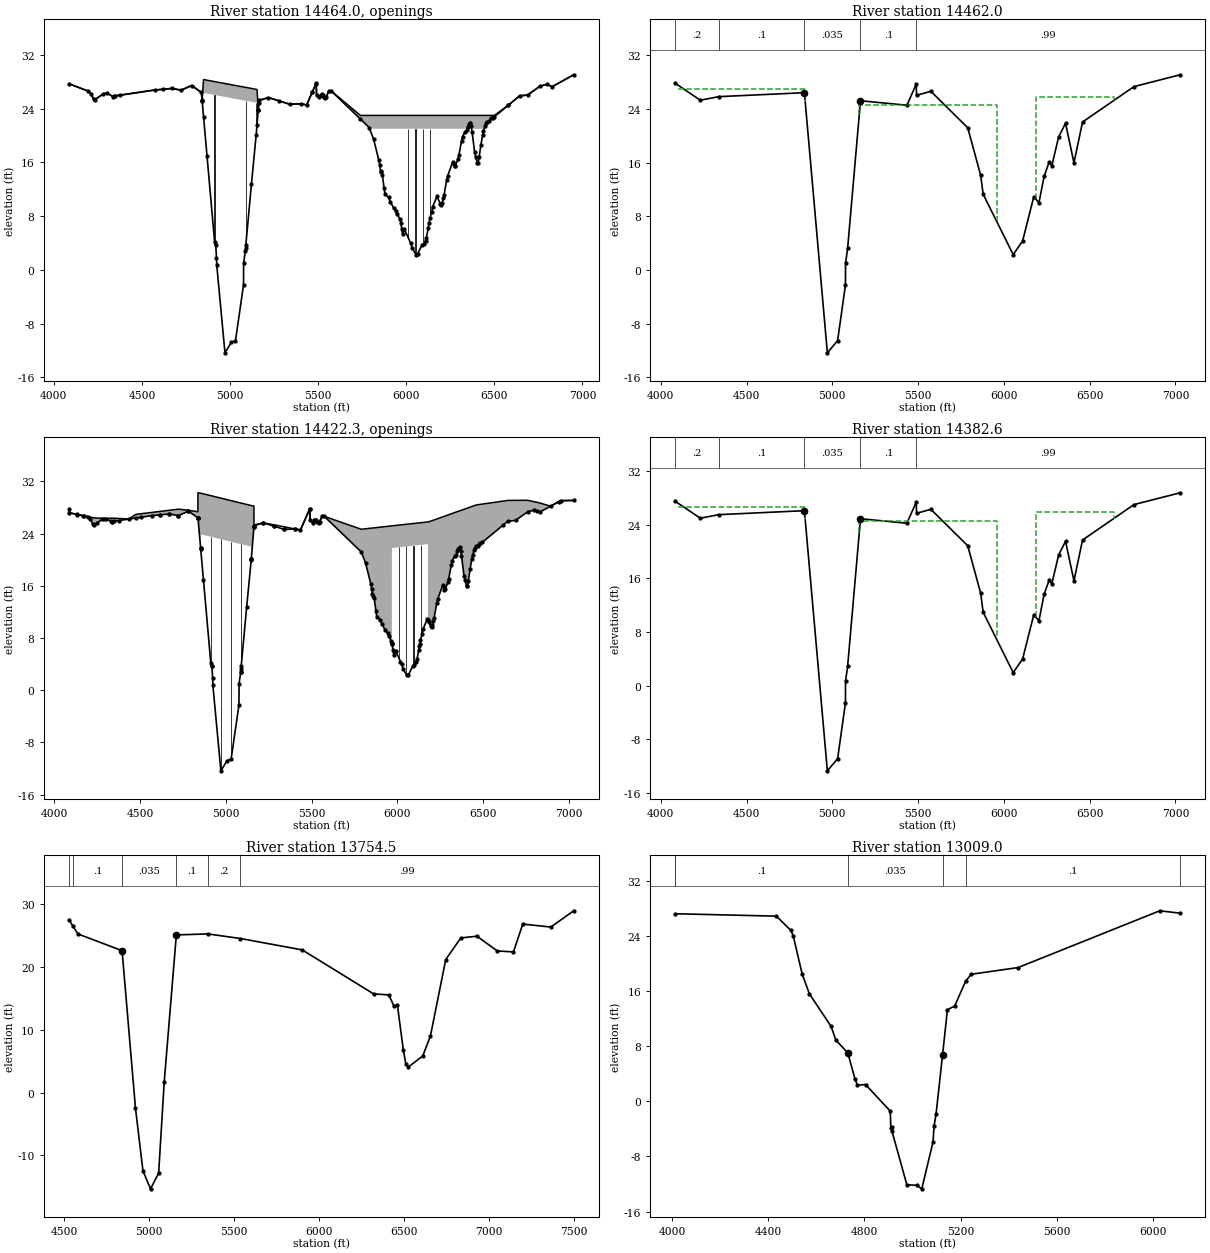
Type RM Length L Ch R = 4 ,14464.0 ,,,
BEGIN DESCRIPTION:
24" DIA. PIPE (PL2_C00-6)
END DESCRIPTION:
Bridge Culvert--1,0,-1,-1, 0
Deck Dist Width WeirC Skew NumUp NumDn MinLoCord MaxHiCord MaxSubmerge Is_Ogee
10,3,2.6,0, 59, 59, , , 0.95, 0, 1,1,,
  4085.7  4195.7  4210.7  4225.7  4230.7  4280.7  4300.7  4335.7  4345.7 4572.29
 4668.19 4722.99 4781.39 4837.39 4841.39 4841.59 4849.49 5152.99 5159.78 5159.99
 5164.19 5217.89 5338.89 5401.89 5434.79  5489.1  5490.9  5505.9  5515.9  5520.9
  5525.9  5530.9  5540.9  5545.9  5560.9  5574.3 5739.89  5789.3  5814.3  6344.3
  6354.3  6359.3  6363.4  6368.4  6373.4  6438.4  6448.4  6453.4  6458.4  6468.4
  6483.4 6499.89 6577.79  6643.4  6688.4  6758.4  6798.4  6828.4  6950.5
   27.71   26.61   26.21   25.41   25.31   26.21   26.31   25.81   25.91   26.78
   27.02   26.76   27.45   26.43   25.27   25.35   28.34   26.86   24.11   24.03
   25.23   25.66   24.66   24.73   24.56   27.81   26.03   25.71   26.07   26.14
   26.05   25.79   25.58   25.73   26.65   26.64      23      23      23      23
      23      23      23      23      23      23      23      23      23      23
      23      23   24.48   25.91   26.03   27.34   27.63   27.28   29.05
   27.71   26.61   26.21   25.41   25.31   26.21   26.31   25.81   25.91   26.78
   27.02   26.76   27.45   26.43   25.24   25.18   26.35   24.87   23.81   23.88
   25.23   25.66   24.66   24.73   24.56   27.81   26.03   25.71   26.07   26.14
   26.05   25.79   25.58   25.73   26.65   26.64   22.45    21.2   21.01   21.01
   21.67   21.87    21.9   21.35   21.01   21.01   21.43   21.88   22.06   22.12
   22.56   22.79   24.48   25.91   26.03   27.34   27.63   27.28   29.05
  4085.7  4195.7  4210.7  4225.7  4230.7  4280.7  4300.7  4335.7  4345.7 4572.29
 4668.19 4722.99 4781.39 4837.39 4841.39 4841.59 4849.49 5152.99 5159.78 5159.99
 5164.19 5217.89 5338.89 5401.89 5434.79  5489.1  5490.9  5505.9  5515.9  5520.9
  5525.9  5530.9  5540.9  5545.9  5560.9  5574.3 5739.89  5789.3  5814.3  6344.3
  6354.3  6359.3  6363.4  6368.4  6373.4  6438.4  6448.4  6453.4  6458.4  6468.4
  6483.4 6499.89 6577.79  6643.4  6688.4  6758.4  6798.4  6828.4  6950.5
    27.7    26.6    26.2    25.4    25.3    26.2    26.3    25.8    25.9   26.77
   27.01   26.75   27.44   26.42   25.27   25.35   28.34   26.86   24.11   24.03
   25.23   25.66   24.66   24.73   24.56   27.81   26.03   25.71   26.07   26.14
   26.05   25.79   25.58   25.73   26.65   26.64      23      23      23      23
      23      23      23      23      23      23      23      23      23      23
      23      23   24.47    25.9   26.02   27.33   27.62   27.27   29.04
    27.7    26.6    26.2    25.4    25.3    26.2    26.3    25.8    25.9   26.77
   27.01   26.75   27.44   26.42   25.23   25.17   26.34   24.86    23.8   23.87
   25.22   25.65   24.65   24.72   24.55    27.8   26.02    25.7   26.06   26.13
   26.04   25.78   25.57   25.72   26.64   26.63   22.44   21.19      21      21
   21.66   21.86   21.89   21.34      21      21   21.42   21.87   22.05   22.11
   22.55   22.78   24.47    25.9   26.02   27.33   27.62   27.27   29.04
Pier Skew, UpSta & Num, DnSta & Num=  ,4912.4, 2 ,4912.4, 2 , 0 , 0 , 0 ,,
     1.4     1.4
     3.1   27.04
     1.4     1.4
    3.09   27.03
Pier Skew, UpSta & Num, DnSta & Num=  ,5089.3, 2 ,5089.3, 2 , 0 , 0 , 0 ,,
     1.4     1.4
    2.13   26.18
     1.4     1.4
    2.12   26.17
Pier Skew, UpSta & Num, DnSta & Num=  ,5148.3, 2 ,5148.3, 2 , 0 , 0 , 0 ,,
     1.4     1.4
   18.92   25.89
     1.4     1.4
   18.91   25.88
Pier Skew, UpSta & Num, DnSta & Num=  ,6009.9, 2 ,6009.9, 2 , 0 , 0 , 0 ,,
     1.4     1.4
    3.82   22.01
     1.4     1.4
    3.81      22
Pier Skew, UpSta & Num, DnSta & Num=  ,6051.9, 2 ,6051.9, 2 , 0 , 0 , 0 ,,
     1.4     1.4
    1.37   22.01
     1.4     1.4
    1.36      22
Pier Skew, UpSta & Num, DnSta & Num=  ,6093.9, 2 ,6093.9, 2 , 0 , 0 , 0 ,,
     1.4     1.4
    2.76   22.01
     1.4     1.4
    2.75      22
Pier Skew, UpSta & Num, DnSta & Num=  ,6135.9, 2 ,6135.9, 2 , 0 , 0 , 0 ,,
     1.4     1.4
    6.79   22.01
     1.4     1.4
    6.78      22
BR Coef= 1 , 1 , 0 ,1.25, 0 ,,,0.8,0,2,0,
WSPro=,,,, 1 ,,,, 0 ,,,, 0 ,,,,-1 ,-1 ,-1 , 0 , 0 , 0 , 0 , 0
BR Coef= 1 , 1 , 0 ,1.25, 0 ,,,0.8,0,2,0,
WSPro=,,,, 1 ,,,, 0 ,,,, 0 ,,,,-1 ,-1 ,-1 , 0 , 0 , 0 , 0 , 0
BC Mult= 3 ,3085.7,5365.26,3085.7,5365.26
BC Mult= 3 ,5262.63,7950.5,5262.63,7950.5
BR U #Sta/Elev= 142
  4085.7   27.71  4195.7   26.61  4210.7   26.21  4225.7   25.41  4230.7   25.31
  4280.7   26.21  4300.7   26.31  4335.7   25.81  4338.5   25.84  4345.7   25.91
    4376   26.01 4572.29   26.78 4617.89   26.88 4668.19   27.02 4722.99   26.76
 4781.39   27.45 4837.39   26.43 4841.39   25.24  4841.5    25.2 4841.59   25.18
 4849.49   22.82 4869.29    16.9 4912.39    4.16 4918.69    3.66 4922.99    1.84
 4924.39     .74 4971.09  -12.35 5006.89  -10.79 5030.89  -10.53 5076.49   -2.23
 5076.99    1.02 5086.79    2.85 5089.29    3.24 5089.39    3.68 5121.39   12.78
 5148.29   20.11 5152.99   21.62 5159.78   23.81 5159.89   23.85 5159.99   23.88
 5162.89   24.81 5164.19   25.23 5217.89   25.66 5280.59   25.15 5338.89   24.66
 5401.89   24.73 5434.79   24.56 5467.81   26.54  5467.9   26.54  5489.1   27.81
  5489.2   27.71  5490.9   26.03  5505.9   25.71  5515.9   26.07  5520.9   26.14
  5525.9   26.05  5530.9   25.79 5532.89   25.75  5540.9   25.58  5545.9   25.73
  5560.9   26.65  5574.3   26.64 5739.89   22.45  5789.3    21.2  5814.3    19.5
  5844.3   16.35  5849.3   15.59  5854.3   14.72  5859.3   14.51  5864.3   14.16
  5874.3   12.16  5879.3   11.29  5899.3   10.79  5909.3   10.16  5929.3    9.18
  5944.3    8.74  5949.3    8.32  5964.3    7.51  5969.3    7.02  5974.3    6.11
  5979.3    5.37  5989.3    6.09  6024.3    4.01  6034.3    3.24  6054.3    2.29
  6064.3    2.37  6089.3    3.69  6099.3    3.86  6109.3    4.34  6114.3    4.77
  6124.3    6.19  6129.3    7.02  6134.3    7.71  6144.3    8.62  6149.3    9.39
  6174.3   10.93  6194.3    9.81  6199.3    9.69  6204.3   10.01  6209.3   10.69
  6214.3   11.09  6229.3    13.4  6234.3   13.95  6264.3   16.11  6269.3   15.83
  6274.3   15.41  6279.3   15.52  6294.3   16.57  6299.3   17.12  6314.3   19.26
  6319.3   19.85  6334.3   20.56  6344.3   20.77  6349.3   21.33  6354.3   21.67
  6359.3   21.87  6363.4    21.9  6368.4   21.35  6373.4    20.6  6388.4    17.5
  6393.4   16.86  6403.4   15.94  6408.4   15.98  6413.4   16.74  6423.4   18.54
  6433.4   20.08  6438.4   20.74  6448.4   21.43  6453.4   21.88  6458.4   22.06
  6468.4   22.12  6483.4   22.56  6493.4   22.65 6499.89   22.79 6577.79   24.48
  6577.9   24.49  6643.4   25.91  6688.4   26.03  6758.4   27.34  6798.4   27.63
  6828.4   27.28  6950.5   29.05
BR U #Mann= 5
  4085.7      .2  4338.5      .1 4837.39    .035 5164.19      .1  5489.2     .99
BR U Banks=4837.39,5164.19
BR D #Sta/Elev= 142
  4085.7    27.7  4195.7    26.6  4210.7    26.2  4225.7    25.4  4230.7    25.3
  4280.7    26.2  4300.7    26.3  4335.7    25.8  4338.5   25.83  4345.7    25.9
    4376      26 4572.29   26.77 4617.89   26.87 4668.19   27.01 4722.99   26.75
 4781.39   27.44 4837.39   26.42 4841.39   25.23  4841.5   25.19 4841.59   25.17
 4849.49   22.81 4869.29   16.89 4912.39    4.15 4918.69    3.65 4922.99    1.83
 4924.39     .73 4971.09  -12.36 5006.89   -10.8 5030.89  -10.54 5076.49   -2.24
 5076.99    1.01 5086.79    2.84 5089.29    3.23 5089.39    3.67 5121.39   12.77
 5148.29    20.1 5152.99   21.61 5159.78    23.8 5159.89   23.84 5159.99   23.87
 5162.89    24.8 5164.19   25.22 5217.89   25.65 5280.59   25.14 5338.89   24.65
 5401.89   24.72 5434.79   24.55 5467.81   26.53  5467.9   26.53  5489.1    27.8
  5489.2    27.7  5490.9   26.02  5505.9    25.7  5515.9   26.06  5520.9   26.13
  5525.9   26.04  5530.9   25.78 5532.89   25.74  5540.9   25.57  5545.9   25.72
  5560.9   26.64  5574.3   26.63 5739.89   22.44  5789.3   21.19  5814.3   19.49
  5844.3   16.34  5849.3   15.58  5854.3   14.71  5859.3    14.5  5864.3   14.15
  5874.3   12.15  5879.3   11.28  5899.3   10.78  5909.3   10.15  5929.3    9.17
  5944.3    8.73  5949.3    8.31  5964.3     7.5  5969.3    7.01  5974.3     6.1
  5979.3    5.36  5989.3    6.08  6024.3       4  6034.3    3.23  6054.3    2.28
  6064.3    2.36  6089.3    3.68  6099.3    3.85  6109.3    4.33  6114.3    4.76
  6124.3    6.18  6129.3    7.01  6134.3     7.7  6144.3    8.61  6149.3    9.38
  6174.3   10.92  6194.3     9.8  6199.3    9.68  6204.3      10  6209.3   10.68
  6214.3   11.08  6229.3   13.39  6234.3   13.94  6264.3    16.1  6269.3   15.82
  6274.3    15.4  6279.3   15.51  6294.3   16.56  6299.3   17.11  6314.3   19.25
  6319.3   19.84  6334.3   20.55  6344.3   20.76  6349.3   21.32  6354.3   21.66
  6359.3   21.86  6363.4   21.89  6368.4   21.34  6373.4   20.59  6388.4   17.49
  6393.4   16.85  6403.4   15.93  6408.4   15.97  6413.4   16.73  6423.4   18.53
  6433.4   20.07  6438.4   20.73  6448.4   21.42  6453.4   21.87  6458.4   22.05
  6468.4   22.11  6483.4   22.55  6493.4   22.64 6499.89   22.78 6577.79   24.47
  6577.9   24.48  6643.4    25.9  6688.4   26.02  6758.4   27.33  6798.4   27.62
  6828.4   27.27  6950.5   29.04
BR D #Mann= 5
  4085.7      .2  4338.5      .1 4837.39    .035 5164.19      .1  5489.2     .99
BR D Banks=4837.39,5164.19
BC Design=,, 0 ,, 0 ,,,,,,
BC HTab HWMax=29.53
BC Use User HTab Curves=0
BC User HTab FreeFlow(D)= 0

Type RM Length L Ch R = 1 ,14462.0 ,79.4,79.4,79.4
BEGIN DESCRIPTION:
Upstream Section of Bridge/Culvert/Weir
END DESCRIPTION:
XS GIS Cut Line= 5
      3154383.36     13818960.28      3154561.46     13818750.48
      3155302.33     13817885.02        3155869.     13817240.04
       3156065.7     13816600.73
#Sta/Elev= 30
  4085.6    27.8  4230.7    25.3  4338.5   25.83  4837.4   26.42  4971.1  -12.36
  5030.9  -10.54  5076.5   -2.24    5077    1.01  5089.3    3.23  5164.2   25.22
  5434.8   24.55  5489.2    27.7  5490.9   26.02  5574.3   26.63  5789.3   21.19
  5864.3   14.15  5879.3   11.28  6054.3    2.28  6109.3    4.33  6174.3   10.92
  6204.3      10  6234.3   13.94  6264.3    16.1  6279.3   15.51  6319.3   19.84
  6359.3   21.86  6408.4   15.97  6458.4   22.05  6758.4   27.33  7027.5   29.09
#Mann= 5 , 1 , 0
  4085.6      .2       0  4338.5      .1       0  4837.4    .035       0
  5164.2      .1       0  5489.2     .99       0
#XS Ineff= 3 ,-1
    4100    4842   27.02    5157    5957   24.52    6187    6640   25.85
Permanent Ineff=
       F       F       F
Bank Sta=4837.4,5164.2
XS Rating Curve= 0 ,0
Exp/Cntr=0.5,0.3

Type RM Length L Ch R = 4 ,14422.3 ,,,
BEGIN DESCRIPTION:
GALVESTON ROAD
Structure ID: C00-6
END DESCRIPTION:
Bridge Culvert--1,0,-1,-1, 0
Deck Dist Width WeirC Skew NumUp NumDn MinLoCord MaxHiCord MaxSubmerge Is_Ogee
10,59.4,2.6,0, 60, 60, , , 0.95, 0, 1,1,,
  4085.6  4085.7  4195.7  4230.7  4300.7  4335.7    4435    4475    4723  4781.5
 4837.09  4837.2  4837.4 4853.11  4853.2 5147.99  5148.1  5163.8 5163.91  5164.2
  5218.1  5434.8  5489.1  5490.9  5505.9  5520.9  5540.9  5560.9  5574.3  5789.3
  5814.3  5844.3  5854.3  5864.3  5879.3  5944.3 5967.81  5967.9 6177.79  6177.9
  6199.3  6214.3  6234.3  6264.3  6279.3  6294.3  6319.3  6359.3  6368.4  6393.4
  6408.4  6438.4  6458.4  6643.4  6688.4  6758.4  6828.4  6892.4  6950.5  7027.5
    27.8    27.2   26.61   26.42   26.31   26.38   26.24   26.95   27.75   27.58
   27.36   30.26   30.26    30.2    30.2    28.3    28.3   28.22   25.32   25.32
   25.66   24.56   27.81   26.03   25.71   26.14   25.58   26.65   26.64   24.67
   24.74   24.83   24.86   24.89   24.93   25.12   25.19   25.19   25.79   25.79
   25.96    26.1   26.29   26.57   26.71   26.85   27.09   27.46   27.55   27.78
   27.92    28.2   28.39   29.09    29.1   29.11   28.71   28.21   29.05   29.09
    27.8    27.2    26.6    25.3    26.3    25.8   26.23   26.39   26.75   27.44
   26.43   26.42   26.42   21.73    23.9      22   20.05   25.09   25.13   25.22
   25.65   24.55    27.8   26.02    25.7   26.13   25.57   26.64   26.63   21.19
   19.49   16.34   14.71   14.15   11.28    8.73    7.16   21.79   22.39   10.72
    9.68   11.08   13.94    16.1   15.51   16.56   19.84   21.86   21.34   16.85
   15.97   20.73   22.05    25.9   26.02   27.33   27.27    28.2   29.04   29.09
  4085.6  4085.7  4195.7  4230.7  4300.7  4335.7    4435    4475    4723  4781.5
 4837.09  4837.2  4837.4 4853.11  4853.2 5147.99  5148.1  5163.8 5163.91  5164.2
  5218.1  5434.8  5489.1  5490.9  5505.9  5520.9  5540.9  5560.9  5574.3  5789.3
  5814.3  5844.3  5854.3  5864.3  5879.3  5944.3 5967.81  5967.9 6177.79  6177.9
  6199.3  6214.3  6234.3  6264.3  6279.3  6294.3  6319.3  6359.3  6368.4  6393.4
  6408.4  6438.4  6458.4  6643.4  6688.4  6758.4  6828.4  6892.4  6950.5  7027.5
    27.8    27.2   26.61   26.42   26.31   26.38   26.24   26.95   27.75   27.58
   27.36   30.26   30.26    30.2    30.2    28.3    28.3   28.22   25.32   25.32
   25.66   24.56   27.81   26.03   25.71   26.14   25.58   26.65   26.64   24.67
   24.74   24.83   24.86   24.89   24.93   25.12   25.19   25.19   25.79   25.79
   25.96    26.1   26.29   26.57   26.71   26.85   27.09   27.46   27.55   27.78
   27.92    28.2   28.39   29.09    29.1   29.11   28.71   28.21   29.05   29.09
    27.5    26.9    26.3      25      26    25.5   25.93   26.09   26.45   27.14
   26.13   26.12   26.12   21.43    23.6    21.7   19.75   24.79   24.83   24.92
   25.35   24.25    27.5   25.72    25.4   25.83   25.27   26.34   26.33   20.89
   19.19   16.04   14.41   13.85   10.98    8.43    6.86   21.49   22.09   10.42
    9.38   10.78   13.64    15.8   15.21   16.26   19.54   21.56   21.04   16.55
   15.67   20.43   21.75    25.6   25.72   27.03   26.97    27.9   28.74   28.79
Pier Skew, UpSta & Num, DnSta & Num=  ,4912.4, 2 ,4912.4, 2 , 0 , 0 , 0 ,,
       2       2
    3.07   24.53
       2       2
    2.77   24.23
Pier Skew, UpSta & Num, DnSta & Num=  ,4971.1, 2 ,4971.1, 2 , 0 , 0 , 0 ,,
       2       2
  -13.32   24.15
       2       2
  -13.62   23.85
Pier Skew, UpSta & Num, DnSta & Num=  ,5030.9, 2 ,5030.9, 2 , 0 , 0 , 0 ,,
       2       2
  -11.55   23.76
       2       2
  -11.85   23.46
Pier Skew, UpSta & Num, DnSta & Num=  ,5089.4, 2 ,5089.4, 2 , 0 , 0 , 0 ,,
       2       2
    2.09   23.38
       2       2
    1.79   23.08
Pier Skew, UpSta & Num, DnSta & Num=  ,6009.9, 2 ,6009.9, 2 , 0 , 0 , 0 ,,
       2       2
     3.8   22.91
       2       2
     3.5   22.61
Pier Skew, UpSta & Num, DnSta & Num=  ,6051.9, 2 ,6051.9, 2 , 0 , 0 , 0 ,,
       2       2
    1.35   23.04
       2       2
    1.05   22.74
Pier Skew, UpSta & Num, DnSta & Num=  ,6093.9, 2 ,6093.9, 2 , 0 , 0 , 0 ,,
       2       2
    2.74   23.16
       2       2
    2.44   22.86
Pier Skew, UpSta & Num, DnSta & Num=  ,6135.9, 2 ,6135.9, 2 , 0 , 0 , 0 ,,
       2       2
    6.75   23.28
       2       2
    6.45   22.98
Abutment Skew #Up #Dn= , 2 , 2
    4853  4918.7
    23.9    3.65
    4853  4918.7
    23.6    3.35
Abutment Skew #Up #Dn= , 2 , 2
  5086.8 5148.19
    2.84      22
  5086.8 5148.19
    2.54    21.7
Abutment Skew #Up #Dn= , 2 , 2
  5967.7  6017.9
   21.79    4.38
  5967.7  6017.9
   21.49    4.08
Abutment Skew #Up #Dn= , 2 , 2
  6127.9 6177.99
    6.78   22.39
  6127.9 6177.99
    6.48   22.09
BR Coef= 1 , 1 , 0 ,1.25, 0 ,,,0.8,0,2,0,
WSPro=,,,, 1 ,,,, 0 ,,,, 0 ,,,,-1 ,-1 ,-1 , 0 , 0 , 0 , 0 , 0
BR Coef= 1 , 1 , 0 ,1.25, 0 ,,,0.8,0,2,0,
WSPro=,,,, 1 ,,,, 0 ,,,, 0 ,,,,-1 ,-1 ,-1 , 0 , 0 , 0 , 0 , 0
BC Mult= 3 ,3085.6,5694.67,3085.6,5694.67
BC Mult= 3 ,5421.43,8027.5,5421.43,8027.5
BR U #Sta/Elev= 172
  4085.6    27.8  4085.7    27.2    4130   26.96    4135   26.93    4170   26.74
    4175   26.71  4195.7    26.6  4210.7    26.2  4225.7    25.4  4230.7    25.3
    4250   25.65  4280.7    26.2    4290   26.25  4300.7    26.3    4330   25.88
  4335.7    25.8  4338.5   25.83  4345.7    25.9    4376      26    4435   26.23
    4475   26.39    4505   26.51  4572.3   26.77  4617.9   26.87    4618   26.87
  4668.2   27.01  4668.3   27.01    4723   26.75  4723.8   26.76  4781.4   27.44
  4781.5   27.44 4837.09   26.43  4837.2   26.42 4837.31   26.42  4837.4   26.42
    4853   21.76 4853.11   21.73  4853.2    21.7  4869.3   16.89  4912.4    4.15
  4918.6    3.66  4918.7    3.65    4923    1.83  4924.4     .73  4971.1  -12.36
  5006.9   -10.8  5030.9  -10.54  5076.5   -2.24    5077    1.01  5086.7    2.82
  5086.8    2.84  5089.3    3.23  5089.4    3.67  5121.4   12.77 5147.99   20.02
  5148.1   20.05  5148.2   20.07  5148.3    20.1 5163.69   25.06  5163.8   25.09
 5163.91   25.13  5164.2   25.22  5217.9   25.65  5218.1   25.65  5280.4   25.14
  5280.6   25.14  5338.9   24.65  5339.3   24.65  5400.6   24.72  5401.9   24.72
  5434.8   24.55  5489.1    27.8  5489.2    27.7  5490.9   26.02  5505.9    25.7
  5515.9   26.06  5520.9   26.13  5525.9   26.04  5530.9   25.78  5540.9   25.57
  5545.9   25.72  5560.9   26.64  5574.3   26.63  5789.3   21.19  5814.3   19.49
  5844.3   16.34  5849.3   15.58  5854.3   14.71  5859.3    14.5  5864.3   14.15
  5874.3   12.15  5879.3   11.28  5899.3   10.78  5909.3   10.15  5929.3    9.17
  5944.3    8.73  5949.3    8.31  5964.3     7.5 5967.81    7.16  5967.9    7.15
  5969.3    7.01  5974.3     6.1  5979.3    5.36  5989.3    6.08  6017.9    4.38
  6024.3       4  6034.3    3.23  6054.3    2.28  6064.3    2.36  6089.3    3.68
  6099.3    3.85  6109.3    4.33  6114.3    4.76  6124.3    6.18  6127.9    6.78
  6129.3    7.01  6134.3     7.7  6144.3    8.61  6149.3    9.38  6174.3   10.92
 6177.79   10.72  6177.9   10.72  6183.2   10.42  6194.3     9.8  6199.3    9.68
  6204.3      10  6209.3   10.68  6214.3   11.08  6229.3   13.39  6234.3   13.94
  6264.3    16.1  6269.3   15.82  6274.3    15.4  6279.3   15.51  6294.3   16.56
  6299.3   17.11  6314.3   19.25  6319.3   19.84  6334.3   20.55  6344.3   20.76
  6349.3   21.32  6354.3   21.66  6359.3   21.86  6363.4   21.89  6368.4   21.34
  6373.4   20.59  6388.4   17.49  6393.4   16.85  6403.4   15.93  6408.4   15.97
  6413.4   16.73  6423.4   18.53  6433.4   20.07  6438.4   20.73  6448.4   21.42
  6453.4   21.87  6458.4   22.05  6468.4   22.11  6477.8   22.39  6483.4   22.55
  6493.4   22.64  6613.3   25.25  6643.4    25.9  6688.4   26.02  6758.4   27.33
  6798.4   27.62  6812.9   27.45  6828.4   27.27  6892.4    28.2  6942.4   28.92
  6950.5   29.04  7027.5   29.09
BR U #Mann= 5
  4085.6      .2  4338.5      .1  4837.4    .035  5164.2      .1  5489.2     .99
BR U Banks=4837.4,5164.2
BR D #Sta/Elev= 172
  4085.6    27.5  4085.7    26.9    4130   26.66    4135   26.63    4170   26.44
    4175   26.41  4195.7    26.3  4210.7    25.9  4225.7    25.1  4230.7      25
    4250   25.35  4280.7    25.9    4290   25.95  4300.7      26    4330   25.58
  4335.7    25.5  4338.5   25.53  4345.7    25.6    4376    25.7    4435   25.93
    4475   26.09    4505   26.21  4572.3   26.47  4617.9   26.57    4618   26.57
  4668.2   26.71  4668.3   26.71    4723   26.45  4723.8   26.46  4781.4   27.14
  4781.5   27.14 4837.09   26.13  4837.2   26.12 4837.31   26.12  4837.4   26.12
    4853   21.46 4853.11   21.43  4853.2    21.4  4869.3   16.59  4912.4    3.85
  4918.6    3.36  4918.7    3.35    4923    1.53  4924.4     .43  4971.1  -12.66
  5006.9   -11.1  5030.9  -10.84  5076.5   -2.54    5077     .71  5086.7    2.52
  5086.8    2.54  5089.3    2.93  5089.4    3.37  5121.4   12.47 5147.99   19.72
  5148.1   19.75  5148.2   19.77  5148.3    19.8 5163.69   24.76  5163.8   24.79
 5163.91   24.83  5164.2   24.92  5217.9   25.35  5218.1   25.35  5280.4   24.84
  5280.6   24.84  5338.9   24.35  5339.3   24.35  5400.6   24.42  5401.9   24.42
  5434.8   24.25  5489.1    27.5  5489.2    27.4  5490.9   25.72  5505.9    25.4
  5515.9   25.76  5520.9   25.83  5525.9   25.74  5530.9   25.48  5540.9   25.27
  5545.9   25.42  5560.9   26.34  5574.3   26.33  5789.3   20.89  5814.3   19.19
  5844.3   16.04  5849.3   15.28  5854.3   14.41  5859.3    14.2  5864.3   13.85
  5874.3   11.85  5879.3   10.98  5899.3   10.48  5909.3    9.85  5929.3    8.87
  5944.3    8.43  5949.3    8.01  5964.3     7.2 5967.81    6.86  5967.9    6.85
  5969.3    6.71  5974.3     5.8  5979.3    5.06  5989.3    5.78  6017.9    4.08
  6024.3     3.7  6034.3    2.93  6054.3    1.98  6064.3    2.06  6089.3    3.38
  6099.3    3.55  6109.3    4.03  6114.3    4.46  6124.3    5.88  6127.9    6.48
  6129.3    6.71  6134.3     7.4  6144.3    8.31  6149.3    9.08  6174.3   10.62
 6177.79   10.42  6177.9   10.42  6183.2   10.12  6194.3     9.5  6199.3    9.38
  6204.3     9.7  6209.3   10.38  6214.3   10.78  6229.3   13.09  6234.3   13.64
  6264.3    15.8  6269.3   15.52  6274.3    15.1  6279.3   15.21  6294.3   16.26
  6299.3   16.81  6314.3   18.95  6319.3   19.54  6334.3   20.25  6344.3   20.46
  6349.3   21.02  6354.3   21.36  6359.3   21.56  6363.4   21.59  6368.4   21.04
  6373.4   20.29  6388.4   17.19  6393.4   16.55  6403.4   15.63  6408.4   15.67
  6413.4   16.43  6423.4   18.23  6433.4   19.77  6438.4   20.43  6448.4   21.12
  6453.4   21.57  6458.4   21.75  6468.4   21.81  6477.8   22.09  6483.4   22.25
  6493.4   22.34  6613.3   24.95  6643.4    25.6  6688.4   25.72  6758.4   27.03
  6798.4   27.32  6812.9   27.15  6828.4   26.97  6892.4    27.9  6942.4   28.62
  6950.5   28.74  7027.5   28.79
BR D #Mann= 5
  4085.6      .2  4338.5      .1  4837.4    .035  5164.2      .1  5489.2     .99
BR D Banks=4837.4,5164.2
BC Design=,, 0 ,, 0 ,,,,,,
BC HTab HWMax=29.09
BC Use User HTab Curves=0
BC User HTab FreeFlow(D)= 0

Type RM Length L Ch R = 1 ,14382.6 ,628.1,628.1,628.1
BEGIN DESCRIPTION:
Downstream Section of Bridge/Culvert/Weir
END DESCRIPTION:
XS GIS Cut Line= 5
      3154444.42     13819011.04      3154622.52     13818801.24
      3155363.39     13817935.78      3155930.06      13817290.8
      3156126.76     13816651.49
#Sta/Elev= 30
  4085.6   27.48  4230.7   24.98  4338.5   25.51  4837.4    26.1  4971.1  -12.68
  5030.9  -10.86  5076.5   -2.56    5077     .69  5089.3    2.91  5164.2    24.9
  5434.8   24.23  5489.2   27.38  5490.9    25.7  5574.3   26.31  5789.3   20.87
  5864.3   13.83  5879.3   10.96  6054.3    1.96  6109.3    4.01  6174.3    10.6
  6204.3    9.68  6234.3   13.62  6264.3   15.78  6279.3   15.19  6319.3   19.52
  6359.3   21.54  6408.4   15.65  6458.4   21.73  6758.4   27.01  7027.5   28.77
#Mann= 5 , 1 , 0
  4085.6      .2       0  4338.5      .1       0  4837.4    .035       0
  5164.2      .1       0  5489.2     .99       0
#XS Ineff= 3 ,-1
    4100    4842   26.58    5157    5957   24.52    6187    6640   25.85
Permanent Ineff=
       F       F       F
Bank Sta=4837.4,5164.2
XS Rating Curve= 0 ,0
Exp/Cntr=0.5,0.3

Type RM Length L Ch R = 1 ,13754.5 ,740.2,745.5,905.9
BEGIN DESCRIPTION:
Cross Section 13754.5
END DESCRIPTION:
XS GIS Cut Line= 6
      3154920.69     13818782.98      3155556.98     13818814.96
      3155666.44      13818678.1       3155631.5     13818196.98
      3156058.48     13817383.69      3156131.23      13816647.4
#Sta/Elev= 30
  4529.1    27.5  4551.5   26.48  4583.1    25.2  4841.8   22.56  4920.7   -2.49
  4964.7  -12.44  5009.4  -15.31  5057.1  -12.81  5089.7    1.61  5161.3   25.06
  5346.2   25.22    5539   24.49  5902.5   22.68  6322.5   15.69  6412.5   15.52
  6442.5   13.74  6462.5   13.97  6497.5    6.82  6512.5    4.55  6527.5    4.06
  6612.5    5.83  6657.5    9.01  6747.5   21.15  6836.1   24.58  6931.1   24.86
  7051.1   22.51  7146.1   22.36  7201.1   26.79  7366.1   26.31  7500.9    28.9
#Mann= 6 , 1 , 0
  4529.1      .2       0  4551.5      .1       0  4841.8    .035       0
  5161.3      .1       0  5346.2      .2       0    5539     .99       0
Bank Sta=4841.8,5161.3
XS Rating Curve= 0 ,0
Exp/Cntr=0.3,0.1

Type RM Length L Ch R = 1 ,13009.0 ,257.4,332.4,234.3
BEGIN DESCRIPTION:
Cross Section 13009.0 - Interpolated
END DESCRIPTION:
XS GIS Cut Line= 6
      3154360.36     13819190.79      3154803.49     13819416.62
      3155331.83     13819582.79      3155472.44     13819693.57
       3155651.4     13819770.27      3156324.61     13819817.14
#Sta/Elev= 30
  4013.8   27.21  4433.8   26.86  4493.8    24.8  4503.8   24.02  4541.2   18.44
  4571.2   15.59  4661.2   10.88  4681.2    8.89  4731.2    6.99  4761.2    3.18
  4771.2    2.34  4804.9    2.43  4907.7   -1.43  4910.1   -3.89  4914.5   -3.79
  4915.1   -4.38  4976.6   -12.1  5017.4  -12.19  5038.8   -12.7  5085.4   -5.91
    5090    -3.6  5098.3    -1.8  5125.4    6.75  5145.4   13.29  5175.4   13.81
  5221.6   17.44  5244.4   18.43  5439.1    19.4  6029.1   27.64  6113.9   27.29
#Mann= 6 , 1 , 0
  4013.8      .2       0  4013.8      .1       0  4731.2    .035       0
  5125.4     .14       0  5221.6      .1       0  6113.9      .2       0
Bank Sta=4731.2,5125.4
XS Rating Curve= 0 ,0
Exp/Cntr=0.5,0.3

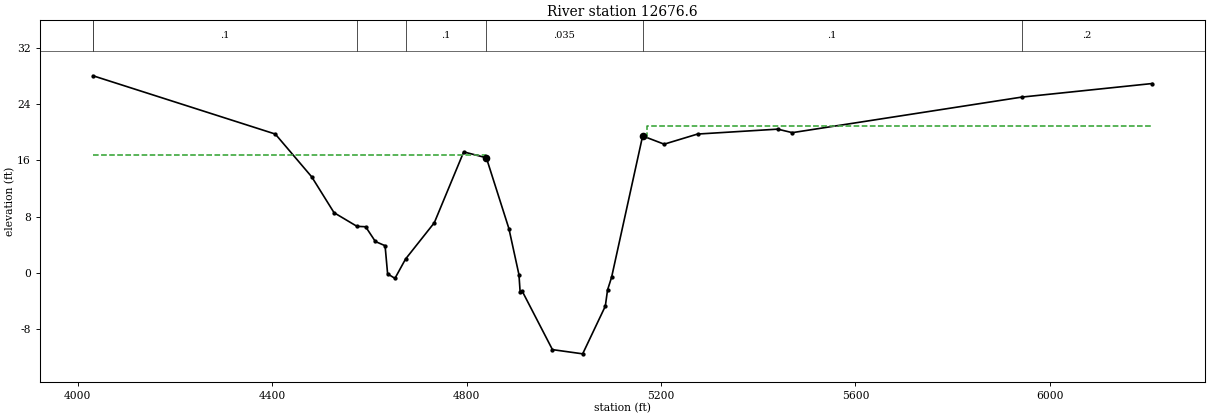
Type RM Length L Ch R = 1 ,12676.6 ,54.4,54.4,54.4
BEGIN DESCRIPTION:
Upstream Section of Bridge/Culvert/Weir
END DESCRIPTION:
XS GIS Cut Line= 6
      3154349.69     13819343.07      3154916.89     13819749.43
      3155076.15      13819836.3      3155376.57     13819883.35
      3155789.19     13819868.87      3156357.72     13819995.21
#Sta/Elev= 30
  4031.3   28.06  4406.3   19.76  4481.3   13.66  4527.2    8.56  4574.3    6.62
  4592.2    6.56  4612.2    4.46  4632.2    3.86  4637.4    -.15  4652.5    -.79
  4674.3    1.96  4733.5    7.13    4794   17.22  4840.6   16.38    4887     6.3
  4907.7    -.27  4910.1   -2.73  4914.5   -2.63  4976.6  -10.94  5038.8  -11.54
  5085.4   -4.75    5090   -2.44  5098.3    -.64  5162.2   19.49  5206.5   18.32
  5275.2   19.76  5440.2   20.46  5470.2   19.96    5942   25.02  6211.3   26.96
#Mann= 7 , 1 , 0
  4031.3      .2       0  4031.3      .1       0  4574.3    .065       0
  4674.3      .1       0  4840.6    .035       0  5162.2      .1       0
    5942      .2       0
#XS Ineff= 2 , 0
       0    4840   16.73    5171       0   20.92
Permanent Ineff=
       F       F
Bank Sta=4840.6,5162.2
XS Rating Curve= 0 ,0
Exp/Cntr=0.5,0.3