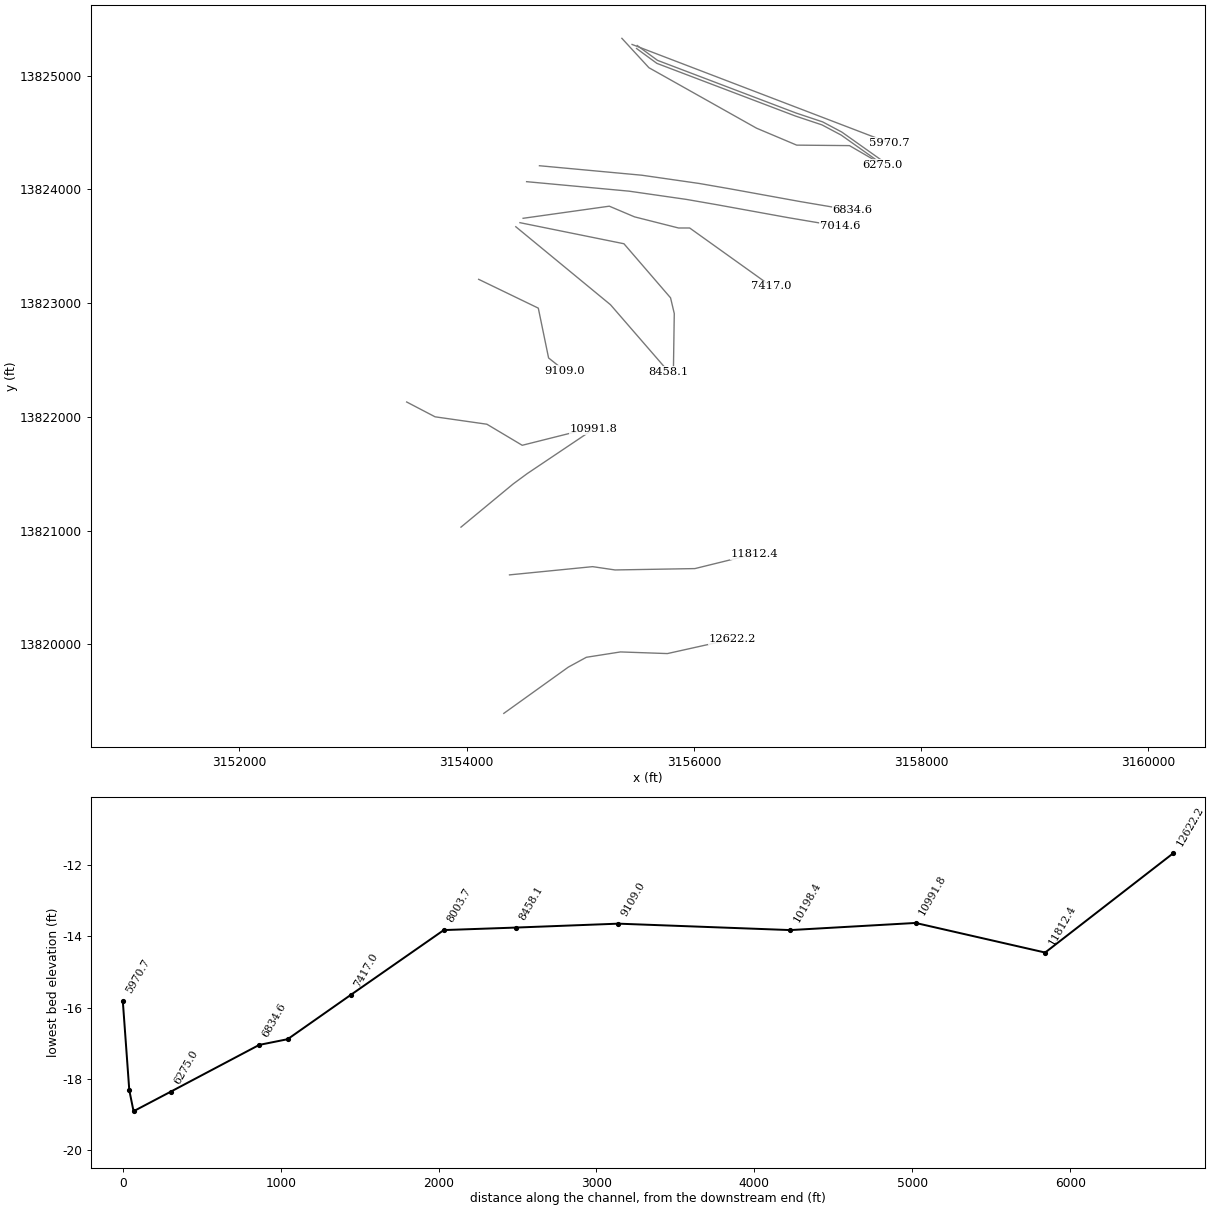
HEC-RAS study C100-00-00.prj: C100-00-00

--- C100-00-00.g01 (geometry) --- (continued)

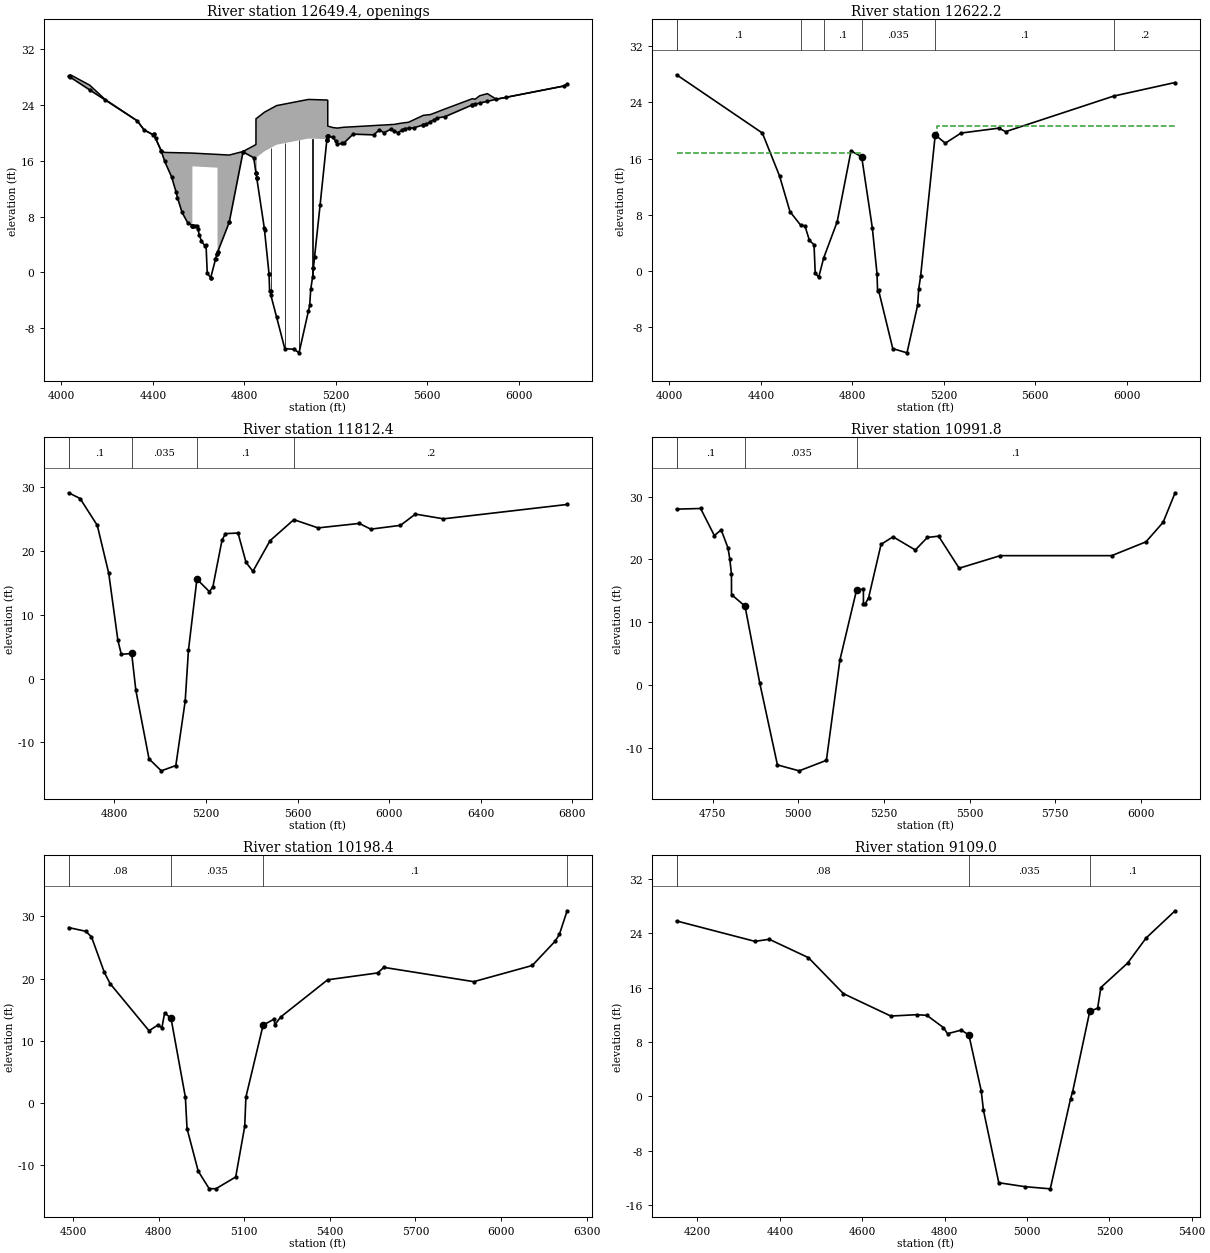
Type RM Length L Ch R = 4 ,12649.4 ,,,
BEGIN DESCRIPTION:
GOODYEAR ACCESS ROAD
Structure ID: C00-7
END DESCRIPTION:
Bridge Culvert--1,0,-1,-1, 0
Deck Dist Width WeirC Skew NumUp NumDn MinLoCord MaxHiCord MaxSubmerge Is_Ogee
10,34.4,2.6,0, 60, 60, , , 0.95, 0, 1,1,,
  4031.3    4039    4124  4189.7  4331.3  4361.3  4401.3  4406.3  4411.3  4436.3
  4451.3  4481.3  4501.3  4507.2  4527.2  4552.2 4572.31  4572.4 4682.29  4682.4
  4733.5    4794  4840.6 4850.39  4850.5 4854.11  4854.2  4887.9  4940.7  5079.4
 5160.19  5160.4  5162.2  5164.4 5164.51  5188.1  5206.5  5234.9  5275.2  5365.2
  5390.2  5410.2  5440.2  5455.9  5470.2  5500.2  5517.7  5540.2  5582.7  5595.2
  5612.7  5640.2  5677.2  5797.2  5808.9  5828.9  5862.5  5901.9  6198.5  6211.3
    28.1    28.3    26.8    24.8   21.71   20.41   19.71   19.81   19.21   17.41
   17.19   17.16   17.15   17.14   17.13   17.11   17.09   17.09    16.9    16.9
   16.81   17.32   18.14   18.32   22.02   22.09   22.09   22.95   23.89   24.77
   24.69   24.69   24.67   24.65   20.95   20.74   20.67   20.79   20.86   21.03
   21.08   21.11   21.17    21.2   21.29   21.44    21.5   21.85    22.5   22.54
    22.6   22.94   23.41   24.88    24.8    25.3    25.6    24.8    26.7      27
    28.1   27.94   26.12   24.72    21.7    20.4    19.7    19.8    19.2    17.4
    15.9    13.7    11.5    10.7     8.6     7.1     6.7   15.19      15    2.89
    7.17   17.26   16.42   14.29   14.27   13.49   16.49   17.35   18.29   19.17
   19.09   18.96   19.53   19.51   19.51   19.35   18.36   18.52    19.8    19.7
    20.4      20    20.5   20.24      20    20.6   20.64    20.7   21.12    21.2
   21.55    22.1    22.3      24   24.09   24.24    24.5    24.8    26.7      27
  4031.3    4039    4124  4189.7  4331.3  4361.3  4401.3  4406.3  4411.3  4436.3
  4451.3  4481.3  4501.3  4507.2  4527.2  4552.2 4572.31  4572.4 4682.29  4682.4
  4733.5    4794  4840.6 4850.39  4850.5 4854.11  4854.2  4887.9  4940.7  5079.4
 5160.19  5160.4  5162.2  5164.4 5164.51  5188.1  5206.5  5234.9  5275.2  5365.2
  5390.2  5410.2  5440.2  5455.9  5470.2  5500.2  5517.7  5540.2  5582.7  5595.2
  5612.7  5640.2  5677.2  5797.2  5808.9  5828.9  5862.5  5901.9  6198.5  6211.3
    28.1    28.3    26.8    24.8   21.71   20.41   19.71   19.81   19.21   17.41
   17.19   17.16   17.15   17.14   17.13   17.11   17.09   17.09    16.9    16.9
   16.81   17.32   18.14   18.32   22.02   22.09   22.09   22.95   23.89   24.77
   24.69   24.69   24.67   24.65   20.95   20.74   20.67   20.79   20.86   21.03
   21.08   21.11   21.17    21.2   21.29   21.44    21.5   21.85    22.5   22.54
    22.6   22.94   23.41   24.88    24.8    25.3    25.6    24.8    26.7      27
   27.96    27.8   25.98   24.58   21.56   20.26   19.56   19.66   19.06   17.26
   15.76   13.56   11.36   10.56    8.46    6.96    6.56   15.05   14.86    2.75
    7.03   17.12   16.28   14.15   14.13   13.35   16.35   17.21   18.15   19.03
   18.95   18.82   19.39   19.37   19.37   19.21   18.22   18.38   19.66   19.56
   20.26   19.86   20.36    20.1   19.86   20.46    20.5   20.56   20.98   21.06
   21.41   21.96   22.16   23.86   23.95    24.1   24.36   24.66   26.56   26.86
Pier Skew, UpSta & Num, DnSta & Num=  ,4915.1, 2 ,4915.1, 2 , 0 , 0 , 0 ,,
       2       2
   -4.31   18.85
       2       2
   -4.45   18.71
Pier Skew, UpSta & Num, DnSta & Num=  ,4976.6, 2 ,4976.6, 2 , 0 , 0 , 0 ,,
       2       2
   -11.9   19.53
       2       2
  -12.04   19.39
Pier Skew, UpSta & Num, DnSta & Num=  ,5038.8, 2 ,5038.8, 2 , 0 , 0 , 0 ,,
       2       2
  -12.48   19.92
       2       2
  -12.62   19.78
Pier Skew, UpSta & Num, DnSta & Num=  ,5098.3, 2 ,5098.3, 2 , 0 , 0 , 0 ,,
       2       2
   -1.82   20.18
       2       2
   -1.96   20.04
Abutment Skew #Up #Dn= , 2 , 2
  4572.2  4582.4
   15.19     6.6
  4572.2  4582.4
   15.05    6.46
Abutment Skew #Up #Dn= , 2 , 2
  4673.4 4682.49
    1.88      15
  4673.4 4682.49
    1.74   14.86
Abutment Skew #Up #Dn= , 2 , 2
    4854  4907.7
   16.49    -.23
    4854  4907.7
   16.35    -.37
Abutment Skew #Up #Dn= , 2 , 2
  5101.5 5160.39
     .61   19.09
  5101.5 5160.39
     .47   18.95
BR Coef= 1 , 1 , 0 ,1.25, 0 ,,,0.8,0,2,0,
WSPro=,,,, 1 ,,,, 0 ,,,, 0 ,,,,-1 ,-1 ,-1 , 0 , 0 , 0 , 0 , 0
BR Coef= 1 , 1 , 0 ,1.25, 0 ,,,0.8,0,2,0,
WSPro=,,,, 1 ,,,, 0 ,,,, 0 ,,,,-1 ,-1 ,-1 , 0 , 0 , 0 , 0 , 0
BC Mult= 3 ,3031.3,4796.93,3031.3,4796.93
BC Mult= 3 ,4739.67,7211.3,4739.67,7211.3
BR U #Sta/Elev= 107
  4031.3    28.1    4039   27.94    4124   26.12  4189.7   24.72  4331.3    21.7
  4361.3    20.4  4401.3    19.7  4404.7   19.77  4406.3    19.8  4411.3    19.2
  4435.4   17.46  4436.3    17.4  4451.3    15.9  4481.3    13.7  4501.3    11.5
  4507.2    10.7  4527.2     8.6  4552.2     7.1 4572.31     6.7  4572.4     6.7
  4574.3    6.66  4577.2     6.6  4582.4     6.6  4592.2     6.6  4597.2     6.2
  4602.2     5.4  4612.2     4.5  4627.2     3.8  4632.2     3.9  4637.4    -.11
  4652.1    -.73  4652.5    -.75  4673.4    1.88  4674.3       2  4679.4    2.64
  4680.1     2.7 4682.29    2.88  4682.4    2.89  4733.5    7.17  4733.7     7.2
    4794   17.26  4794.5   17.25  4840.6   16.42 4850.39   14.29  4850.5   14.27
 4850.61   14.25  4853.9   13.53 4854.11   13.49  4854.2   13.47    4887    6.34
  4887.9    6.05  4907.6     -.2  4907.7    -.23  4910.1   -2.69  4914.5   -2.59
  4915.1   -3.18  4940.7   -6.39  4976.6   -10.9  5017.4  -10.99  5038.8   -11.5
  5079.4   -5.58  5085.4   -4.71    5090    -2.4  5098.3     -.6  5101.4     .58
  5101.5     .61  5106.7    2.21  5131.1    9.71 5160.19    18.9  5160.3   18.93
  5160.4   18.96  5162.2   19.53 5164.29   19.52  5164.4   19.51 5164.51   19.51
  5188.1   19.35  5199.3   18.75  5206.5   18.36  5226.7   18.47  5234.9   18.52
  5275.2    19.8  5365.2    19.7  5390.2    20.4  5410.2      20  5440.2    20.5
  5455.9   20.24  5470.2      20  5487.7   20.35  5500.2    20.6  5517.7   20.64
  5540.2    20.7  5580.2    21.1  5582.7   21.12  5595.2    21.2  5612.7   21.55
  5628.9   21.87  5640.2    22.1  5677.2    22.3  5793.9   23.95  5797.2      24
  5808.9   24.09  5828.9   24.24  5862.5    24.5  5901.9    24.8    5942   25.06
  6198.5    26.7  6211.3      27
BR U #Mann= 7
  4031.3      .2  4031.3      .1  4574.3    .065  4674.3      .1  4840.6    .035
  5162.2      .1    5942      .2
BR U Banks=4840.6,5162.2
BR D #Sta/Elev= 107
  4031.3   27.96    4039    27.8    4124   25.98  4189.7   24.58  4331.3   21.56
  4361.3   20.26  4401.3   19.56  4404.7   19.63  4406.3   19.66  4411.3   19.06
  4435.4   17.32  4436.3   17.26  4451.3   15.76  4481.3   13.56  4501.3   11.36
  4507.2   10.56  4527.2    8.46  4552.2    6.96 4572.31    6.56  4572.4    6.56
  4574.3    6.52  4577.2    6.46  4582.4    6.46  4592.2    6.46  4597.2    6.06
  4602.2    5.26  4612.2    4.36  4627.2    3.66  4632.2    3.76  4637.4    -.25
  4652.1    -.87  4652.5    -.89  4673.4    1.74  4674.3    1.86  4679.4     2.5
  4680.1    2.56 4682.29    2.74  4682.4    2.75  4733.5    7.03  4733.7    7.06
    4794   17.12  4794.5   17.11  4840.6   16.28 4850.39   14.15  4850.5   14.13
 4850.61   14.11  4853.9   13.39 4854.11   13.35  4854.2   13.33    4887     6.2
  4887.9    5.91  4907.6    -.34  4907.7    -.37  4910.1   -2.83  4914.5   -2.73
  4915.1   -3.32  4940.7   -6.53  4976.6  -11.04  5017.4  -11.13  5038.8  -11.64
  5079.4   -5.72  5085.4   -4.85    5090   -2.54  5098.3    -.74  5101.4     .44
  5101.5     .47  5106.7    2.07  5131.1    9.57 5160.19   18.76  5160.3   18.79
  5160.4   18.82  5162.2   19.39 5164.29   19.38  5164.4   19.37 5164.51   19.37
  5188.1   19.21  5199.3   18.61  5206.5   18.22  5226.7   18.33  5234.9   18.38
  5275.2   19.66  5365.2   19.56  5390.2   20.26  5410.2   19.86  5440.2   20.36
  5455.9    20.1  5470.2   19.86  5487.7   20.21  5500.2   20.46  5517.7    20.5
  5540.2   20.56  5580.2   20.96  5582.7   20.98  5595.2   21.06  5612.7   21.41
  5628.9   21.73  5640.2   21.96  5677.2   22.16  5793.9   23.81  5797.2   23.86
  5808.9   23.95  5828.9    24.1  5862.5   24.36  5901.9   24.66    5942   24.92
  6198.5   26.56  6211.3   26.86
BR D #Mann= 7
  4031.3      .2  4031.3      .1  4574.3    .065  4674.3      .1  4840.6    .035
  5162.2      .1    5942      .2
BR D Banks=4840.6,5162.2
BC Design=,, 0 ,, 0 ,,,,,,
BC HTab HWMax=28.06
BC Use User HTab Curves=0
BC User HTab FreeFlow(D)= 0

Type RM Length L Ch R = 1 ,12622.2 ,809.8,809.8,809.8
BEGIN DESCRIPTION:
Downstream Section of Bridge/Culvert/Weir
END DESCRIPTION:
XS GIS Cut Line= 6
      3154326.86     13819392.44      3154894.05     13819798.81
      3155053.31     13819885.68      3155353.73     13819932.73
      3155766.35     13819918.25      3156334.89     13820044.58
#Sta/Elev= 30
  4031.3   27.93  4406.3   19.63  4481.3   13.53  4527.2    8.43  4574.3    6.49
  4592.2    6.43  4612.2    4.33  4632.2    3.73  4637.4    -.28  4652.5    -.92
  4674.3    1.83  4733.5       7    4794   17.09  4840.6   16.25    4887    6.17
  4907.7     -.4  4910.1   -2.86  4914.5   -2.76  4976.6  -11.07  5038.8  -11.67
  5085.4   -4.88    5090   -2.57  5098.3    -.77  5162.2   19.36  5206.5   18.19
  5275.2   19.63  5440.2   20.33  5470.2   19.83    5942   24.89  6211.3   26.83
#Mann= 7 , 1 , 0
  4031.3      .2       0  4031.3      .1       0  4574.3    .065       0
  4674.3      .1       0  4840.6    .035       0  5162.2      .1       0
    5942      .2       0
#XS Ineff= 2 , 0
       0    4840   16.73    5171       0   20.62
Permanent Ineff=
       F       F
Bank Sta=4840.6,5162.2
XS Rating Curve= 0 ,0
Exp/Cntr=0.5,0.3

Type RM Length L Ch R = 1 ,11812.4 ,739.5,820.6,923.1
BEGIN DESCRIPTION:
Cross Section 11812.4
END DESCRIPTION:
XS GIS Cut Line= 5
      3154377.03     13820610.22      3155108.16     13820682.61
      3155305.65     13820653.56      3156008.32     13820665.56
      3156532.74     13820794.45
#Sta/Elev= 30
    4600    29.1    4650    28.2    4725      24    4775    16.5    4815       6
    4830     3.8  4875.2    3.93  4893.4   -1.81    4951  -12.58  5004.7  -14.45
  5068.1  -13.62  5108.9   -3.55  5123.2    4.44  5160.2   15.57    5215    13.6
    5230    14.4    5270    21.7    5285    22.7  5339.7    22.8  5374.7    18.2
  5404.7    16.8  5479.7    21.6  5583.5   24.89  5689.3    23.6  5869.3    24.3
  5919.3    23.4  6049.3      24  6114.3   25.76  6237.1   25.02  6777.1   27.27
#Mann= 5 , 1 , 0
    4600      .2       0    4600      .1       0  4875.2    .035       0
  5160.2      .1       0  5583.5      .2       0
Bank Sta=4875.2,5160.2
XS Rating Curve= 0 ,0
Exp/Cntr=0.3,0.1

Type RM Length L Ch R = 1 ,10991.8 ,961.3,793.4,649.3
BEGIN DESCRIPTION:
Cross Section 10991.8
END DESCRIPTION:
XS GIS Cut Line= 4
      3153949.93     13821030.08       3154409.6     13821410.12
      3154532.67     13821500.61      3155118.25     13821893.25
#Sta/Elev= 30
  4645.1      28  4715.1    28.1  4755.1    23.8  4775.1    24.7  4795.1    21.8
  4800.1    20.1  4805.1    17.7  4805.2   14.41  4844.6   12.57  4887.3     .42
  4939.2  -12.68  5002.6  -13.62    5082  -11.95  5121.5    4.02    5170   15.13
    5190   15.27  5190.1    12.9  5195.1    12.9  5205.1    13.9  5241.5    22.4
  5276.5    23.6  5341.5    21.5  5376.5    23.5  5409.3    23.7  5469.3    18.6
  5589.3    20.6  5914.3    20.6  6014.3    22.8  6064.3    25.9  6099.3    30.6
#Mann= 4 , 1 , 0
  4645.1      .2       0  4645.1      .1       0  4844.6    .035       0
    5170      .1       0
Bank Sta=4844.6,5170
XS Rating Curve= 0 ,0
Exp/Cntr=0.3,0.1

Type RM Length L Ch R = 1 ,10198.4 ,1332.6,1089.4,889.8
BEGIN DESCRIPTION:
Cross Section 10198.4
END DESCRIPTION:
XS GIS Cut Line= 5
      3153472.16      13822130.4       3153721.9      13822000.1
      3154177.96     13821934.95      3154488.86     13821749.73
      3155111.78     13821905.99
#Sta/Elev= 30
    4485    28.2    4545    27.6    4565    26.7    4610      21    4630    19.2
  4766.7    11.6  4796.7    12.5  4811.7    12.1  4821.3   14.48  4843.7    13.6
    4894     .91  4899.7   -4.12    4939  -10.98    4977  -13.77  5000.3  -13.82
  5070.3  -11.91  5101.9   -3.77    5106     .93  5166.3   12.51    5206   13.51
  5206.7    12.5  5227.4    13.8  5392.4    19.8  5567.4    20.9  5589.3    21.8
  5904.3    19.5  6109.3    22.1  6189.3      26  6204.3    27.1  6231.5    30.9
#Mann= 5 , 1 , 0
    4485      .2       0    4485     .08       0  4843.7    .035       0
  5166.3      .1       0  6231.5      .2       0
Bank Sta=4843.7,5166.3
XS Rating Curve= 0 ,0
Exp/Cntr=0.3,0.1

Type RM Length L Ch R = 1 ,9109.0  ,507.1,650.9,750.5
BEGIN DESCRIPTION:
Cross Section 9109.0
END DESCRIPTION:
XS GIS Cut Line= 4
      3154105.57       13823209.      3154630.39     13822955.64
      3154720.88     13822517.68      3154862.04     13822405.48
#Sta/Elev= 25
  4149.4    25.8  4339.4    22.8  4374.4    23.1  4469.4    20.4  4554.4    15.1
  4669.4    11.8  4732.2      12  4757.2    11.9  4797.2    10.1  4807.2     9.2
  4840.5    9.73    4859    9.01    4889     .78  4894.3   -2.05  4931.6  -12.74
    4995  -13.32  5056.6  -13.64  5105.8     -.4    5111     .68  5152.5   12.49
  5171.6   12.96  5179.4      16  5244.4    19.6  5289.4    23.3  5359.7    27.3
#Mann= 4 , 1 , 0
  4149.4      .2       0  4149.4     .08       0    4859    .035       0
  5152.5      .1       0
Bank Sta=4859,5152.5
XS Rating Curve= 0 ,0
Exp/Cntr=0.3,0.1

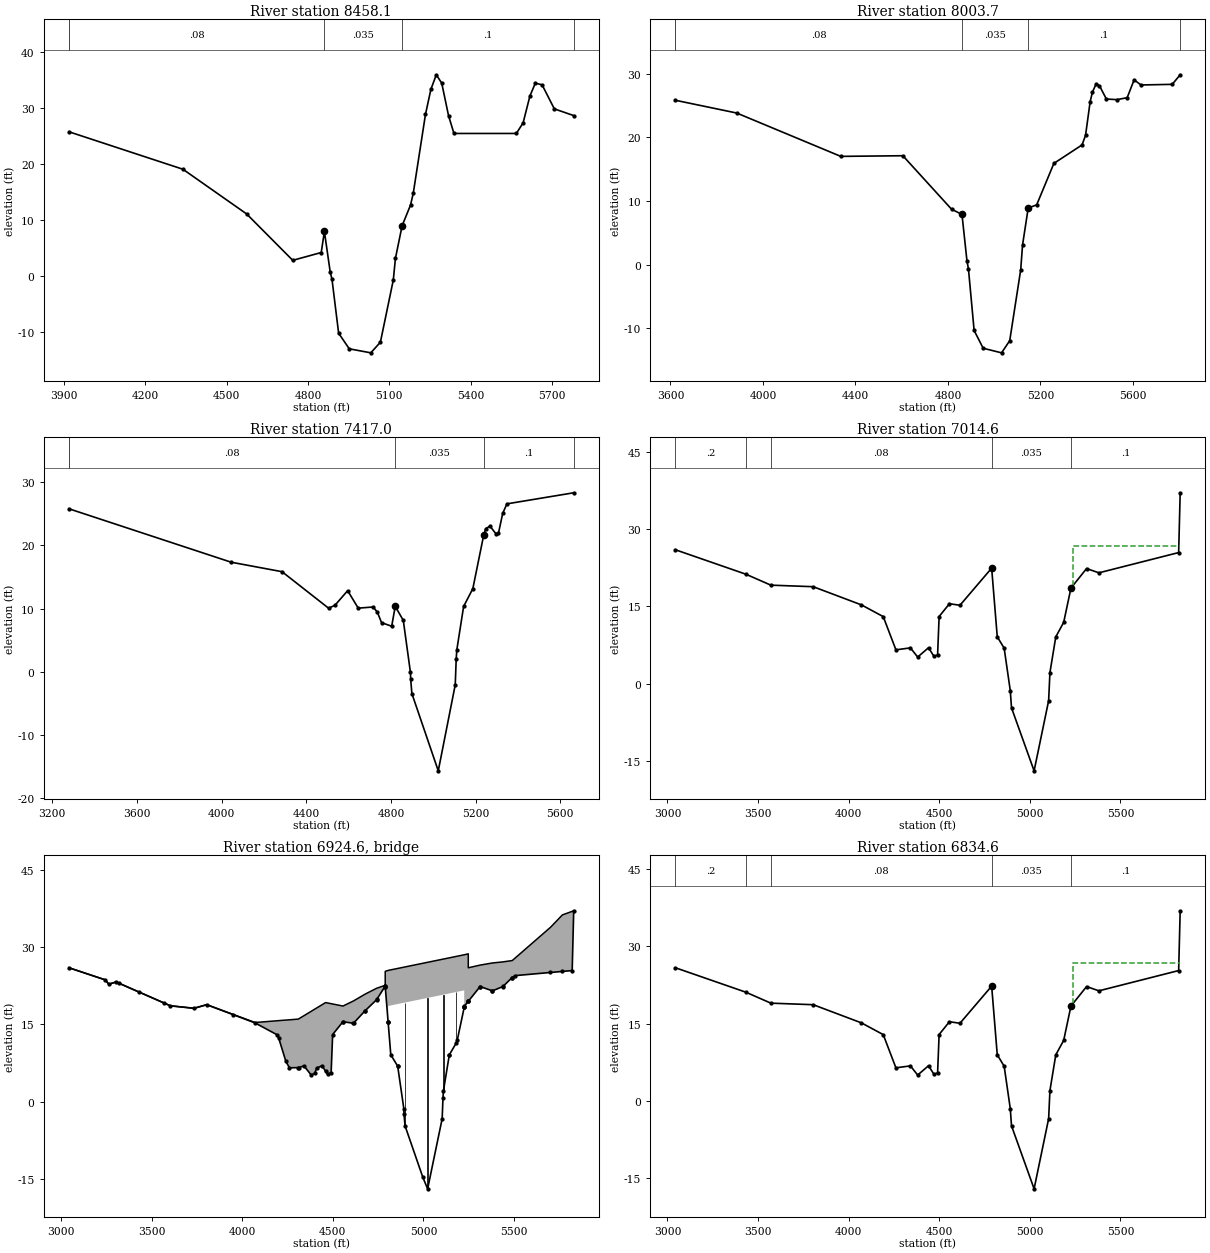
Type RM Length L Ch R = 1 ,8458.1  ,493.1,454.4,449.2
BEGIN DESCRIPTION:
Cross Section 8458.1-Interpolated
END DESCRIPTION:
XS GIS Cut Line= 3
       3154432.3     13823671.43      3155265.63     13822985.66
      3155777.78     13822395.38
#Sta/Elev= 30
  3919.2    25.8  4339.2    19.1  4574.2    11.1  4744.2     2.8  4849.2     4.2
  4860.8    7.96  4882.4     .66  4888.8    -.58  4913.3  -10.24  4952.5  -13.03
    5032  -13.75  5067.3  -11.84  5114.8    -.72  5122.7    3.15  5147.2    8.97
  5178.4    12.7  5188.4    14.8  5233.4    28.9  5253.4    33.4  5273.4      36
  5293.4    34.5  5318.4    28.7  5338.4    25.5  5568.4    25.5  5593.4    27.4
  5618.4    32.2  5638.4    34.5  5663.4    34.2  5708.4    29.9  5779.9    28.7
#Mann= 5 , 1 , 0
  3919.2      .2       0  3919.2     .08       0  4860.8    .035       0
  5147.2      .1       0  5779.9      .2       0
Bank Sta=4860.8,5147.2
XS Rating Curve= 0 ,0
Exp/Cntr=0.3,0.1

Type RM Length L Ch R = 1 ,8003.7  ,531.6,586.7,640.9
BEGIN DESCRIPTION:
Cross Section 8003.7
END DESCRIPTION:
XS GIS Cut Line= 5
      3154468.82     13823707.11       3155383.9     13823521.92
      3155794.23     13823046.22      3155826.91     13822908.24
      3155819.65     13822428.91
#Sta/Elev= 30
  3621.5    25.8  3886.5    23.8  4336.5      17  4605.1    17.1  4815.5    8.72
  4860.8    7.89  4882.4     .59  4888.8    -.65  4913.3  -10.31  4952.5   -13.1
    5032  -13.82  5067.3  -11.91  5114.8    -.79  5122.7    3.08  5147.2     8.9
  5183.8    9.39  5258.3    15.9  5380.2    18.8  5395.2    20.3  5415.2    25.6
  5425.2    27.1  5440.2    28.3  5455.2    28.1  5485.2      26  5530.2    25.9
  5575.2    26.2  5605.2      29  5635.2    28.2  5770.2    28.3  5804.5    29.8
#Mann= 5 , 1 , 0
  3621.5      .2       0  3621.5     .08       0  4860.8    .035       0
  5147.2      .1       0  5804.5      .2       0
Bank Sta=4860.8,5147.2
XS Rating Curve= 0 ,0
Exp/Cntr=0.3,0.1

Type RM Length L Ch R = 1 ,7417.0  ,216.9,402.4,396.7
BEGIN DESCRIPTION:
Cross Section 7417.0 - Interpolated
END DESCRIPTION:
XS GIS Cut Line= 6
      3154496.71     13823745.63      3155255.14     13823852.15
       3155476.7     13823758.41      3155864.44     13823660.41
      3155962.44     13823660.41      3156678.26     13823149.11
#Sta/Elev= 30
  3278.9   25.78  4044.8   17.34  4285.3   15.84  4505.3   10.07  4535.3   10.53
  4595.3   12.84  4645.3   10.08  4715.3   10.26  4735.3    9.47  4755.3    7.79
  4803.3    7.22    4820   10.36  4858.1    8.15  4891.9    -.08  4893.1   -1.17
  4898.6   -3.41  5023.3  -15.63  5103.5   -2.03    5108    1.99  5110.7    3.43
  5143.1   10.35  5186.6   13.16  5237.6   21.57  5247.6   22.64  5267.6   23.04
  5297.6   21.75  5307.6    21.9  5327.6   25.05  5347.6   26.56  5663.1   28.31
#Mann= 5 , 1 , 0
  3278.9      .2       0  3278.9     .08       0    4820    .035       0
  5237.6      .1       0  5663.1      .2       0
Bank Sta=4820,5237.6
XS Rating Curve= 0 ,0
Exp/Cntr=0.5,0.3

Type RM Length L Ch R = 1 ,7014.6  ,180,180,180
BEGIN DESCRIPTION:
Upstream Section of Bridge/Culvert/Weir
END DESCRIPTION:
XS GIS Cut Line= 6
      3154527.43     13824067.69      3155429.07      13823984.2
      3155934.55     13823911.58      3156201.81      13823865.1
      3156826.38      13823751.8        3157283.     13823674.59
#Sta/Elev= 30
  3044.1   25.98  3432.3   21.25  3570.7   19.12  3804.4   18.82  4070.8   15.29
  4190.8   13.02  4260.8    6.58  4340.8    6.96  4380.8    5.18  4440.8    6.99
  4470.8    5.31  4490.8    5.61  4499.2   13.04  4556.1   15.52  4614.2   15.22
  4789.1   22.42    4820    9.11  4858.1     6.9  4891.9   -1.33  4898.6   -4.66
  5023.3  -16.88  5103.5   -3.28  5110.7    2.18    5143     9.1  5186.6   11.91
  5226.6   18.55  5312.9   22.34  5380.8   21.51    5821   25.44  5829.4   37.03
#Mann= 5 , 1 , 0
  3044.1      .2       0  3432.3      .1       0  3570.7     .08       0
  4789.1    .035       0  5226.6      .1       0
#XS Ineff= 2 , 0
       0    4795   15.54    5236       0   26.77
Permanent Ineff=
       F       F
Bank Sta=4789.1,5226.6
XS Rating Curve= 0 ,0
Exp/Cntr=0.5,0.3

Type RM Length L Ch R = 3 ,6924.6  ,,,
BEGIN DESCRIPTION:
LA PORTE FREEWAY 225
Structure ID: C00-6A
END DESCRIPTION:
Bridge Culvert--1,0,-1,-1, 0
Deck Dist Width WeirC Skew NumUp NumDn MinLoCord MaxHiCord MaxSubmerge Is_Ogee
10,160,2.6,0, 45, 45, , , 0.95, 0, 1,1,,
  3044.1  3244.1  3264.1  3304.1  3604.1  3734.4  3804.4  4070.8  4190.8  4200.8
  4240.8  4260.8  4309.6  4340.8  4380.8  4400.8  4410.8  4440.8  4460.2  4470.8
  4490.8  4499.2  4556.1  4614.2  4677.8  4742.1  4789.1 4789.19  4789.3 4805.31
  4805.4 5225.19  5225.3  5226.6  5247.6 5247.71  5312.9  5380.8  5438.2  5490.1
  5506.6  5701.3    5767    5821  5829.4
   25.95   23.61   22.76    23.2   18.58    18.1    18.8   15.34   15.67    15.7
   15.81   15.86      16   16.66   17.51   17.94   18.15   18.79    19.2   19.13
   18.99   18.93   18.53   19.52   20.83   21.98   22.55   22.55   25.25   25.44
   25.44   28.47   28.47   28.48   28.65   25.95   26.47   26.88   27.09   27.35
   27.85    33.8    36.2   36.89      37
   25.95   23.61   22.76    23.2   18.57   18.09   18.79   15.26   12.99    12.4
    7.82    6.55    6.59    6.93    5.15     5.5     6.5    6.96    5.87    5.28
    5.58   13.01   15.49   15.19    17.6   19.77   22.39   22.35    22.3   15.41
   18.54   21.57    18.3   18.52   19.44   19.45   22.31   21.48    22.3   24.05
   24.43   25.04   25.24   25.41      37
  3044.1  3244.1  3264.1  3304.1  3604.1  3734.4  3804.4  4070.8  4190.8  4200.8
  4240.8  4260.8  4309.6  4340.8  4380.8  4400.8  4410.8  4440.8  4460.2  4470.8
  4490.8  4499.2  4556.1  4614.2  4677.8  4742.1  4789.1 4789.19  4789.3 4805.31
  4805.4 5225.19  5225.3  5226.6  5247.6 5247.71  5312.9  5380.8  5438.2  5490.1
  5506.6  5701.3    5767    5821  5829.4
   25.95   23.61   22.76    23.2   18.58    18.1    18.8   15.34   15.67    15.7
   15.81   15.86      16   16.66   17.51   17.94   18.15   18.79    19.2   19.13
   18.99   18.93   18.53   19.52   20.83   21.98   22.55   22.55   25.25   25.44
   25.44   28.47   28.47   28.48   28.65   25.95   26.47   26.88   27.09   27.35
   27.85    33.8    36.2   36.89      37
   25.84    23.5   22.65   23.09   18.46   17.98   18.68   15.15   12.88   12.29
    7.71    6.44    6.48    6.82    5.04    5.39    6.39    6.85    5.76    5.17
    5.47    12.9   15.38   15.08   17.49   19.66   22.28   22.24   22.19    15.3
   18.43   21.46   18.19   18.41   19.33   19.34    22.2   21.37   22.19   23.94
   24.32   24.93   25.13    25.3   36.89
Pier Skew, UpSta & Num, DnSta & Num=  ,4898.6, 2 ,4898.6, 2 , 0 , 0 , 0 ,,
       2       2
   -5.79   20.22
       2       2
    -5.9   20.11
Pier Skew, UpSta & Num, DnSta & Num=  ,5023.3, 2 ,5023.3, 2 , 0 , 0 , 0 ,,
       2       2
  -17.83   21.12
       2       2
  -17.94   21.01
Pier Skew, UpSta & Num, DnSta & Num=  ,5110.7, 2 ,5110.7, 2 , 0 , 0 , 0 ,,
       2       2
     .62   21.75
       2       2
     .51   21.64
Pier Skew, UpSta & Num, DnSta & Num=  ,5180.9, 2 ,5180.9, 2 , 0 , 0 , 0 ,,
       2       2
   10.29   22.26
       2       2
   10.18   22.15
Abutment Skew #Up #Dn= , 2 , 2
  4805.2  4858.1
   18.54    6.87
  4805.2  4858.1
   18.43    6.76
Abutment Skew #Up #Dn= , 2 , 2
  5143.1 5225.39
    9.08   21.57
  5143.1 5225.39
    8.97   21.46
BR Coef= 1 , 1 , 0 ,1.25, 0 ,,,0.8,0,2,0,
WSPro=,,,, 1 ,,,, 0 ,,,, 0 ,,,,-1 ,-1 ,-1 , 0 , 0 , 0 , 0 , 0
BR U #Sta/Elev= 77
  3044.1   25.95  3244.1   23.61  3264.1   22.76  3304.1    23.2  3319.4   22.96
  3432.3   21.22  3570.7   19.09  3604.1   18.57  3734.4   18.09  3804.4   18.79
  3949.6   16.87  4070.8   15.26  4190.8   12.99  4200.8    12.4  4240.8    7.82
  4260.8    6.55  4309.6    6.59  4310.8    6.59  4340.8    6.93  4380.8    5.15
  4400.8     5.5  4410.8     6.5  4440.8    6.96  4460.2    5.87  4470.8    5.28
  4490.8    5.58  4499.2   13.01  4556.1   15.49  4556.2   15.49  4614.2   15.19
    4615   15.22  4675.6   17.52  4677.8    17.6  4742.1   19.77  4743.5   19.85
  4789.1   22.39 4789.19   22.35  4789.3    22.3 4789.41   22.26  4805.2   15.46
 4805.31   15.41  4805.4   15.37    4820    9.08    4858    6.88  4858.1    6.87
  4891.9   -1.36  4893.1   -2.45  4898.6   -4.69  4997.2  -14.71  5023.3  -16.91
  5103.5   -3.31    5108     .71  5110.7    2.15    5143    9.07  5143.1    9.08
  5180.9   11.35  5186.6   11.88 5225.19   18.29  5225.3    18.3  5225.4   18.32
  5226.6   18.52 5247.49   19.44  5247.6   19.44 5247.71   19.45  5312.6    22.3
  5312.9   22.31  5379.6   21.49  5380.8   21.48  5438.2    22.3  5438.9   22.32
  5488.4   24.01  5490.1   24.05  5506.6   24.43  5701.3   25.04    5767   25.24
    5821   25.41  5829.4      37
BR U #Mann= 5
  3044.1      .2  3432.3      .1  3570.7     .08  4789.1    .035  5226.6      .1
BR U Banks=4789.1,5226.6
BR D #Sta/Elev= 77
  3044.1   25.84  3244.1    23.5  3264.1   22.65  3304.1   23.09  3319.4   22.85
  3432.3   21.11  3570.7   18.98  3604.1   18.46  3734.4   17.98  3804.4   18.68
  3949.6   16.76  4070.8   15.15  4190.8   12.88  4200.8   12.29  4240.8    7.71
  4260.8    6.44  4309.6    6.48  4310.8    6.48  4340.8    6.82  4380.8    5.04
  4400.8    5.39  4410.8    6.39  4440.8    6.85  4460.2    5.76  4470.8    5.17
  4490.8    5.47  4499.2    12.9  4556.1   15.38  4556.2   15.38  4614.2   15.08
    4615   15.11  4675.6   17.41  4677.8   17.49  4742.1   19.66  4743.5   19.74
  4789.1   22.28 4789.19   22.24  4789.3   22.19 4789.41   22.15  4805.2   15.35
 4805.31    15.3  4805.4   15.26    4820    8.97    4858    6.77  4858.1    6.76
  4891.9   -1.47  4893.1   -2.56  4898.6    -4.8  4997.2  -14.82  5023.3  -17.02
  5103.5   -3.42    5108      .6  5110.7    2.04    5143    8.96  5143.1    8.97
  5180.9   11.24  5186.6   11.77 5225.19   18.18  5225.3   18.19  5225.4   18.21
  5226.6   18.41 5247.49   19.33  5247.6   19.33 5247.71   19.34  5312.6   22.19
  5312.9    22.2  5379.6   21.38  5380.8   21.37  5438.2   22.19  5438.9   22.21
  5488.4    23.9  5490.1   23.94  5506.6   24.32  5701.3   24.93    5767   25.13
    5821    25.3  5829.4   36.89
BR D #Mann= 5
  3044.1      .2  3432.3      .1  3570.7     .08  4789.1    .035  5226.6      .1
BR D Banks=4789.1,5226.6
BC Design=,, 0 ,, 0 ,,,,,,
BC HTab HWMax=37.03
BC Use User HTab Curves=0
BC User HTab FreeFlow(D)= 0

Type RM Length L Ch R = 1 ,6834.6  ,559.6,559.6,559.6
BEGIN DESCRIPTION:
Downstream Section of Bridge/Culvert/Weir
END DESCRIPTION:
XS GIS Cut Line= 6
      3154640.43      13824207.8      3155542.07     13824124.32
      3156047.55      13824051.7      3156314.81     13824005.22
      3156939.38     13823891.92      3157395.99      13823814.7
#Sta/Elev= 30
  3044.1   25.82  3432.3   21.09  3570.7   18.96  3804.4   18.66  4070.8   15.13
  4190.8   12.86  4260.8    6.42  4340.8     6.8  4380.8    5.02  4440.8    6.83
  4470.8    5.15  4490.8    5.45  4499.2   12.88  4556.1   15.36  4614.2   15.06
  4789.1   22.26    4820    8.95  4858.1    6.74  4891.9   -1.49  4898.6   -4.82
  5023.3  -17.04  5103.5   -3.44  5110.7    2.02    5143    8.94  5186.6   11.75
  5226.6   18.39  5312.9   22.18  5380.8   21.35    5821   25.28  5829.4   36.87
#Mann= 5 , 1 , 0
  3044.1      .2       0  3432.3      .1       0  3570.7     .08       0
  4789.1    .035       0  5226.6      .1       0
#XS Ineff= 2 , 0
       0    4795    15.5    5236       0   26.77
Permanent Ineff=
       F       F
Bank Sta=4789.1,5226.6
XS Rating Curve= 0 ,0
Exp/Cntr=0.5,0.3

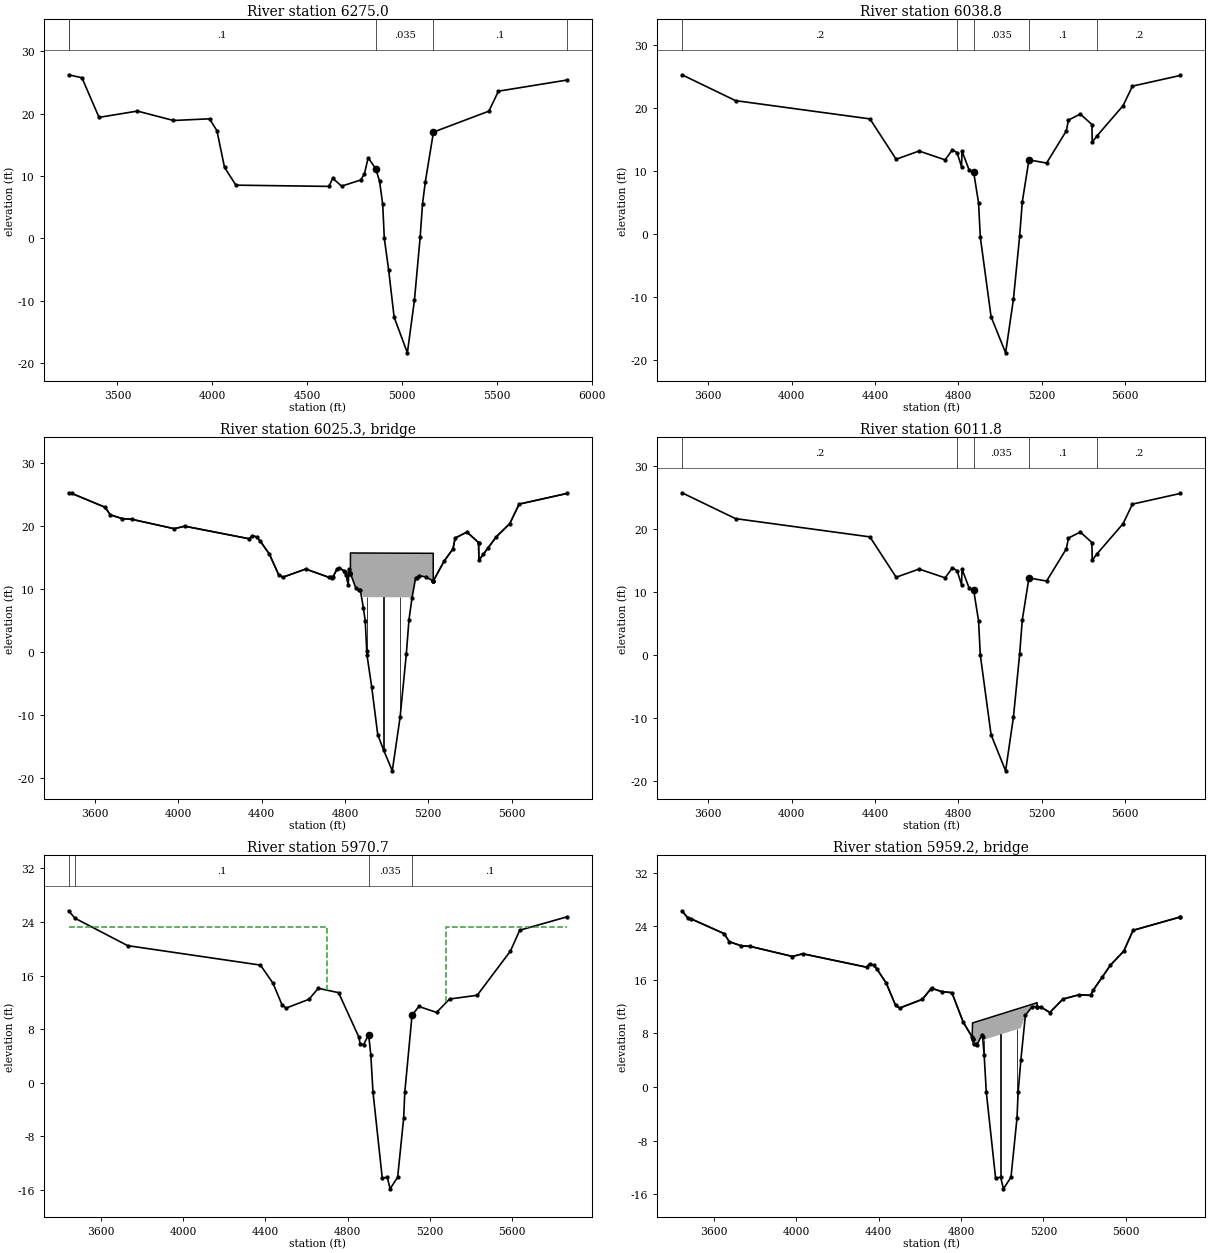
Type RM Length L Ch R = 1 ,6275.0  ,293.3,236.2,236.1
BEGIN DESCRIPTION:
Cross Section 6275.0-Interpolated
END DESCRIPTION:
XS GIS Cut Line= 6
      3155365.85     13825328.02       3155603.8     13825069.75
      3156550.43     13824538.14      3156904.08     13824389.01
      3157368.51     13824384.75      3157662.51     13824214.32
#Sta/Elev= 30
    3243   26.24    3313   25.76    3403   19.41    3605   20.42    3795   18.91
    3985   19.18    4024   17.27    4064   11.39    4124    8.54    4614    8.34
    4634    9.65  4680.7    8.38  4780.7    9.36  4800.7   10.31  4820.7   12.95
  4860.7   11.16  4880.7    9.17  4897.3    5.45  4905.6     .04  4928.4   -5.04
  4957.4  -12.63  5027.1  -18.35  5064.5   -9.87  5094.4     .16  5107.1    5.59
  5121.5    9.03  5164.5   17.05  5456.7   20.41  5506.7   23.61  5868.8    25.4
#Mann= 5 , 1 , 0
    3243      .2       0    3243      .1       0  4860.7    .035       0
  5164.5      .1       0  5868.8      .2       0
Bank Sta=4860.7,5164.5
XS Rating Curve= 0 ,0
Exp/Cntr=0.5,0.3

Type RM Length L Ch R = 1 ,6038.8  ,27,27,27
BEGIN DESCRIPTION:
Upstream Section of Bridge/Culvert/Weir
END DESCRIPTION:
XS GIS Cut Line= 6
      3155494.99     13825238.63      3155673.63     13825107.98
      3156893.11     13824644.79      3157127.03     13824566.86
      3157295.57     13824477.48      3157645.74      13824229.7
#Sta/Elev= 30
  3474.2   25.22    3731   21.12    4376   18.22  4501.9   11.82  4611.9   13.12
  4736.9   11.72  4771.9   13.32  4794.2   12.86  4815.7   10.62 4818.04    13.1
 4852.24   10.09 4873.64     9.8 4897.34     4.9 4905.64    -.51 4957.44  -13.18
 5027.14   -18.9 5064.54  -10.42 5094.44    -.39 5107.14    5.04 5139.14   11.72
 5223.74   11.21 5318.44   16.32 5328.84   18.04 5385.54   18.99 5441.14   17.33
  5442.8   14.52  5464.2   15.47  5590.8   20.32  5635.8   23.42  5866.3   25.12
#Mann= 5 , 1 , 0
  3474.2      .2       0  4794.2      .1       0 4873.64    .035       0
 5139.14      .1       0  5464.2      .2       0
#XS Ineff= 2 , 0
       0    4817   10.72    5234       0   11.26
Permanent Ineff=
       F       F
Bank Sta=4873.64,5139.14
XS Rating Curve= 0 ,0
Exp/Cntr=0.5,0.3

Type RM Length L Ch R = 3 ,6025.3  ,,,
BEGIN DESCRIPTION:
PIPELINE
END DESCRIPTION:
Bridge Culvert--1,0,-1,-1, 0
Deck Dist Width WeirC Skew NumUp NumDn MinLoCord MaxHiCord MaxSubmerge Is_Ogee
10,7,2.6,0, 50, 50, , , 0.95, 0, 1,1,,
  3474.2  3489.2  3649.2  3674.2    3731    3776    3981    4031    4341    4356
    4376  4391.9  4436.9  4481.9  4501.9  4611.9  4721.9  4731.9  4736.9  4741.9
  4761.9  4771.9  4800.7  4805.7  4815.7 4818.04 4823.04 4826.24 4826.34 4852.24
 4869.24 4873.64 4888.44 5121.54 5139.14 5145.24 5153.34 5189.34 5223.64 5223.74
 5276.44 5318.44 5328.84 5385.54 5441.14  5442.8  5525.8  5590.8  5635.8  5866.3
    25.2    25.1    22.9    21.7    21.1      21    19.5    19.9    17.9    18.4
    18.2    17.6    15.5    12.2    11.8    13.1    11.8    11.9    11.7    11.8
    13.1    13.3    12.7    12.2    10.6   13.08   12.43   12.41   15.65   15.65
   15.64   15.64   15.64   15.61   15.61   15.61   15.61    15.6    15.6   11.19
   14.39    16.3   18.02   18.97   17.31    14.5    18.2    20.3    23.4    25.1
    25.2    25.1    22.9    21.7    21.1      21    19.5    19.9    17.9    18.4
    18.2    17.6    15.5    12.2    11.8    13.1    11.8    11.9    11.7    11.8
    13.1    13.3    12.7    12.2    10.6   13.08   12.43   12.41    12.4   10.07
    9.73    9.78    8.64    8.61    11.7   11.68   12.06   11.83   11.19   11.19
   14.39    16.3   18.02   18.97   17.31    14.5    18.2    20.3    23.4    25.1
  3474.2  3489.2  3649.2  3674.2    3731    3776    3981    4031    4341    4356
    4376  4391.9  4436.9  4481.9  4501.9  4611.9  4721.9  4731.9  4736.9  4741.9
  4761.9  4771.9  4800.7  4805.7  4815.7 4818.04 4823.04 4826.24 4826.34 4852.24
 4869.24 4873.64 4888.44 5121.54 5139.14 5145.24 5153.34 5189.34 5223.64 5223.74
 5276.44 5318.44 5328.84 5385.54 5441.14  5442.8  5525.8  5590.8  5635.8  5866.3
    25.2    25.1    22.9    21.7    21.1      21    19.5    19.9    17.9    18.4
    18.2    17.6    15.5    12.2    11.8    13.1    11.8    11.9    11.7    11.8
    13.1    13.3    12.7    12.2    10.6   13.08   12.43   12.41   15.65   15.65
   15.64   15.64   15.64   15.61   15.61   15.61   15.61    15.6    15.6   11.19
   14.39    16.3   18.02   18.97   17.31    14.5    18.2    20.3    23.4    25.1
    25.2    25.1    22.9    21.7    21.1      21    19.5    19.9    17.9    18.4
    18.2    17.6    15.5    12.2    11.8    13.1    11.8    11.9    11.7    11.8
    13.1    13.3    12.7    12.2    10.6   13.08   12.43   12.41    12.4   10.07
    9.73    9.78    8.64    8.61    11.7   11.68   12.06   11.83   11.19   11.19
   14.39    16.3   18.02   18.97   17.31    14.5    18.2    20.3    23.4    25.1
Pier Skew, UpSta & Num, DnSta & Num=  ,4904.7, 2 ,4904.7, 2 , 0 , 0 , 0 ,,
     1.5     1.5
   -1.43    9.64
     1.5     1.5
   -1.43    9.64
Pier Skew, UpSta & Num, DnSta & Num=  ,4985.1, 2 ,4985.1, 2 , 0 , 0 , 0 ,,
     1.5     1.5
  -16.65    9.63
     1.5     1.5
  -16.65    9.63
Pier Skew, UpSta & Num, DnSta & Num=  ,5064.5, 2 ,5064.5, 2 , 0 , 0 , 0 ,,
     1.5     1.5
  -11.61    9.62
     1.5     1.5
  -11.61    9.62
Pier Skew, UpSta & Num, DnSta & Num=  ,5145.2, 2 ,5145.2, 2 , 0 , 0 , 0 ,,
     2.5     2.5
   10.68   12.74
     2.5     2.5
   10.68   12.74
BR Coef= 1 , 1 , 0 ,1.25, 0 ,,,0.8,-1,2,0,
WSPro=,,,, 1 ,,,, 0 ,,,, 0 ,,,,-1 ,-1 ,-1 , 0 , 0 , 0 , 0 , 0
BR U #Sta/Elev= 68
  3474.2    25.2  3489.2    25.1  3649.2    22.9  3674.2    21.7    3731    21.1
    3776      21    3981    19.5    4031    19.9    4341    17.9    4356    18.4
    4376    18.2  4391.9    17.6  4436.9    15.5  4481.9    12.2  4501.9    11.8
  4611.9    13.1  4721.9    11.8  4731.9    11.9  4736.9    11.7  4741.9    11.8
  4761.9    13.1  4771.9    13.3  4794.2   12.84  4800.7    12.7  4805.7    12.2
  4815.7    10.6 4818.04   13.08 4823.04   12.43 4826.24   12.41 4826.34    12.4
 4826.45   12.39 4826.54   12.38 4852.24   10.07 4869.24    9.73 4873.64    9.78
 4888.44    6.94 4897.34    4.88 4904.74     .05 4905.64    -.53 4928.44   -5.61
 4957.44   -13.2 4985.14  -15.59 5027.14  -18.92 5064.54  -10.44 5094.44    -.41
 5107.14    5.02 5121.54    8.46 5139.14    11.7 5145.24   11.68 5153.34   12.06
 5189.34   11.83 5223.53   11.19 5223.64   11.19 5223.74   11.19 5223.84    11.2
 5276.44   14.39 5318.44    16.3 5328.84   18.02 5385.54   18.97 5441.04    17.3
 5441.14   17.31  5442.8    14.5  5464.2   15.45  5485.8    16.4  5525.8    18.2
  5590.8    20.3  5635.8    23.4  5866.3    25.1
BR U #Mann= 5
  3474.2      .2  4794.2      .1 4873.64    .035 5139.14      .1  5464.2      .2
BR U Banks=4873.64,5139.14
BR D #Sta/Elev= 68
  3474.2    25.2  3489.2    25.1  3649.2    22.9  3674.2    21.7    3731    21.1
    3776      21    3981    19.5    4031    19.9    4341    17.9    4356    18.4
    4376    18.2  4391.9    17.6  4436.9    15.5  4481.9    12.2  4501.9    11.8
  4611.9    13.1  4721.9    11.8  4731.9    11.9  4736.9    11.7  4741.9    11.8
  4761.9    13.1  4771.9    13.3  4794.2   12.84  4800.7    12.7  4805.7    12.2
  4815.7    10.6 4818.04   13.08 4823.04   12.43 4826.24   12.41 4826.34    12.4
 4826.45   12.39 4826.54   12.38 4852.24   10.07 4869.24    9.73 4873.64    9.78
 4888.44    6.94 4897.34    4.88 4904.74     .05 4905.64    -.53 4928.44   -5.61
 4957.44   -13.2 4985.14  -15.59 5027.14  -18.92 5064.54  -10.44 5094.44    -.41
 5107.14    5.02 5121.54    8.46 5139.14    11.7 5145.24   11.68 5153.34   12.06
 5189.34   11.83 5223.53   11.19 5223.64   11.19 5223.74   11.19 5223.84    11.2
 5276.44   14.39 5318.44    16.3 5328.84   18.02 5385.54   18.97 5441.04    17.3
 5441.14   17.31  5442.8    14.5  5464.2   15.45  5485.8    16.4  5525.8    18.2
  5590.8    20.3  5635.8    23.4  5866.3    25.1
BR D #Mann= 5
  3474.2      .2  4794.2      .1 4873.64    .035 5139.14      .1  5464.2      .2
BR D Banks=4873.64,5139.14
BC Design=,, 0 ,, 0 ,,,,,,
BC HTab HWMax=25.22
BC Use User HTab Curves=0
BC User HTab FreeFlow(D)= 0

Type RM Length L Ch R = 1 ,6011.8  ,41.1,41.1,41.1
BEGIN DESCRIPTION:
Downstream Section of Bridge/Culvert/Weir
END DESCRIPTION:
XS GIS Cut Line= 6
      3155500.55     13825265.05      3155679.19      13825134.4
      3156898.67     13824671.21      3157132.59     13824593.28
      3157301.13      13824503.9      3157651.29     13824256.13
#Sta/Elev= 30
  3474.2   25.81    3731   21.71    4376   18.81  4501.9   12.41  4611.9   13.71
  4736.9   12.31  4771.9   13.91  4794.2   13.45  4815.7   11.21 4818.04   13.69
 4852.24   10.68 4873.64   10.39 4897.34    5.49 4905.64     .08 4957.44  -12.59
 5027.14  -18.31 5064.54   -9.83 5094.44      .2 5107.14    5.63 5139.14   12.31
 5223.74    11.8 5318.44   16.91 5328.84   18.63 5385.54   19.58 5441.14   17.92
  5442.8   15.11  5464.2   16.06  5590.8   20.91  5635.8   24.01  5866.3   25.71
#Mann= 5 , 1 , 0
  3474.2      .2       0  4794.2      .1       0 4873.64    .035       0
 5139.14      .1       0  5464.2      .2       0
#XS Ineff= 2 , 0
       0    4817   10.72    5234       0   11.26
Permanent Ineff=
       F       F
Bank Sta=4873.64,5139.14
XS Rating Curve= 0 ,0
Exp/Cntr=0.5,0.3

Type RM Length L Ch R = 1 ,5970.7  ,19.2,19.2,19.2
BEGIN DESCRIPTION:
Upstream Section of Bridge/Culvert/Weir
END DESCRIPTION:
XS GIS Cut Line= 2
      3155455.45     13825274.24      3157717.73     13824408.99
#Sta/Elev= 30
  3444.2   25.66  3474.2   24.56    3731   20.46    4376   17.56  4436.9   14.86
  4481.9   11.56  4501.9   11.16  4611.9   12.46 4657.02    14.1 4755.62   13.45
 4854.12    6.83 4860.72    5.76 4877.42     5.7 4901.62    7.18 4912.32    4.19
 4922.72   -1.33 4967.92  -14.21 4992.32  -14.07 5006.02  -15.81 5042.72  -14.07
 5072.02   -5.23 5077.32   -1.43 5112.62   10.08 5145.82   11.39 5231.62    10.5
 5295.22    12.5 5429.32   13.06  5590.8   19.66  5635.8   22.76  5866.3   24.76
#Mann= 4 , 1 , 0
  3444.2      .2       0  3474.2      .1       0 4901.62    .035       0
 5112.62      .1       0
#XS Ineff= 2 , 0
       0    4700    23.2    5280       0    23.2
Permanent Ineff=
       F       F
Bank Sta=4901.62,5112.62
XS Rating Curve= 0 ,0
Exp/Cntr=0.5,0.3

Type RM Length L Ch R = 3 ,5959.2  ,,,
BEGIN DESCRIPTION:
36" DIA. PIPE
END DESCRIPTION:
Bridge Culvert--1,0,-1,-1, 0
Deck Dist Width WeirC Skew NumUp NumDn MinLoCord MaxHiCord MaxSubmerge Is_Ogee
10,3,2.6,0, 57, 57, , , 0.95, 0, 1,1,,
  3444.2  3474.2  3489.2  3649.2  3674.2    3731    3776    3981    4031    4341
    4356    4376  4391.9  4436.9  4481.9  4501.9  4611.9 4654.42 4657.02 4705.12
 4755.62 4810.72 4854.12 4855.92 4856.03 4856.12 4860.72 4872.92 4877.42 4901.62
 4904.82 4912.32 4922.72 4967.92 4992.32 5006.02 5042.72 5072.02 5077.32 5090.92
 5112.62 5145.82 5169.71 5169.82 5169.92 5190.62 5231.62 5295.22 5373.42 5429.32
  5442.8  5485.8  5525.8  5590.8  5635.8  5866.2  5866.3
    26.3    25.2    25.1    22.9    21.7    21.1      21    19.5    19.9    17.9
    18.4    18.2    17.6    15.5    12.2    11.8    13.1    14.7   14.74   14.27
   14.09    9.69    7.47    9.56    9.56    9.56    9.61    9.72    9.77      10
   10.03    10.1    10.2   10.64   10.87      11   11.36   11.64   11.69   11.82
   12.03   12.35   12.58   12.58   11.96    11.9   11.14   13.14   13.78    13.7
    14.5    16.4    18.2    20.3    23.4    25.4    25.4
   26.27   25.17   25.07   22.87   21.67   21.07   20.97   19.47   19.87   17.87
   18.37   18.17   17.57   15.47   12.17   11.77   13.07   14.67   14.71   14.24
   14.06    9.66    7.44    7.15    7.13    7.12    6.58    6.69    6.74    7.79
    7.47    7.07    7.17    7.61    7.84    7.97    8.33    8.61    8.66    8.79
   10.69      12   11.93   11.93   11.93   11.87   11.11   13.11   13.75   13.67
   14.47   16.37   18.17   20.27   23.37   25.37   25.37
  3444.2  3474.2  3489.2  3649.2  3674.2    3731    3776    3981    4031    4341
    4356    4376  4391.9  4436.9  4481.9  4501.9  4611.9 4654.42 4657.02 4705.12
 4755.62 4810.72 4854.12 4855.92 4856.03 4856.12 4860.72 4872.92 4877.42 4901.62
 4904.82 4912.32 4922.72 4967.92 4992.32 5006.02 5042.72 5072.02 5077.32 5090.92
 5112.62 5145.82 5169.71 5169.82 5169.92 5190.62 5231.62 5295.22 5373.42 5429.32
  5442.8  5485.8  5525.8  5590.8  5635.8  5866.2  5866.3
    26.3    25.2    25.1    22.9    21.7    21.1      21    19.5    19.9    17.9
    18.4    18.2    17.6    15.5    12.2    11.8    13.1    14.7   14.74   14.27
   14.09    9.69    7.47    9.56    9.56    9.56    9.61    9.72    9.77      10
   10.03    10.1    10.2   10.64   10.87      11   11.36   11.64   11.69   11.82
   12.03   12.35   12.58   12.58   11.96    11.9   11.14   13.14   13.78    13.7
    14.5    16.4    18.2    20.3    23.4    25.4    25.4
    26.3    25.2    25.1    22.9    21.7    21.1      21    19.5    19.9    17.9
    18.4    18.2    17.6    15.5    12.2    11.8    13.1    14.7   14.74   14.27
   14.09    9.69    7.47    7.18    7.16    7.15    6.61    6.72    6.77    7.82
     7.5     7.1     7.2    7.64    7.87       8    8.36    8.64    8.69    8.82
   10.72   12.03   11.96   11.96   11.96    11.9   11.14   13.14   13.78    13.7
    14.5    16.4    18.2    20.3    23.4    25.4    25.4
Pier Skew, UpSta & Num, DnSta & Num=  ,4872.9, 2 ,4872.9, 2 , 0 , 0 , 0 ,,
     1.4     1.4
    5.39     7.7
     1.4     1.4
    5.42    7.73
Pier Skew, UpSta & Num, DnSta & Num=  ,4912.3, 2 ,4912.3, 2 , 0 , 0 , 0 ,,
     1.4     1.4
    3.43    8.11
     1.4     1.4
    3.46    8.14
Pier Skew, UpSta & Num, DnSta & Num=  ,4992.3, 2 ,4992.3, 2 , 0 , 0 , 0 ,,
     1.4     1.4
  -14.55    8.85
     1.4     1.4
  -14.52    8.88
Pier Skew, UpSta & Num, DnSta & Num=  ,5072, 2 ,5072, 2 , 0 , 0 , 0 ,,
     1.4     1.4
   -5.83    9.62
     1.4     1.4
    -5.8    9.65
BR Coef= 1 , 1 , 0 ,1.25, 0 ,,,0.8,0,2,0,
WSPro=,,,, 1 ,,,, 0 ,,,, 0 ,,,,-1 ,-1 ,-1 , 0 , 0 , 0 , 0 , 0
BR U #Sta/Elev= 57
  3444.2   26.27  3474.2   25.17  3489.2   25.07  3649.2   22.87  3674.2   21.67
    3731   21.07    3776   20.97    3981   19.47    4031   19.87    4341   17.87
    4356   18.37    4376   18.17  4391.9   17.57  4436.9   15.47  4481.9   12.17
  4501.9   11.77  4611.9   13.07 4654.42   14.67 4657.02   14.71 4705.12   14.24
 4755.62   14.06 4810.72    9.66 4854.12    7.44 4855.92    7.15 4856.03    7.13
 4856.12    7.12 4860.72    6.37 4872.92    6.41 4877.42    6.31 4901.62    7.79
 4904.82    7.47 4912.32     4.8 4922.72    -.72 4967.92   -13.6 4992.32  -13.46
 5006.02   -15.2 5042.72  -13.46 5072.02   -4.62 5077.32    -.82 5090.92    4.08
 5112.62   10.69 5145.82      12 5169.71   11.93 5169.82   11.93 5169.92   11.93
 5190.62   11.87 5231.62   11.11 5295.22   13.11 5373.42   13.75 5429.32   13.67
  5442.8   14.47  5485.8   16.37  5525.8   18.17  5590.8   20.27  5635.8   23.37
  5866.2   25.37  5866.3   25.37
BR U #Mann= 4
  3444.2      .2  3474.2      .1 4901.62    .035 5112.62      .1
BR U Banks=4901.62,5112.62
BR D #Sta/Elev= 57
  3444.2    26.3  3474.2    25.2  3489.2    25.1  3649.2    22.9  3674.2    21.7
    3731    21.1    3776      21    3981    19.5    4031    19.9    4341    17.9
    4356    18.4    4376    18.2  4391.9    17.6  4436.9    15.5  4481.9    12.2
  4501.9    11.8  4611.9    13.1 4654.42    14.7 4657.02   14.74 4705.12   14.27
 4755.62   14.09 4810.72    9.69 4854.12    7.47 4855.92    7.18 4856.03    7.16
 4856.12    7.15 4860.72     6.4 4872.92    6.44 4877.42    6.34 4901.62    7.82
 4904.82     7.5 4912.32    4.83 4922.72    -.69 4967.92  -13.57 4992.32  -13.43
 5006.02  -15.17 5042.72  -13.43 5072.02   -4.59 5077.32    -.79 5090.92    4.11
 5112.62   10.72 5145.82   12.03 5169.71   11.96 5169.82   11.96 5169.92   11.96
 5190.62    11.9 5231.62   11.14 5295.22   13.14 5373.42   13.78 5429.32    13.7
  5442.8    14.5  5485.8    16.4  5525.8    18.2  5590.8    20.3  5635.8    23.4
  5866.2    25.4  5866.3    25.4
BR D #Mann= 4
  3444.2      .2  3474.2      .1 4901.62    .035 5112.62      .1
BR D Banks=4901.62,5112.62
BC Design=,, 0 ,, 0 ,,,,,,
BC HTab HWMax=25.66
BC Use User HTab Curves=0
BC User HTab FreeFlow(D)= 0