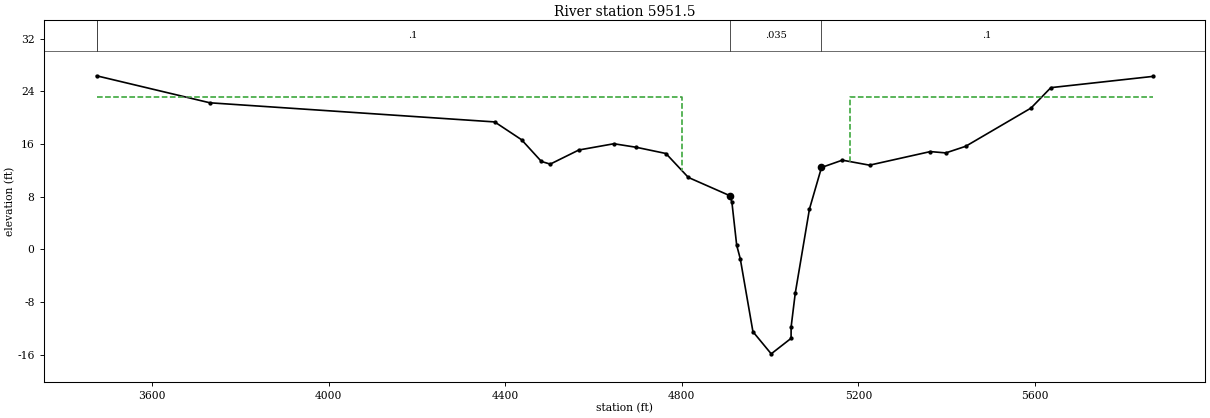
HEC-RAS study C100-00-00.prj: C100-00-00

--- C100-00-00.g01 (geometry) --- (continued)

Type RM Length L Ch R = 1 ,5951.5  ,98.6,98.6,98.6
BEGIN DESCRIPTION:
Upstream Section of Bridge/Culvert/Weir
END DESCRIPTION:
XS GIS Cut Line= 4
      3155485.54     13825276.06      3156698.44     13824816.51
      3157241.68     13824607.35       3157708.2      13824394.1
#Sta/Elev= 30
  3474.2   26.35    3731   22.25    4376   19.35  4436.9   16.65  4481.9   13.35
  4501.9   12.95  4566.6   15.09  4646.1   16.04    4697    15.5  4763.9   14.56
  4814.7   10.93  4908.7    8.16  4913.4    7.15  4924.2     .65  4932.3    -1.4
    4961  -12.47  5002.4  -15.83  5047.4  -13.48  5047.5  -11.75  5056.8   -6.66
    5089    6.13  5116.3   12.44  5163.5   13.55  5225.1   12.79  5362.8   14.85
  5397.8   14.65  5442.8   15.65  5590.8   21.45  5635.8   24.55  5866.3   26.25
#Mann= 4 , 1 , 0
  3474.2      .2       0  3474.2      .1       0  4908.7    .035       0
  5116.3      .1       0
#XS Ineff= 2 , 0
       0    4800    23.2    5180       0    23.2
Permanent Ineff=
       F       F
Bank Sta=4908.7,5116.3
XS Rating Curve= 0 ,0
Exp/Cntr=0.5,0.3