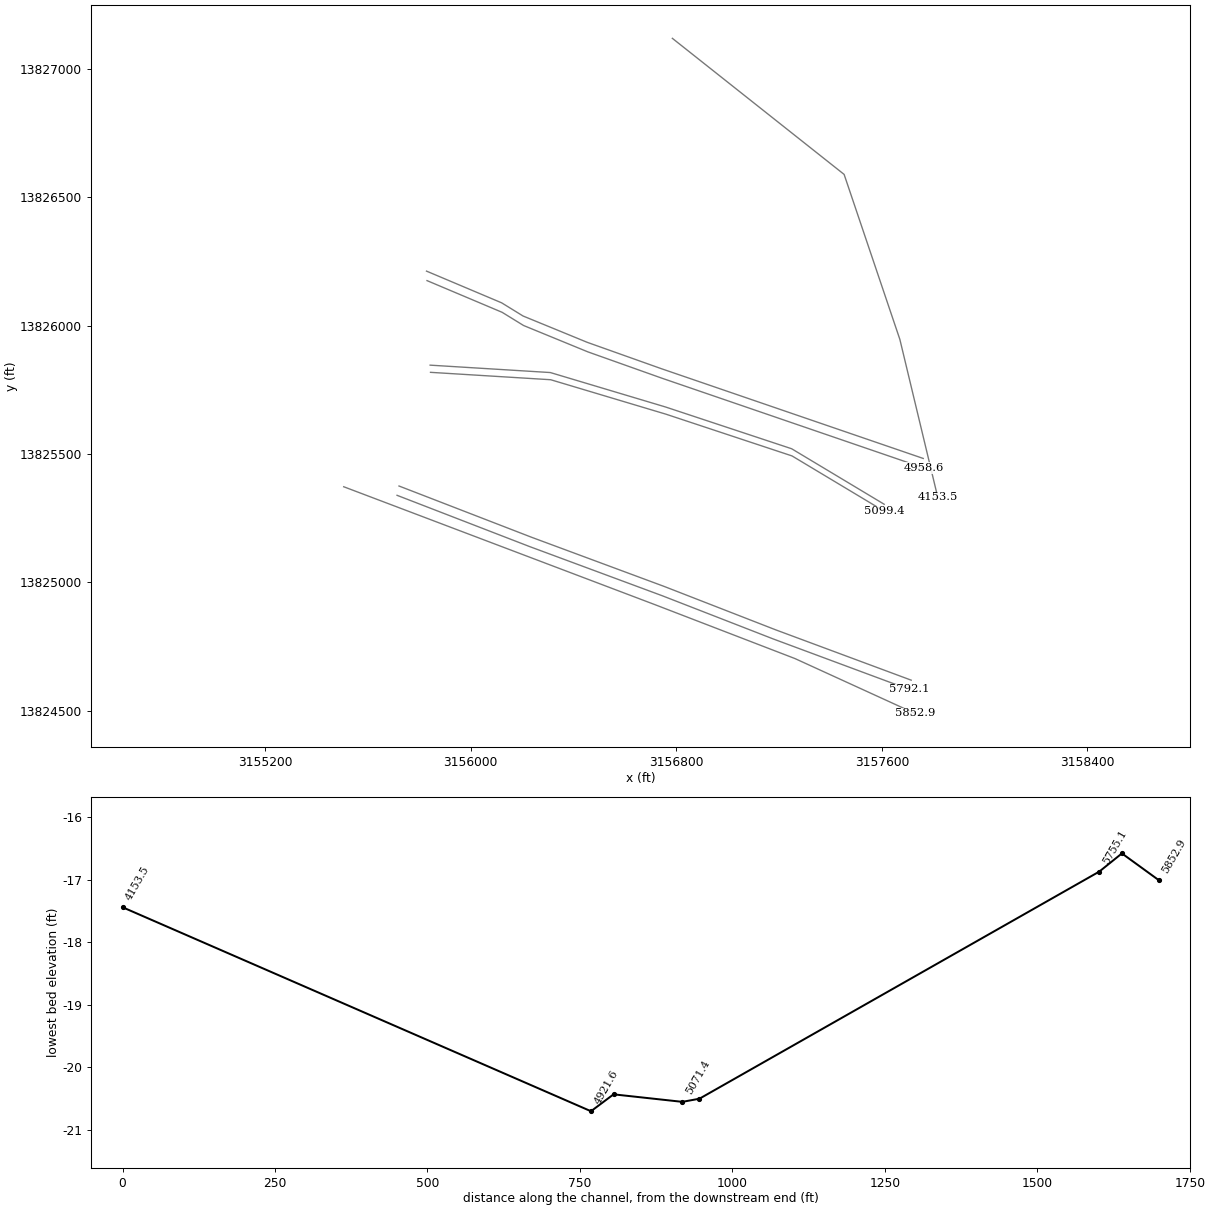
HEC-RAS study C100-00-00.prj: C100-00-00

--- C100-00-00.g01 (geometry) --- (continued)

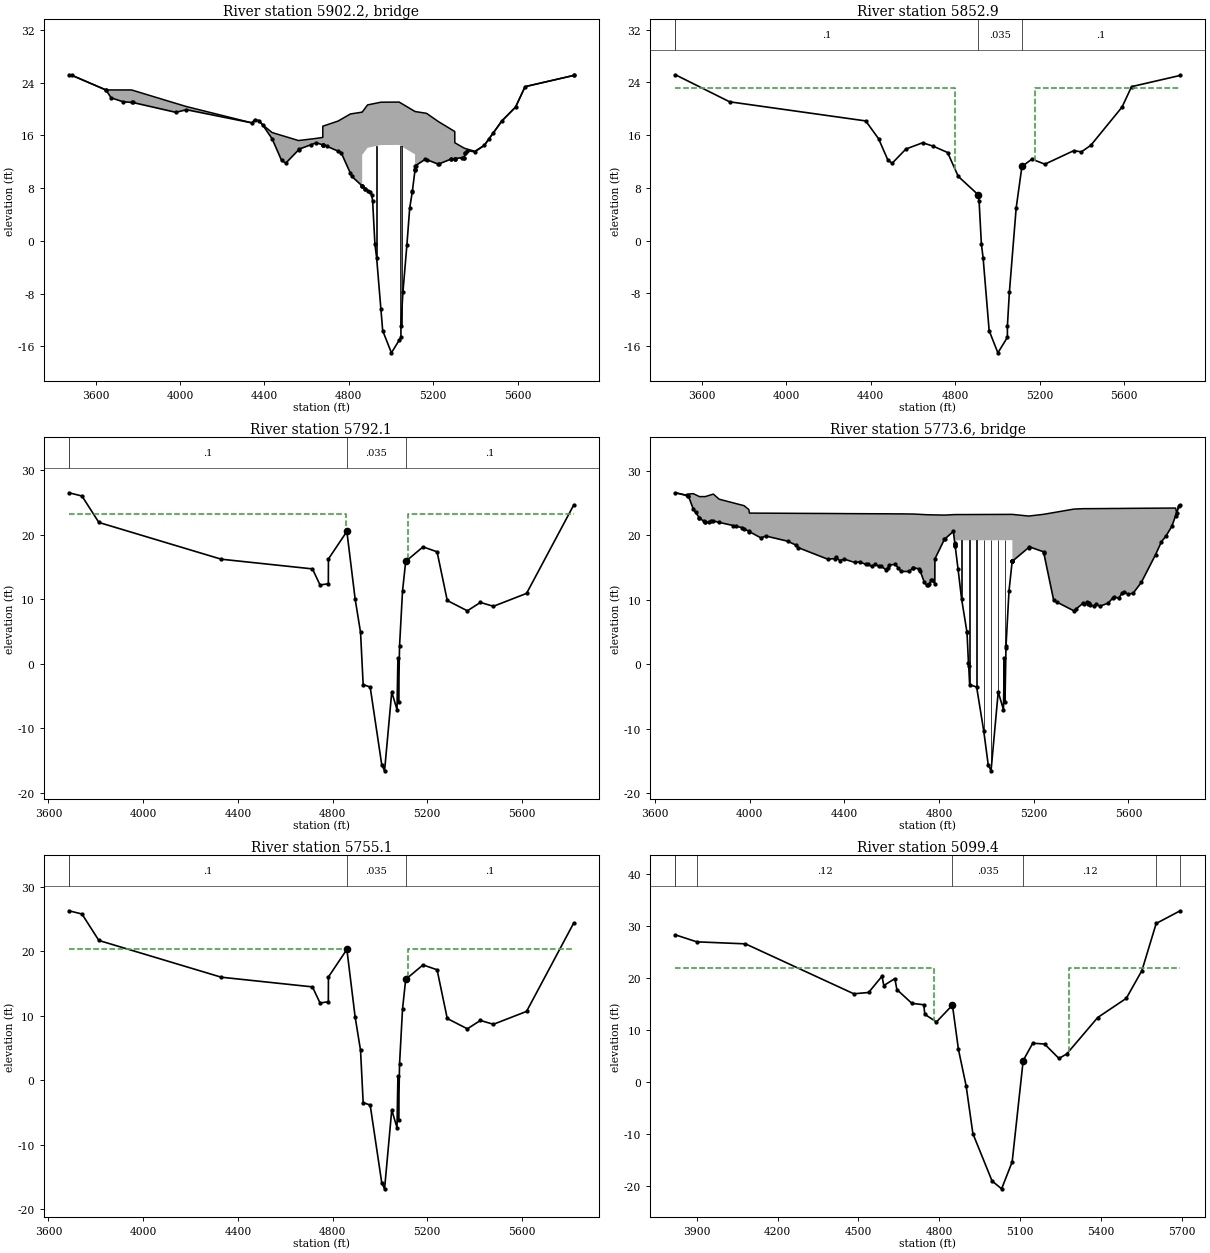
Type RM Length L Ch R = 3 ,5902.2  ,,,
BEGIN DESCRIPTION:
LAWNDALE ROAD
Structure ID: C00-4
END DESCRIPTION:
Bridge Culvert--1,0,-1,-1, 0
Deck Dist Width WeirC Skew NumUp NumDn MinLoCord MaxHiCord MaxSubmerge Is_Ogee
10,78.6,2.6,0, 49, 49, , , 0.95, 0, 1,1,,
  3474.2  3489.2  3649.2  3674.2    3731  3770.9    3981    4031    4341    4356
    4376  4391.9  4436.9  4481.9  4501.9  4562.3  4566.6  4646.1 4677.09  4677.2
  4749.8  4763.9  4807.4  4814.7  4863.7 4863.81  4863.9  4889.3  4952.6    5039
 5114.39  5114.5  5116.3  5117.5  5163.5  5168.8  5225.1  5283.2  5302.7 5302.81
  5345.7  5352.8  5362.8  5397.8  5442.8  5525.8  5590.8  5635.8  5866.3
    25.2    25.1    22.9    22.9    22.9    22.9   20.86   20.38   17.91   18.41
   18.21   17.61   16.44      16   15.81   15.22   15.24   15.55    15.7    17.4
   18.18   18.44   19.25   19.29   19.53   19.53   19.54   20.63   21.04   21.06
   19.63   19.63   19.62   19.61   19.38   19.35    18.1   16.97   16.59   14.89
    14.1   14.01   13.92    13.6   14.51    18.2    20.3    23.4    25.1
    25.2    25.1    22.9    21.7    21.1   21.01    19.5    19.9    17.9    18.4
    18.2    17.6    15.5    12.2    11.8    13.8   13.94   14.89   14.56   14.56
   13.61   13.41    10.3    9.78    8.34    8.34   13.04   14.13   14.54   14.56
   13.13   10.83   11.29   11.43    12.4   12.33   11.64   12.39   12.48   12.48
   12.64    13.3    13.7    13.5    14.5    18.2    20.3    23.4    25.1
  3474.2  3489.2  3649.2  3674.2    3731  3770.9    3981    4031    4341    4356
    4376  4391.9  4436.9  4481.9  4501.9  4562.3  4566.6  4646.1 4677.09  4677.2
  4749.8  4763.9  4807.4  4814.7  4863.7 4863.81  4863.9  4889.3  4952.6    5039
 5114.39  5114.5  5116.3  5117.5  5163.5  5168.8  5225.1  5283.2  5302.7 5302.81
  5345.7  5352.8  5362.8  5397.8  5442.8  5525.8  5590.8  5635.8  5866.3
    25.2    25.1    22.9    22.9    22.9    22.9   20.86   20.38   17.91   18.41
   18.21   17.61   16.44      16   15.81   15.22   15.24   15.55    15.7    17.4
   18.18   18.44   19.25   19.29   19.53   19.53   19.54   20.63   21.04   21.06
   19.63   19.63   19.62   19.61   19.38   19.35    18.1   16.97   16.59   14.89
    14.1   14.01   13.92    13.6   14.51    18.2    20.3    23.4    25.1
    25.1      25    22.8    21.6      21   20.91    19.4    19.8    17.8    18.3
    18.1    17.5    15.4    12.1    11.7    13.7   13.84   14.79   14.46   14.46
   13.51   13.31    10.2    9.68    8.24    8.24   12.94   14.03   14.44   14.46
   13.03   10.73   11.19   11.33    12.3   12.23   11.54   12.29   12.38   12.38
   12.54    13.2    13.6    13.4    14.4    18.1    20.2    23.3      25
Pier Skew, UpSta & Num, DnSta & Num=  ,4932.3, 2 ,4932.3, 2 , 0 , 0 , 0 ,,
     6.5     6.5
    -4.8   15.43
     6.5     6.5
    -4.9   15.33
Pier Skew, UpSta & Num, DnSta & Num=  ,5047.5, 2 ,5047.5, 2 , 0 , 0 , 0 ,,
     6.5     6.5
  -15.79   15.46
     6.5     6.5
   -15.9   15.36
Abutment Skew #Up #Dn= , 2 , 2
  4863.7  4877.8
   13.04    7.93
  4863.7  4877.8
   12.94    7.83
Abutment Skew #Up #Dn= , 2 , 2
  5101.5 5114.59
     7.5   13.13
  5101.5 5114.59
     7.4   13.03
BR Coef= 1 , 1 , 0 ,1.25, 0 ,,,0.8,-1,2,0,
WSPro=,,,, 1 ,,,, 0 ,,,, 0 ,,,,-1 ,-1 ,-1 , 0 , 0 , 0 , 0 , 0
BR U #Sta/Elev= 81
  3474.2    25.2  3489.2    25.1  3649.2    22.9  3650.9   22.82  3674.2    21.7
    3731    21.1  3770.9   21.01    3776      21    3981    19.5    4031    19.9
    4341    17.9    4356    18.4    4376    18.2  4391.9    17.6  4436.9    15.5
  4481.9    12.2  4501.9    11.8  4562.3    13.8  4566.6   13.94  4622.2    14.6
  4646.1   14.89 4677.09   14.56  4677.2   14.56 4677.31   14.56  4680.4   14.53
    4697   14.35  4749.8   13.61  4763.9   13.41  4807.4    10.3  4814.7    9.78
  4863.7    8.34 4863.81    8.34  4863.9    8.34  4877.7    7.93  4877.8    7.93
  4889.3    7.62  4898.7    7.37  4908.7    7.01  4913.4       6  4924.2     -.5
  4932.3   -2.55  4952.6  -10.38    4961  -13.62  5002.4  -16.98    5039  -15.07
  5047.4  -14.63  5047.5   -12.9  5056.8   -7.81  5075.7    -.61    5089    4.98
  5101.4    7.47  5101.5     7.5 5114.39    10.8  5114.5   10.83  5114.6   10.85
  5116.3   11.29  5117.5   11.43  5163.5    12.4  5168.8   12.33  5225.1   11.64
  5228.3   11.68  5283.2   12.39  5284.3    12.4 5302.59   12.48  5302.7   12.48
 5302.81   12.48  5339.2   12.63  5344.8   12.65  5345.7   12.64  5352.8    13.3
  5353.3   13.32  5362.8    13.7  5397.8    13.5  5442.8    14.5  5465.1   15.49
  5485.8    16.4  5525.8    18.2  5590.8    20.3  5635.8    23.4  5866.2    25.1
  5866.3    25.1
BR U #Mann= 4
  3474.2      .2  3474.2      .1  4908.7    .035  5116.3      .1
BR U Banks=4908.7,5116.3
BR D #Sta/Elev= 81
  3474.2    25.1  3489.2      25  3649.2    22.8  3650.9   22.72  3674.2    21.6
    3731      21  3770.9   20.91    3776    20.9    3981    19.4    4031    19.8
    4341    17.8    4356    18.3    4376    18.1  4391.9    17.5  4436.9    15.4
  4481.9    12.1  4501.9    11.7  4562.3    13.7  4566.6   13.84  4622.2    14.5
  4646.1   14.79 4677.09   14.46  4677.2   14.46 4677.31   14.46  4680.4   14.43
    4697   14.25  4749.8   13.51  4763.9   13.31  4807.4    10.2  4814.7    9.68
  4863.7    8.24 4863.81    8.24  4863.9    8.24  4877.7    7.83  4877.8    7.83
  4889.3    7.52  4898.7    7.27  4908.7    6.91  4913.4     5.9  4924.2     -.6
  4932.3   -2.65  4952.6  -10.48    4961  -13.72  5002.4  -17.08    5039  -15.17
  5047.4  -14.73  5047.5     -13  5056.8   -7.91  5075.7    -.71    5089    4.88
  5101.4    7.37  5101.5     7.4 5114.39    10.7  5114.5   10.73  5114.6   10.75
  5116.3   11.19  5117.5   11.33  5163.5    12.3  5168.8   12.23  5225.1   11.54
  5228.3   11.58  5283.2   12.29  5284.3    12.3 5302.59   12.38  5302.7   12.38
 5302.81   12.38  5339.2   12.53  5344.8   12.55  5345.7   12.54  5352.8    13.2
  5353.3   13.22  5362.8    13.6  5397.8    13.4  5442.8    14.4  5465.1   15.39
  5485.8    16.3  5525.8    18.1  5590.8    20.2  5635.8    23.3  5866.2      25
  5866.3      25
BR D #Mann= 4
  3474.2      .2  3474.2      .1  4908.7    .035  5116.3      .1
BR D Banks=4908.7,5116.3
BC Design=,, 0 ,, 0 ,,,,,,
BC HTab HWMax=26.35
BC Use User HTab Curves=0
BC User HTab FreeFlow(D)= 0

Type RM Length L Ch R = 1 ,5852.9  ,60.8,60.8,60.8
BEGIN DESCRIPTION:
Downstream Section of Bridge/Culvert/Weir
END DESCRIPTION:
XS GIS Cut Line= 4
      3155505.82     13825372.55      3156718.72     13824913.01
      3157261.96     13824703.85      3157728.47     13824490.59
#Sta/Elev= 30
  3474.2   25.17    3731   21.07    4376   18.17  4436.9   15.47  4481.9   12.17
  4501.9   11.77  4566.6   13.91  4646.1   14.86    4697   14.32  4763.9   13.38
  4814.7    9.75  4908.7    6.98  4913.4    5.97  4924.2    -.53  4932.3   -2.58
    4961  -13.65  5002.4  -17.01  5047.4  -14.66  5047.5  -12.93  5056.8   -7.84
    5089    4.95  5116.3   11.26  5163.5   12.37  5225.1   11.61  5362.8   13.67
  5397.8   13.47  5442.8   14.47  5590.8   20.27  5635.8   23.37  5866.3   25.07
#Mann= 4 , 1 , 0
  3474.2      .2       0  3474.2      .1       0  4908.7    .035       0
  5116.3      .1       0
#XS Ineff= 2 , 0
       0    4800    23.2    5180       0   23.23
Permanent Ineff=
       F       F
Bank Sta=4908.7,5116.3
XS Rating Curve= 0 ,0
Exp/Cntr=0.5,0.3

Type RM Length L Ch R = 1 ,5792.1  ,37,37,37
BEGIN DESCRIPTION:
Upstream Section of Bridge/Culvert/Weir
END DESCRIPTION:
XS GIS Cut Line= 5
      3155713.36      13825339.2      3156228.36     13825140.07
      3156745.45     13824948.34       3157178.3     13824779.85
       3157706.6     13824583.62
#Sta/Elev= 30
  3686.6   26.53  3741.5   26.03  3812.8   21.93  4329.9   16.23  4714.9   14.73
    4747   12.23    4782   12.43  4782.4   16.27  4860.3   20.54  4895.2   10.06
    4918    4.89  4929.1   -3.21  4958.7   -3.59  5007.5  -15.62  5019.5  -16.58
  5049.8   -4.35    5072   -7.09  5075.8     .84  5078.4   -5.91  5082.7    2.73
  5095.3   11.29  5108.7   15.89  5181.9   18.14  5241.3   17.38  5284.2    9.83
  5369.2    8.23  5424.2    9.53  5479.2    8.93  5619.2   10.93  5818.3   24.63
#Mann= 4 , 1 , 0
  3686.6      .2       0  3686.6      .1       0  4860.3    .035       0
  5108.7      .1       0
#XS Ineff= 2 , 0
       0    4857   23.22    5119       0   23.26
Permanent Ineff=
       F       F
Bank Sta=4860.3,5108.7
XS Rating Curve= 0 ,0
Exp/Cntr=0.5,0.3

Type RM Length L Ch R = 3 ,5773.6  ,,,
BEGIN DESCRIPTION:
SOUTHERN PACIFIC RR
Structure ID: C00-3
END DESCRIPTION:
Bridge Culvert--1,0,-1,-1, 0
Deck Dist Width WeirC Skew NumUp NumDn MinLoCord MaxHiCord MaxSubmerge Is_Ogee
10,17,2.6,0, 60, 60, , , 0.95, 0, 1,1,,
  3686.6  3741.5  3741.6  3761.6  3787.8  3812.8  3846.6  3871.6  3976.6  3996.6
  3999.1  4047.8  4067.8  4159.9  4204.9  4329.9  4364.9  4379.9  4399.9  4464.9
  4514.9  4529.9  4574.9  4589.9  4614.9  4639.9  4674.9  4689.9  4714.9    4737
    4747    4757    4767    4782  4782.4  4822.7  4860.3 4867.81  4867.9 5109.49
  5109.6  5178.5  5241.3  5284.2  5369.2  5409.2  5424.2  5479.2  5514.2  5539.2
  5559.2  5579.2  5619.2  5654.2  5739.2  5783.3  5799.1  5803.3  5813.3  5818.3
    26.6    26.1    26.4   26.47   26.01   26.01    26.4    25.6    24.6      24
   23.45   23.44   23.44   23.42   23.41   23.39   23.38   23.38   23.37   23.36
   23.35   23.35   23.34   23.34   23.33   23.33   23.31   23.31   23.26   23.22
    23.2   23.19   23.18   23.17   23.17   23.14   23.21   23.22   23.22   23.25
   23.25   22.99   23.26   23.53   24.07   24.14   24.14   24.15   24.16   24.17
   24.17   24.18   24.19    24.2   24.22   24.23   24.23    23.5    24.6    24.7
    26.6    26.1   26.09    24.1    22.7      22   22.23   22.01   21.02   20.62
   20.57    19.6    19.9    19.1    18.1    16.3    16.6    16.1    16.3    15.9
    15.2    15.5    14.7    15.4    15.5    14.4    14.4      15    14.8    12.8
    12.3    12.4      13    12.5   16.34   19.38   20.61    18.4   19.22   19.25
   15.99   18.11   17.45     9.9     8.3     9.5     9.6       9     9.5    10.4
    10.3    11.2      11    12.7      19    21.4   23.06    23.5    24.6    24.7
  3686.6  3741.5  3741.6  3761.6  3787.8  3812.8  3846.6  3871.6  3976.6  3996.6
  3999.1  4047.8  4067.8  4159.9  4204.9  4329.9  4364.9  4379.9  4399.9  4464.9
  4514.9  4529.9  4574.9  4589.9  4614.9  4639.9  4674.9  4689.9  4714.9    4737
    4747    4757    4767    4782  4782.4  4822.7  4860.3 4867.81  4867.9 5109.49
  5109.6  5178.5  5241.3  5284.2  5369.2  5409.2  5424.2  5479.2  5514.2  5539.2
  5559.2  5579.2  5619.2  5654.2  5739.2  5783.3  5799.1  5803.3  5813.3  5818.3
    26.6    26.1    26.4   26.47   26.01   26.01    26.4    25.6    24.6      24
   23.45   23.44   23.44   23.42   23.41   23.39   23.38   23.38   23.37   23.36
   23.35   23.35   23.34   23.34   23.33   23.33   23.31   23.31   23.26   23.22
    23.2   23.19   23.18   23.17   23.17   23.14   23.21   23.22   23.22   23.25
   23.25   22.99   23.26   23.53   24.07   24.14   24.14   24.15   24.16   24.17
   24.17   24.18   24.19    24.2   24.22   24.23   24.23    23.5    24.6    24.7
    26.3    25.8   25.79    23.8    22.4    21.7   21.93   21.71   20.72   20.32
   20.27    19.3    19.6    18.8    17.8      16    16.3    15.8      16    15.6
    14.9    15.2    14.4    15.1    15.2    14.1    14.1    14.7    14.5    12.5
      12    12.1    12.7    12.2   16.04   19.08   20.31    18.1   18.92   18.95
   15.69   17.81   17.15     9.6       8     9.2     9.3     8.7     9.2    10.1
      10    10.9    10.7    12.4    18.7    21.1   22.76    23.2    24.3    24.4
Pier Skew, UpSta & Num, DnSta & Num=  ,4895.2, 2 ,4895.2, 2 , 0 , 0 , 0 ,,
     1.4     1.4
    8.97   20.22
     1.4     1.4
    8.67   19.92
Pier Skew, UpSta & Num, DnSta & Num=  ,4929.1, 2 ,4929.1, 2 , 0 , 0 , 0 ,,
     1.4     1.4
   -4.15   20.23
     1.4     1.4
   -4.45   19.93
Pier Skew, UpSta & Num, DnSta & Num=  ,4958.7, 2 ,4958.7, 2 , 0 , 0 , 0 ,,
     1.4     1.4
   -4.68   20.23
     1.4     1.4
   -4.98   19.93
Pier Skew, UpSta & Num, DnSta & Num=  ,4988.9, 2 ,4988.9, 2 , 0 , 0 , 0 ,,
     1.4     1.4
  -11.57   20.24
     1.4     1.4
  -11.87   19.94
Pier Skew, UpSta & Num, DnSta & Num=  ,5019.5, 2 ,5019.5, 2 , 0 , 0 , 0 ,,
     1.4     1.4
  -17.45   20.24
     1.4     1.4
  -17.75   19.94
Pier Skew, UpSta & Num, DnSta & Num=  ,5049.8, 2 ,5049.8, 2 , 0 , 0 , 0 ,,
     1.4     1.4
   -5.56   20.24
     1.4     1.4
   -5.86   19.94
Pier Skew, UpSta & Num, DnSta & Num=  ,5078.4, 2 ,5078.4, 2 , 0 , 0 , 0 ,,
     1.4     1.4
   -5.43   20.25
     1.4     1.4
   -5.73   19.95
Abutment Skew #Up #Dn= , 2 , 2
  4867.7    4918
   19.22    4.96
  4867.7    4918
   18.92    4.66
Abutment Skew #Up #Dn= , 2 , 2
  5082.7 5109.69
     2.8   19.25
  5082.7 5109.69
     2.5   18.95
BR Coef= 1 , 1 , 0 ,1.25, 0 ,,,0.8,0,2,0,
WSPro=,,,, 1 ,,,, 0 ,,,, 0 ,,,,-1 ,-1 ,-1 , 0 , 0 , 0 , 0 , 0
BR U #Sta/Elev= 126
  3686.6    26.6  3736.6    26.2  3741.5    26.1  3741.6   26.09  3761.6    24.1
  3771.6   23.57  3786.6   22.76  3787.8    22.7  3806.6   22.17  3811.6   22.03
  3812.8      22  3827.8      22  3837.8    22.3  3846.6   22.23  3871.6   22.01
  3931.6   21.51  3941.6   21.42  3967.8    21.2  3976.6   21.02  3996.6   20.62
  3999.1   20.57  4047.8    19.6  4067.8    19.9  4159.9    19.1  4194.9    18.5
  4204.9    18.1  4329.9    16.3  4359.9    16.4  4364.9    16.6  4379.9    16.1
  4399.9    16.3  4444.9    15.8  4464.9    15.9  4489.9    15.5  4499.9    15.5
  4514.9    15.2  4529.9    15.5  4544.9    15.2  4554.9    15.2  4574.9    14.7
  4584.9      15  4589.9    15.4  4614.9    15.5  4628.2   14.91  4639.9    14.4
  4674.9    14.4  4688.3   14.94  4689.9      15  4714.9    14.8  4719.9    14.5
    4737    12.8    4747    12.3  4754.4   12.37    4757    12.4    4767      13
    4772      13    4782    12.5  4782.4   16.34  4822.7   19.38  4823.5   19.41
  4860.3   20.61 4866.59   18.76  4866.7   18.73 4866.81    18.7  4867.7   18.43
 4867.81    18.4  4867.9   18.38  4880.1   14.79  4895.2   10.13  4917.9    4.98
    4918    4.96  4924.2     .14  4925.3    -.27  4929.1   -3.14  4958.7   -3.52
  4988.9  -10.38  5007.5  -15.55  5019.5  -16.51  5049.8   -4.28    5072   -7.02
  5075.8     .91  5078.4   -5.84  5082.6     2.6  5082.7     2.8  5095.3   11.36
  5108.7   15.96 5109.49   15.98  5109.6   15.99  5109.7   15.99 5109.79   15.99
  5109.9      16 5110.01      16  5178.5   18.11  5181.9   18.21  5241.3   17.45
  5241.9   17.34  5284.2     9.9  5297.5    9.65  5369.2     8.3  5378.5    8.58
  5409.2     9.5  5414.2     9.3  5424.2     9.6  5429.2     9.4  5434.2     9.5
  5439.2     9.2  5454.2     9.1  5464.2     9.3  5479.2       9  5514.2     9.5
  5534.2    10.3  5539.2    10.4  5559.2    10.3  5574.2    11.1  5579.2    11.2
  5599.2    10.9  5619.2      11  5654.2    12.7  5714.2      17  5739.2      19
  5758.3    19.9  5783.3    21.4  5799.1   23.06  5803.3    23.5  5813.3    24.6
  5818.3    24.7
BR U #Mann= 4
  3686.6      .2  3686.6      .1  4860.3    .035  5108.7      .1
BR U Banks=4860.3,5108.7
BR D #Sta/Elev= 126
  3686.6    26.3  3736.6    25.9  3741.5    25.8  3741.6   25.79  3761.6    23.8
  3771.6   23.27  3786.6   22.46  3787.8    22.4  3806.6   21.87  3811.6   21.73
  3812.8    21.7  3827.8    21.7  3837.8      22  3846.6   21.93  3871.6   21.71
  3931.6   21.21  3941.6   21.12  3967.8    20.9  3976.6   20.72  3996.6   20.32
  3999.1   20.27  4047.8    19.3  4067.8    19.6  4159.9    18.8  4194.9    18.2
  4204.9    17.8  4329.9      16  4359.9    16.1  4364.9    16.3  4379.9    15.8
  4399.9      16  4444.9    15.5  4464.9    15.6  4489.9    15.2  4499.9    15.2
  4514.9    14.9  4529.9    15.2  4544.9    14.9  4554.9    14.9  4574.9    14.4
  4584.9    14.7  4589.9    15.1  4614.9    15.2  4628.2   14.61  4639.9    14.1
  4674.9    14.1  4688.3   14.64  4689.9    14.7  4714.9    14.5  4719.9    14.2
    4737    12.5    4747      12  4754.4   12.07    4757    12.1    4767    12.7
    4772    12.7    4782    12.2  4782.4   16.04  4822.7   19.08  4823.5   19.11
  4860.3   20.31 4866.59   18.46  4866.7   18.43 4866.81    18.4  4867.7   18.13
 4867.81    18.1  4867.9   18.08  4880.1   14.49  4895.2    9.83  4917.9    4.68
    4918    4.66  4924.2    -.16  4925.3    -.57  4929.1   -3.44  4958.7   -3.82
  4988.9  -10.68  5007.5  -15.85  5019.5  -16.81  5049.8   -4.58    5072   -7.32
  5075.8     .61  5078.4   -6.14  5082.6     2.3  5082.7     2.5  5095.3   11.06
  5108.7   15.66 5109.49   15.68  5109.6   15.69  5109.7   15.69 5109.79   15.69
  5109.9    15.7 5110.01    15.7  5178.5   17.81  5181.9   17.91  5241.3   17.15
  5241.9   17.04  5284.2     9.6  5297.5    9.35  5369.2       8  5378.5    8.28
  5409.2     9.2  5414.2       9  5424.2     9.3  5429.2     9.1  5434.2     9.2
  5439.2     8.9  5454.2     8.8  5464.2       9  5479.2     8.7  5514.2     9.2
  5534.2      10  5539.2    10.1  5559.2      10  5574.2    10.8  5579.2    10.9
  5599.2    10.6  5619.2    10.7  5654.2    12.4  5714.2    16.7  5739.2    18.7
  5758.3    19.6  5783.3    21.1  5799.1   22.76  5803.3    23.2  5813.3    24.3
  5818.3    24.4
BR D #Mann= 4
  3686.6      .2  3686.6      .1  4860.3    .035  5108.7      .1
BR D Banks=4860.3,5108.7
BC Design=,, 0 ,, 0 ,,,,,,
BC HTab HWMax=26.53
BC Use User HTab Curves=0
BC User HTab FreeFlow(D)= 0

Type RM Length L Ch R = 1 ,5755.1  ,655.7,655.7,655.7
BEGIN DESCRIPTION:
Downstream Section of Bridge/Culvert/Weir
END DESCRIPTION:
XS GIS Cut Line= 5
      3155720.97     13825375.41      3156235.96     13825176.27
      3156753.05     13824984.54       3157185.9     13824816.05
       3157714.2     13824619.83
#Sta/Elev= 30
  3686.6   26.24  3741.5   25.74  3812.8   21.64  4329.9   15.94  4714.9   14.44
    4747   11.94    4782   12.14  4782.4   15.98  4860.3   20.25  4895.2    9.77
    4918     4.6  4929.1    -3.5  4958.7   -3.88  5007.5  -15.91  5019.5  -16.87
  5049.8   -4.64    5072   -7.38  5075.8     .55  5078.4    -6.2  5082.7    2.44
  5095.3      11  5108.7    15.6  5181.9   17.85  5241.3   17.09  5284.2    9.54
  5369.2    7.94  5424.2    9.24  5479.2    8.64  5619.2   10.64  5818.3   24.34
#Mann= 4 , 1 , 0
  3686.6      .2       0  3686.6      .1       0  4860.3    .035       0
  5108.7      .1       0
#XS Ineff= 2 , 0
       0    4857   20.32    5119       0   20.36
Permanent Ineff=
       F       F
Bank Sta=4860.3,5108.7
XS Rating Curve= 0 ,0
Exp/Cntr=0.5,0.3

Type RM Length L Ch R = 1 ,5099.4  ,28,28,28
BEGIN DESCRIPTION:
Upstream Section of Bridge/Culvert/Weir
END DESCRIPTION:
XS GIS Cut Line= 5
       3155843.6      13825817.8      3156311.29     13825789.02
      3156759.65     13825654.98      3157250.49     13825492.45
      3157610.57     13825276.44
#Sta/Elev= 30
  3820.8   28.33    3900   26.99  4080.8    26.6  4482.8      17  4537.8   17.25
 4587.36   20.37 4594.36   18.59 4635.16   19.92 4642.86   17.81 4698.26   15.17
 4742.66   14.89 4746.36   13.05 4789.66   11.59 4848.96   14.82 4871.26     6.3
 4899.66    -.66 4924.86   -9.88 4995.96  -18.98 5031.46   -20.5 5070.66  -15.32
 5111.56    4.17 5147.16     7.5 5191.06    7.34 5244.26    4.57 5272.86    5.42
 5388.26   12.44 5494.36   16.13  5552.3   21.47  5605.2   30.52  5694.3   32.96
#Mann= 7 , 1 , 0
  3820.8      .2       0  3820.8      .1       0    3900     .12       0
 4848.96    .035       0 5111.56     .12       0  5605.2      .1       0
  5694.3      .2       0
#XS Ineff= 2 , 0
       0    4782      22    5280       0      22
Permanent Ineff=
       F       F
Bank Sta=4848.96,5111.56
XS Rating Curve= 0 ,0
Exp/Cntr=0.5,0.3

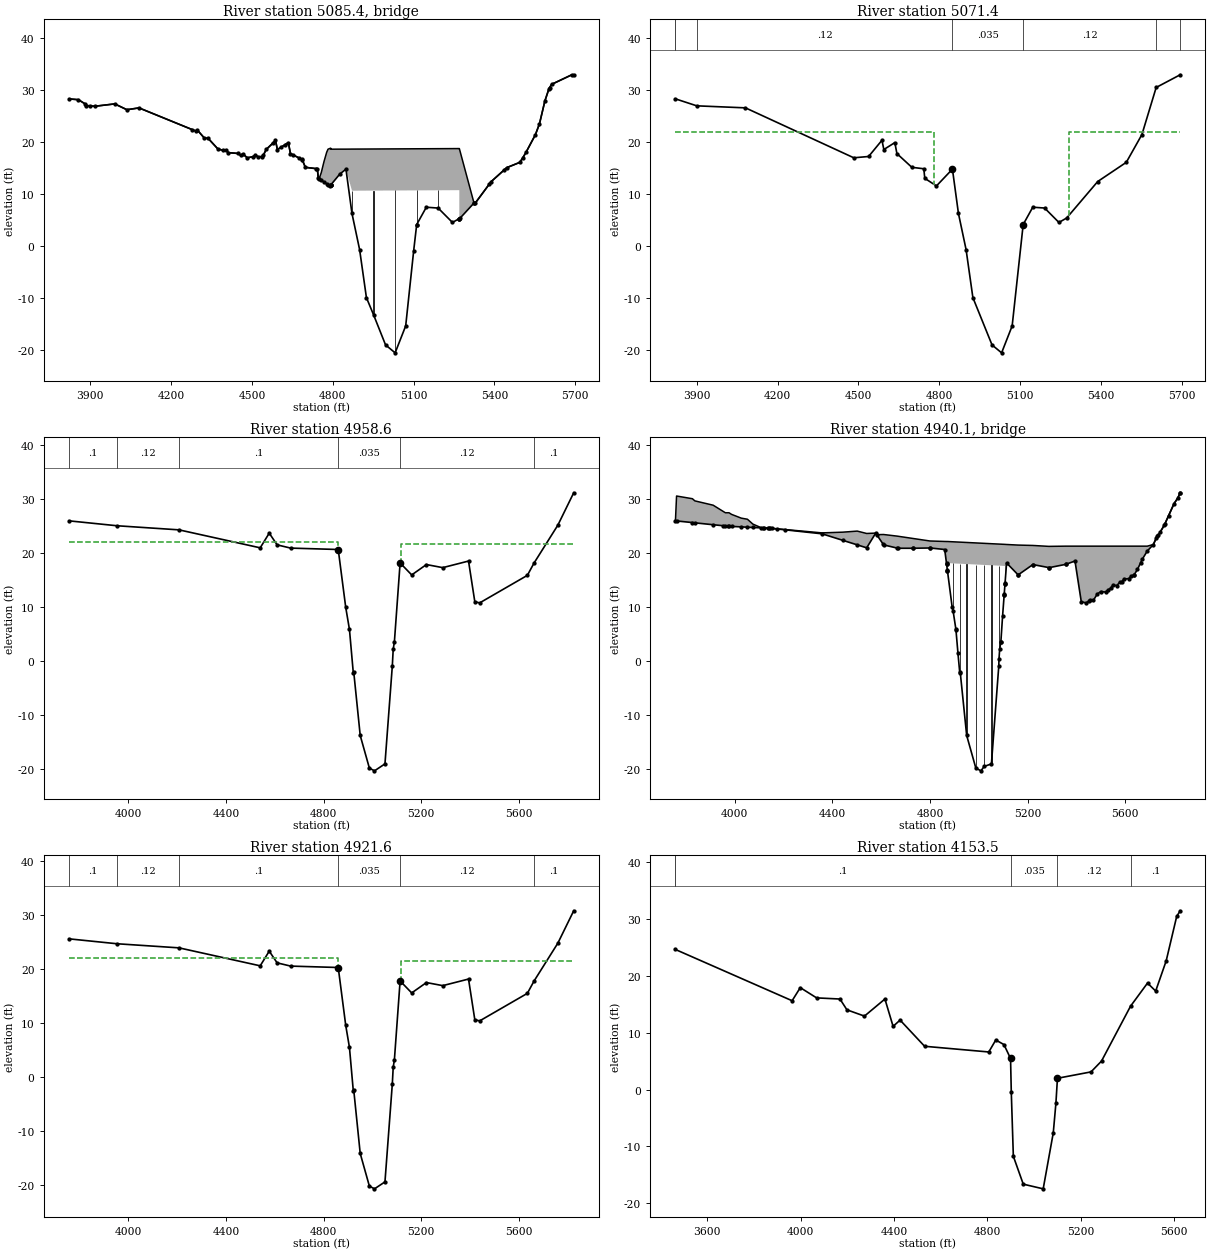
Type RM Length L Ch R = 3 ,5085.4  ,,,
BEGIN DESCRIPTION:
PIPELINE
END DESCRIPTION:
Bridge Culvert--1,0,-1,-1, 0
Deck Dist Width WeirC Skew NumUp NumDn MinLoCord MaxHiCord MaxSubmerge Is_Ogee
10,8,2.6,0, 60, 60, , , 0.95, 0, 1,1,,
  3820.8  3855.8  3880.8  3885.8  3915.8  3990.8  4035.8  4080.8  4292.8  4297.8
  4322.8  4337.8  4372.8  4392.8  4402.8  4412.8  4447.8  4457.8  4467.8  4482.8
  4502.8  4512.8  4522.8  4537.8  4542.8  4552.8 4587.36 4594.36 4635.16 4642.86
 4686.36 4698.26 4742.66 4746.36  4749.2  4757.3  4767.3  4777.3  4782.3 4789.66
  4792.2 4792.26 4825.76 4848.96 4871.26 5269.65 5269.76 5323.86 5328.46 5388.26
 5445.76 5494.36  5517.3  5552.3  5567.3  5587.3  5602.3  5612.3  5687.3  5694.3
   28.27   28.12   27.31      27   26.85   27.31   26.19   26.54   22.06   22.25
   20.77   20.66   18.69   18.36   18.39   17.94   17.78   17.46   17.62   16.94
   17.15   17.41   17.14   17.19   17.48   18.55   20.31   18.53   19.87   17.76
   16.62   15.12   14.84      13    12.9    14.1    16.2      18    18.6   18.75
    18.8    18.6   18.61   18.61   18.62   18.72   18.72    8.32    8.21   12.38
   15.05   16.07      18   21.41    23.5   27.87   30.21   31.07   32.91    32.9
   28.27   28.12   27.31      27   26.85   27.31   26.19   26.54   22.06   22.25
   20.77   20.66   18.69   18.36   18.39   17.94   17.78   17.46   17.62   16.94
   17.15   17.41   17.14   17.19   17.48   18.55   20.31   18.53   19.86   17.75
   16.61   15.11   14.83   12.99   12.89   12.62   12.28   11.95   11.78   11.53
   11.69   11.69    13.8   14.76   10.62   10.72    5.27    8.23    8.21   12.38
   15.05   16.07      18   21.41    23.5   27.87   30.21   31.07   32.91    32.9
  3820.8  3855.8  3880.8  3885.8  3915.8  3990.8  4035.8  4080.8  4292.8  4297.8
  4322.8  4337.8  4372.8  4392.8  4402.8  4412.8  4447.8  4457.8  4467.8  4482.8
  4502.8  4512.8  4522.8  4537.8  4542.8  4552.8 4587.36 4594.36 4635.16 4642.86
 4686.36 4698.26 4742.66 4746.36  4749.2  4757.3  4767.3  4777.3  4782.3 4789.66
  4792.2 4792.26 4825.76 4848.96 4871.26 5269.65 5269.76 5323.86 5328.46 5388.26
 5445.76 5494.36  5517.3  5552.3  5567.3  5587.3  5602.3  5612.3  5687.3  5694.3
   28.27   28.12   27.31      27   26.85   27.31   26.19   26.54   22.06   22.25
   20.77   20.66   18.69   18.36   18.39   17.94   17.78   17.46   17.62   16.94
   17.15   17.41   17.14   17.19   17.48   18.55   20.31   18.53   19.87   17.76
   16.62   15.12   14.84      13    12.9    14.1    16.2      18    18.6   18.75
    18.8    18.6   18.61   18.61   18.62   18.72   18.72    8.32    8.21   12.38
   15.05   16.07      18   21.41    23.5   27.87   30.21   31.07   32.91    32.9
   28.27   28.12   27.31      27   26.85   27.31   26.19   26.54   22.06   22.25
   20.77   20.66   18.69   18.36   18.39   17.94   17.78   17.46   17.62   16.94
   17.15   17.41   17.14   17.19   17.48   18.55   20.31   18.53   19.86   17.75
   16.61   15.11   14.83   12.99   12.89   12.62   12.28   11.95   11.78   11.53
   11.69   11.69    13.8   14.76   10.62   10.72    5.27    8.23    8.21   12.38
   15.05   16.07      18   21.41    23.5   27.87   30.21   31.07   32.91    32.9
Pier Skew, UpSta & Num, DnSta & Num=  ,4871.3, 2 ,4871.3, 2 , 0 , 0 , 0 ,,
     1.4     1.4
    5.07   11.75
     1.4     1.4
    5.07   11.75
Pier Skew, UpSta & Num, DnSta & Num=  ,4951.3, 2 ,4951.3, 2 , 0 , 0 , 0 ,,
     1.4     1.4
  -14.32   11.64
     1.4     1.4
  -14.32   11.64
Pier Skew, UpSta & Num, DnSta & Num=  ,5031.5, 2 ,5031.5, 2 , 0 , 0 , 0 ,,
     1.4     1.4
  -21.53   11.66
     1.4     1.4
  -21.53   11.66
Pier Skew, UpSta & Num, DnSta & Num=  ,5111.5, 2 ,5111.5, 2 , 0 , 0 , 0 ,,
     1.4     1.4
    2.79   11.68
     1.4     1.4
    2.79   11.68
Pier Skew, UpSta & Num, DnSta & Num=  ,5191.1, 2 ,5191.1, 2 , 0 , 0 , 0 ,,
     1.4     1.4
    6.24    11.7
     1.4     1.4
    6.24    11.7
BR Coef= 1 , 1 , 0 ,1.25, 0 ,,,0.8,0,2,0,
WSPro=,,,, 1 ,,,, 0 ,,,, 0 ,,,,-1 ,-1 ,-1 , 0 , 0 , 0 , 0 , 0
BR U #Sta/Elev= 90
  3820.8   28.27  3855.8   28.12  3880.8   27.31  3885.8      27    3900   26.93
  3915.8   26.85  3990.8   27.31  4035.8   26.19  4080.8   26.54  4277.8   22.38
  4292.8   22.06  4297.8   22.25  4322.8   20.77  4337.8   20.66  4372.8   18.69
  4392.8   18.36  4402.8   18.39  4412.8   17.94  4447.8   17.78  4457.8   17.46
  4467.8   17.62  4482.8   16.94  4502.8   17.15  4512.8   17.41  4522.8   17.14
  4537.8   17.19  4542.8   17.48  4552.8   18.55  4577.8   19.73 4587.36   20.31
 4594.36   18.53  4609.2   19.01  4624.2    19.5 4635.16   19.86 4642.86   17.75
  4654.2   17.45  4674.2   16.93  4684.2   16.67 4686.36   16.61 4698.26   15.11
  4739.2   14.85 4742.66   14.83 4746.36   12.99  4749.2   12.89  4757.3   12.62
  4767.3   12.28  4777.3   11.95  4782.3   11.78 4789.66   11.53  4792.2   11.69
 4792.26   11.69 4792.37    11.7 4792.46   11.71 4825.76    13.8 4848.96   14.76
 4871.26    6.24 4899.66    -.72 4924.86   -9.94 4951.26  -13.23 4995.96  -19.04
 5031.46  -20.56 5070.66  -15.38 5100.36    -.89 5111.46    4.11 5111.56    4.11
 5147.16    7.44 5191.06    7.28 5244.26    4.51 5269.65    5.26 5269.76    5.27
 5269.86    5.27 5272.86    5.36 5323.86    8.23 5324.46    8.26 5328.46    8.21
 5380.16   11.83 5388.26   12.38 5436.86   14.65 5445.76   15.05 5494.36   16.07
 5505.56   16.92  5517.3      18  5552.3   21.41  5567.3    23.5  5587.3   27.87
  5602.3   30.21  5605.2   30.46  5612.3   31.07  5687.3   32.91  5694.3    32.9
BR U #Mann= 7
  3820.8      .2  3820.8      .1    3900     .12 4848.96    .035 5111.56     .12
  5605.2      .1  5694.3      .2
BR U Banks=4848.96,5111.56
BR D #Sta/Elev= 90
  3820.8   28.27  3855.8   28.12  3880.8   27.31  3885.8      27    3900   26.93
  3915.8   26.85  3990.8   27.31  4035.8   26.19  4080.8   26.54  4277.8   22.38
  4292.8   22.06  4297.8   22.25  4322.8   20.77  4337.8   20.66  4372.8   18.69
  4392.8   18.36  4402.8   18.39  4412.8   17.94  4447.8   17.78  4457.8   17.46
  4467.8   17.62  4482.8   16.94  4502.8   17.15  4512.8   17.41  4522.8   17.14
  4537.8   17.19  4542.8   17.48  4552.8   18.55  4577.8   19.73 4587.36   20.31
 4594.36   18.53  4609.2   19.01  4624.2    19.5 4635.16   19.86 4642.86   17.75
  4654.2   17.45  4674.2   16.93  4684.2   16.67 4686.36   16.61 4698.26   15.11
  4739.2   14.85 4742.66   14.83 4746.36   12.99  4749.2   12.89  4757.3   12.62
  4767.3   12.28  4777.3   11.95  4782.3   11.78 4789.66   11.53  4792.2   11.69
 4792.26   11.69 4792.37    11.7 4792.46   11.71 4825.76    13.8 4848.96   14.76
 4871.26    6.24 4899.66    -.72 4924.86   -9.94 4951.26  -13.23 4995.96  -19.04
 5031.46  -20.56 5070.66  -15.38 5100.36    -.89 5111.46    4.11 5111.56    4.11
 5147.16    7.44 5191.06    7.28 5244.26    4.51 5269.65    5.26 5269.76    5.27
 5269.86    5.27 5272.86    5.36 5323.86    8.23 5324.46    8.26 5328.46    8.21
 5380.16   11.83 5388.26   12.38 5436.86   14.65 5445.76   15.05 5494.36   16.07
 5505.56   16.92  5517.3      18  5552.3   21.41  5567.3    23.5  5587.3   27.87
  5602.3   30.21  5605.2   30.46  5612.3   31.07  5687.3   32.91  5694.3    32.9
BR D #Mann= 7
  3820.8      .2  3820.8      .1    3900     .12 4848.96    .035 5111.56     .12
  5605.2      .1  5694.3      .2
BR D Banks=4848.96,5111.56
BC Design=,, 0 ,, 0 ,,,,,,
BC HTab HWMax=32.97
BC Use User HTab Curves=0
BC User HTab FreeFlow(D)= 0

Type RM Length L Ch R = 1 ,5071.4  ,112.8,112.8,112.8
BEGIN DESCRIPTION:
Downstream Section of Bridge/Culvert/Weir
END DESCRIPTION:
XS GIS Cut Line= 5
      3155842.12     13825845.76      3156309.81     13825816.98
      3156758.17     13825682.94      3157249.01     13825520.41
      3157609.09      13825304.4
#Sta/Elev= 30
  3820.8   28.28    3900   26.94  4080.8   26.55  4482.8   16.95  4537.8    17.2
 4587.36   20.32 4594.36   18.54 4635.16   19.87 4642.86   17.76 4698.26   15.12
 4742.66   14.84 4746.36      13 4789.66   11.54 4848.96   14.77 4871.26    6.25
 4899.66    -.71 4924.86   -9.93 4995.96  -19.03 5031.46  -20.55 5070.66  -15.37
 5111.56    4.12 5147.16    7.45 5191.06    7.29 5244.26    4.52 5272.86    5.37
 5388.26   12.39 5494.36   16.08  5552.3   21.42  5605.2   30.47  5694.3   32.91
#Mann= 7 , 1 , 0
  3820.8      .2       0  3820.8      .1       0    3900     .12       0
 4848.96    .035       0 5111.56     .12       0  5605.2      .1       0
  5694.3      .2       0
#XS Ineff= 2 , 0
       0    4782      22    5280       0      22
Permanent Ineff=
       F       F
Bank Sta=4848.96,5111.56
XS Rating Curve= 0 ,0
Exp/Cntr=0.5,0.3

Type RM Length L Ch R = 1 ,4958.6  ,37,37,37
BEGIN DESCRIPTION:
Upstream Section of Bridge/Culvert/Weir
END DESCRIPTION:
XS GIS Cut Line= 6
      3155829.99     13826174.75      3156122.44      13826051.3
      3156205.69     13826000.07      3156455.45     13825897.61
      3156743.62     13825795.15      3157763.06      13825445.7
#Sta/Elev= 30
  3756.5   25.89  3953.5   24.98  4207.6   24.22  4540.3   20.89  4577.3   23.61
  4609.6   21.44  4665.2   20.84  4860.1   20.58  4890.8    9.86  4906.1    5.76
  4921.8   -2.27  4923.8   -2.19  4950.2  -13.88  4987.7  -19.92  5008.7  -20.43
  5051.6  -19.14  5081.7   -1.03  5085.4    2.09  5090.3    3.49  5113.7   18.09
  5161.2   15.87  5221.5   17.79  5288.5   17.22  5394.1   18.44  5419.9   10.89
  5439.9   10.69  5635.2   15.79  5662.6   18.07  5760.2   25.09  5825.2   31.09
#Mann= 6 , 1 , 0
  3756.5      .1       0  3953.5     .12       0  4207.6      .1       0
  4860.1    .035       0  5113.7     .12       0  5662.6      .1       0
#XS Ineff= 2 , 0
       0    4858   22.02    5117       0   21.59
Permanent Ineff=
       F       F
Bank Sta=4860.1,5113.7
XS Rating Curve= 0 ,0
Exp/Cntr=0.5,0.3

Type RM Length L Ch R = 3 ,4940.1  ,,,
BEGIN DESCRIPTION:
RAILROAD EAST OF CENTRAL STREET
Structure ID: C00-1
END DESCRIPTION:
Bridge Culvert--1,0,-1,-1, 0
Deck Dist Width WeirC Skew NumUp NumDn MinLoCord MaxHiCord MaxSubmerge Is_Ogee
10,17,2.6,0, 60, 60, , , 0.95, 0, 1,1,,
  3756.5  3761.1  3826.1  3836.1  3911.1  3961.1  3976.1  3986.5  4026.5  4051.5
  4073.9  4108.9  4152.2  4357.2  4441.6  4501.6  4540.3  4577.3  4581.6  4609.6
  4665.2  4799.3  4860.1 4867.61  4867.7 4871.41 5107.19  5107.3  5113.7  5161.2
  5221.5  5286.9  5355.4  5394.1  5419.9  5439.9  5454.9  5469.9  5484.9  5499.9
  5519.9  5539.9  5549.9  5564.9  5579.9  5584.9  5594.9  5614.9  5624.9  5635.2
  5650.2  5670.2  5690.2  5715.2  5730.2  5735.2  5760.2  5800.2  5815.2  5825.2
    25.9    30.5      30    29.6    28.8    27.4    27.4    27.1    26.4    26.2
    25.3   24.61   24.51   23.67    23.8      24   23.56   23.63   23.34   23.37
   23.07   22.17   22.08   22.07   22.07   22.07   21.54   21.54   21.52   21.41
   21.34   21.17   21.21   21.21   21.21   21.21   21.21   21.21   21.21   21.21
   21.21   21.21   21.21   21.21   21.21   21.21   21.21   21.21   21.21   21.21
   21.21   21.21   21.21   21.51   23.01   23.21   25.11   29.11   30.11    31.1
    25.9   25.88   25.58   25.53   25.18   24.95   24.89   24.87   24.78   24.72
   24.67    24.6    24.5    23.5    22.3   21.45    20.9   23.62   23.33   21.45
   20.85   20.87   20.59   17.97   18.07   18.07   17.54   14.25    18.1   15.88
    17.8   17.24   17.83   18.45    10.9    10.7    11.2    11.2    12.3    12.8
    12.7    13.4      14    13.9    14.6    14.6    15.1    15.2    15.7    15.8
    16.9    18.8    20.3    21.5      23    23.2    25.1    29.1    30.1    31.1
  3756.5  3761.1  3826.1  3836.1  3911.1  3961.1  3976.1  3986.5  4026.5  4051.5
  4073.9  4108.9  4152.2  4357.2  4441.6  4501.6  4540.3  4577.3  4581.6  4609.6
  4665.2  4799.3  4860.1 4867.61  4867.7 4871.41 5107.19  5107.3  5113.7  5161.2
  5221.5  5286.9  5355.4  5394.1  5419.9  5439.9  5454.9  5469.9  5484.9  5499.9
  5519.9  5539.9  5549.9  5564.9  5579.9  5584.9  5594.9  5614.9  5624.9  5635.2
  5650.2  5670.2  5690.2  5715.2  5730.2  5735.2  5760.2  5800.2  5815.2  5825.2
    25.9    30.5      30    29.6    28.8    27.4    27.4    27.1    26.4    26.2
    25.3   24.61   24.51   23.67    23.8      24   23.56   23.63   23.34   23.37
   23.07   22.17   22.08   22.07   22.07   22.07   21.54   21.54   21.52   21.41
   21.34   21.17   21.21   21.21   21.21   21.21   21.21   21.21   21.21   21.21
   21.21   21.21   21.21   21.21   21.21   21.21   21.21   21.21   21.21   21.21
   21.21   21.21   21.21   21.51   23.01   23.21   25.11   29.11   30.11    31.1
   25.58   25.56   25.26   25.21   24.86   24.63   24.57   24.55   24.46    24.4
   24.35   24.28   24.18   23.18   21.98   21.13   20.58    23.3   23.01   21.13
   20.53   20.55   20.27   17.65   17.75   17.75   17.22   13.93   17.78   15.56
   17.48   16.92   17.51   18.13   10.58   10.38   10.88   10.88   11.98   12.48
   12.38   13.08   13.68   13.58   14.28   14.28   14.78   14.88   15.38   15.48
   16.58   18.48   19.98   21.18   22.68   22.88   24.78   28.78   29.78   30.78
Pier Skew, UpSta & Num, DnSta & Num=  ,4894.6, 2 ,4894.6, 2 , 0 , 0 , 0 ,,
       2       2
    7.88   19.02
       2       2
    7.56    18.7
Pier Skew, UpSta & Num, DnSta & Num=  ,4923.8, 2 ,4923.8, 2 , 0 , 0 , 0 ,,
       2       2
   -3.62   18.96
       2       2
   -3.94   18.63
Pier Skew, UpSta & Num, DnSta & Num=  ,4950.2, 2 ,4950.2, 2 , 0 , 0 , 0 ,,
       2       2
  -15.03   18.89
       2       2
  -15.35   18.57
Pier Skew, UpSta & Num, DnSta & Num=  ,4987.7, 2 ,4987.7, 2 , 0 , 0 , 0 ,,
       2       2
  -20.93   18.81
       2       2
  -21.25   18.49
Pier Skew, UpSta & Num, DnSta & Num=  ,5021.7, 2 ,5021.7, 2 , 0 , 0 , 0 ,,
       2       2
  -20.67   18.73
       2       2
  -20.99   18.41
Pier Skew, UpSta & Num, DnSta & Num=  ,5051.6, 2 ,5051.6, 2 , 0 , 0 , 0 ,,
       2       2
  -20.15   18.67
       2       2
  -20.47   18.35
Pier Skew, UpSta & Num, DnSta & Num=  ,5082.6, 2 ,5082.6, 2 , 0 , 0 , 0 ,,
       2       2
   -2.08    18.6
       2       2
    -2.4   18.28
Abutment Skew #Up #Dn= , 2 , 2
  4867.5  4906.2
   18.07    5.72
  4867.5  4906.2
   17.75     5.4
Abutment Skew #Up #Dn= , 2 , 2
  5090.3 5107.39
     3.5   17.54
  5090.3 5107.39
    3.18   17.22
BR Coef= 1 , 1 , 0 ,1.25, 0 ,,,0.8,0,2,0,
WSPro=,,,, 1 ,,,, 0 ,,,, 0 ,,,,-1 ,-1 ,-1 , 0 , 0 , 0 , 0 , 0
BR U #Sta/Elev= 112
  3756.5    25.9  3761.1   25.88  3826.1   25.58  3836.1   25.53  3911.1   25.18
  3953.5   24.99  3961.1   24.95  3972.2    24.9  3976.1   24.89  3986.5   24.87
  4026.5   24.78  4051.5   24.72  4073.9   24.67  4108.9    24.6  4113.9   24.59
  4118.9   24.57  4133.9   24.54  4138.9   24.53  4143.9   24.52  4152.2    24.5
  4171.7    24.4  4207.6   24.23  4357.2    23.5  4441.6    22.3  4501.6   21.45
  4540.3    20.9  4577.3   23.62  4581.6   23.33  4608.6   21.52  4609.6   21.45
  4665.2   20.85  4668.4   20.82  4728.3   20.82  4728.8   20.82  4799.3   20.87
  4800.3   20.87  4860.1   20.59  4867.5   18.01 4867.61   17.97  4867.7   17.94
 4871.19   16.72  4871.3   16.68 4871.41   16.64  4890.8    9.87  4894.6    9.18
  4906.1    5.77  4906.2    5.72  4914.5    1.33  4921.8   -2.26  4923.8   -2.18
  4950.2  -13.87  4987.7  -19.91  5008.7  -20.42  5021.7  -19.61  5051.6  -19.13
  5081.7   -1.02  5082.6      .3  5085.4     2.1  5090.2    3.47  5090.3     3.5
  5097.4     8.3 5103.79   12.14  5103.9   12.21 5104.01   12.27 5107.19   14.19
  5107.3   14.25  5107.4   14.31  5113.7    18.1  5161.2   15.88  5162.3   15.92
  5221.5    17.8  5222.1   17.79  5286.9   17.24  5288.5   17.23  5355.4   17.83
    5356   17.84  5394.1   18.45  5419.9    10.9  5439.9    10.7  5449.9      11
  5454.9    11.2  5469.9    11.2  5484.9    12.3  5499.9    12.8  5519.9    12.7
  5529.9    13.1  5539.9    13.4  5549.9      14  5564.9    13.9  5579.9    14.6
  5584.9    14.6  5594.9    15.1  5614.9    15.2  5624.9    15.7  5634.9    15.8
  5635.2    15.8  5650.2    16.9  5662.6   18.08  5670.2    18.8  5690.2    20.3
  5715.2    21.5  5727.4   22.72  5730.2      23  5735.2    23.2  5742.4   23.75
  5760.2    25.1  5762.4   25.32  5777.4   26.82  5800.2    29.1  5815.2    30.1
  5823.9   30.97  5825.2    31.1
BR U #Mann= 6
  3756.5      .1  3953.5     .12  4207.6      .1  4860.1    .035  5113.7     .12
  5662.6      .1
BR U Banks=4860.1,5113.7
BR D #Sta/Elev= 112
  3756.5   25.58  3761.1   25.56  3826.1   25.26  3836.1   25.21  3911.1   24.86
  3953.5   24.67  3961.1   24.63  3972.2   24.58  3976.1   24.57  3986.5   24.55
  4026.5   24.46  4051.5    24.4  4073.9   24.35  4108.9   24.28  4113.9   24.27
  4118.9   24.25  4133.9   24.22  4138.9   24.21  4143.9    24.2  4152.2   24.18
  4171.7   24.08  4207.6   23.91  4357.2   23.18  4441.6   21.98  4501.6   21.13
  4540.3   20.58  4577.3    23.3  4581.6   23.01  4608.6    21.2  4609.6   21.13
  4665.2   20.53  4668.4    20.5  4728.3    20.5  4728.8    20.5  4799.3   20.55
  4800.3   20.55  4860.1   20.27  4867.5   17.69 4867.61   17.65  4867.7   17.62
 4871.19    16.4  4871.3   16.36 4871.41   16.32  4890.8    9.55  4894.6    8.86
  4906.1    5.45  4906.2     5.4  4914.5    1.01  4921.8   -2.58  4923.8    -2.5
  4950.2  -14.19  4987.7  -20.23  5008.7  -20.74  5021.7  -19.93  5051.6  -19.45
  5081.7   -1.34  5082.6    -.02  5085.4    1.78  5090.2    3.15  5090.3    3.18
  5097.4    7.98 5103.79   11.82  5103.9   11.89 5104.01   11.95 5107.19   13.87
  5107.3   13.93  5107.4   13.99  5113.7   17.78  5161.2   15.56  5162.3    15.6
  5221.5   17.48  5222.1   17.47  5286.9   16.92  5288.5   16.91  5355.4   17.51
    5356   17.52  5394.1   18.13  5419.9   10.58  5439.9   10.38  5449.9   10.68
  5454.9   10.88  5469.9   10.88  5484.9   11.98  5499.9   12.48  5519.9   12.38
  5529.9   12.78  5539.9   13.08  5549.9   13.68  5564.9   13.58  5579.9   14.28
  5584.9   14.28  5594.9   14.78  5614.9   14.88  5624.9   15.38  5634.9   15.48
  5635.2   15.48  5650.2   16.58  5662.6   17.76  5670.2   18.48  5690.2   19.98
  5715.2   21.18  5727.4    22.4  5730.2   22.68  5735.2   22.88  5742.4   23.43
  5760.2   24.78  5762.4      25  5777.4    26.5  5800.2   28.78  5815.2   29.78
  5823.9   30.65  5825.2   30.78
BR D #Mann= 6
  3756.5      .1  3953.5     .12  4207.6      .1  4860.1    .035  5113.7     .12
  5662.6      .1
BR D Banks=4860.1,5113.7
BC Design=,, 0 ,, 0 ,,,,,,
BC HTab HWMax=31.09
BC Use User HTab Curves=0
BC User HTab FreeFlow(D)= 0

Type RM Length L Ch R = 1 ,4921.6  ,768.1,768.1,768.1
BEGIN DESCRIPTION:
Downstream Section of Bridge/Culvert/Weir
END DESCRIPTION:
XS GIS Cut Line= 6
      3155828.03      13826211.7      3156120.48     13826088.24
      3156203.73     13826037.01      3156453.49     13825934.55
      3156741.66     13825832.09       3157761.1     13825482.65
#Sta/Elev= 30
  3756.5   25.62  3953.5   24.71  4207.6   23.95  4540.3   20.62  4577.3   23.34
  4609.6   21.17  4665.2   20.57  4860.1   20.31  4890.8    9.59  4906.1    5.49
  4921.8   -2.54  4923.8   -2.46  4950.2  -14.15  4987.7  -20.19  5008.7   -20.7
  5051.6  -19.41  5081.7    -1.3  5085.4    1.82  5090.3    3.22  5113.7   17.82
  5161.2    15.6  5221.5   17.52  5288.5   16.95  5394.1   18.17  5419.9   10.62
  5439.9   10.42  5635.2   15.52  5662.6    17.8  5760.2   24.82  5825.2   30.82
#Mann= 6 , 1 , 0
  3756.5      .1       0  3953.5     .12       0  4207.6      .1       0
  4860.1    .035       0  5113.7     .12       0  5662.6      .1       0
#XS Ineff= 2 , 0
       0    4858   22.02    5117       0   21.59
Permanent Ineff=
       F       F
Bank Sta=4860.1,5113.7
XS Rating Curve= 0 ,0
Exp/Cntr=0.5,0.3

Type RM Length L Ch R = 1 ,4153.5  ,316.8,294.3,287.2
BEGIN DESCRIPTION:
Cross Section 4153.5-Interpolated
END DESCRIPTION:
XS GIS Cut Line= 5
      3156784.73     13827117.61      3157453.13     13826588.09
      3157670.14     13825945.73      3157763.99     13825554.71
      3157817.66     13825331.09
#Sta/Elev= 30
  3463.9    24.6  3963.9    15.6  3998.9    17.9  4068.9    16.1  4168.9    15.9
  4198.9      14  4273.9    12.9  4361.6    15.9  4396.6    11.1  4426.6    12.2
  4531.6     7.6  4806.6     6.6  4836.6     8.7  4871.6     7.9  4899.9    5.46
  4903.1    -.49  4911.9  -11.72  4954.4  -16.62  5039.8  -17.44    5083    -7.6
  5094.3    -2.4  5100.9    1.98  5244.7     3.1  5289.7       5  5414.1   14.64
  5486.8    18.7  5521.8    17.3  5566.8    22.6  5611.8    30.4  5626.8    31.4
#Mann= 5 , 1 , 0
  3463.9      .2       0  3463.9      .1       0  4899.9    .035       0
  5100.9     .12       0  5414.1      .1       0
Bank Sta=4899.9,5100.9
XS Rating Curve= 0 ,0
Exp/Cntr=0.3,0.1