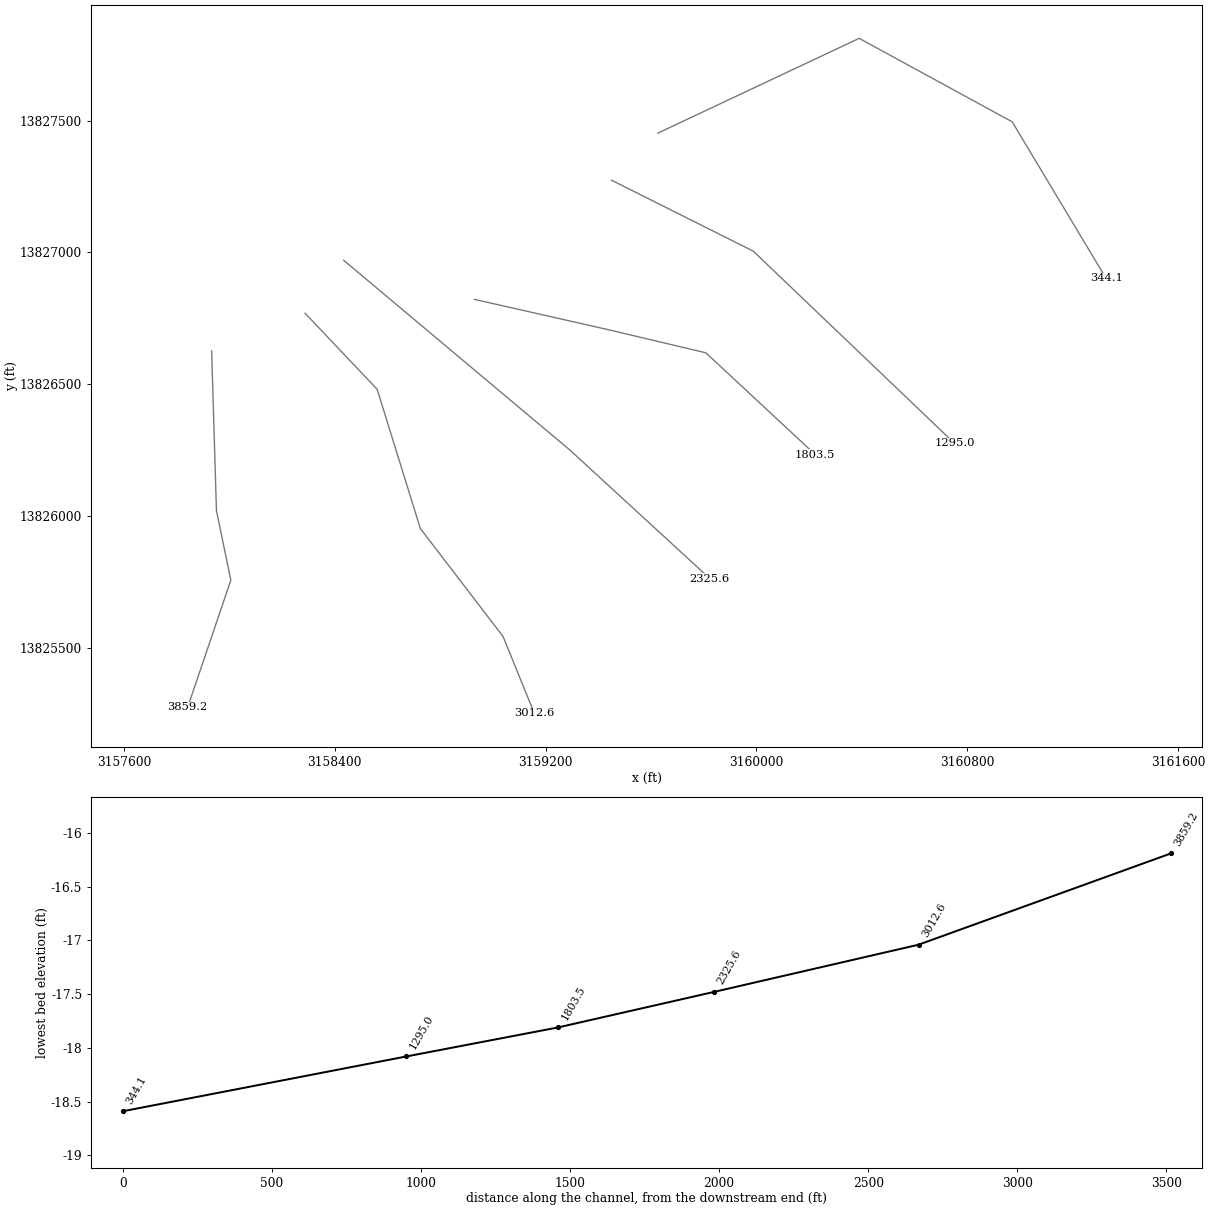
HEC-RAS study C100-00-00.prj: C100-00-00

--- C100-00-00.g01 (geometry) --- (continued)

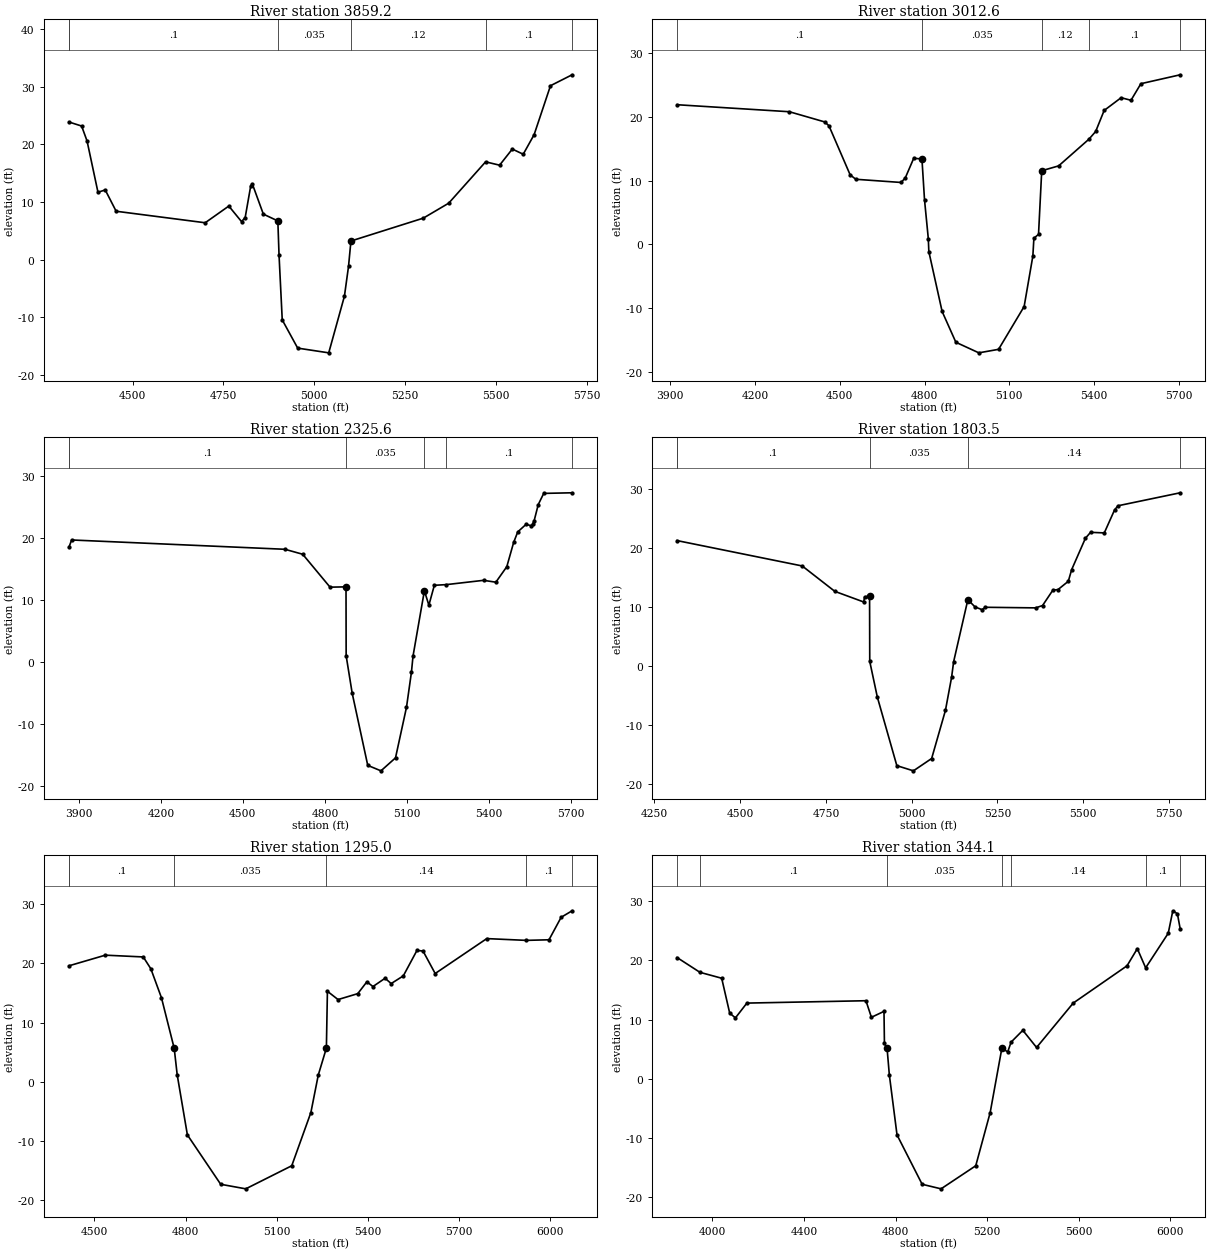
Type RM Length L Ch R = 1 ,3859.2  ,756.2,846.6,961.1
BEGIN DESCRIPTION:
Cross Section 3859.2
END DESCRIPTION:
XS GIS Cut Line= 4
      3157933.13     13826626.43      3157951.34     13826021.19
      3158005.94     13825757.26      3157842.12     13825274.89
#Sta/Elev= 30
  4324.9    23.9  4359.9    23.2  4374.9    20.6  4404.9    11.7  4424.9    12.1
  4454.9     8.4  4699.9     6.4  4764.9     9.3  4799.9     6.6  4809.9     7.3
  4824.9    12.7  4829.9    13.1  4859.9     7.9  4899.8    6.72  4903.1     .76
  4911.9  -10.47  4954.4  -15.37  5039.8  -16.19    5083   -6.35  5094.3   -1.15
  5100.9    3.23  5299.9     7.2  5369.9     9.8  5471.4   16.98  5509.9    16.4
  5544.9    19.2  5574.9    18.3  5604.9    21.7  5649.9    30.2  5709.4    32.1
#Mann= 6 , 1 , 0
  4324.9      .2       0  4324.9      .1       0  4899.8    .035       0
  5100.9     .12       0  5471.4      .1       0  5709.4      .2       0
Bank Sta=4899.8,5100.9
XS Rating Curve= 0 ,0
Exp/Cntr=0.3,0.1

Type RM Length L Ch R = 1 ,3012.6  ,617.6,687,691.6
BEGIN DESCRIPTION:
Cross Section 3012.6
END DESCRIPTION:
XS GIS Cut Line= 5
      3158287.61     13826769.23      3158561.12     13826480.81
      3158724.95     13825952.93      3159038.94     13825543.38
      3159157.26     13825252.13
#Sta/Elev= 30
  3924.1    21.9  4321.6    20.8  4446.6    19.2  4461.6    18.6  4536.6    10.9
  4556.6    10.2  4716.6     9.7  4731.6    10.4  4761.6    13.5  4790.7   13.38
  4799.8    6.97  4813.2     .88  4815.1   -1.16  4862.1  -10.55  4910.7  -15.38
    4992  -17.04  5061.8  -16.49  5152.3   -9.77  5183.1   -1.86  5186.8     .94
  5203.2    1.56  5214.5   11.54  5274.3    12.3  5381.5   16.49  5405.4    17.7
  5435.4      21  5495.4      23  5530.4    22.6  5565.4    25.2  5704.7    26.6
#Mann= 5 , 1 , 0
  3924.1      .1       0  4790.7    .035       0  5214.5     .12       0
  5381.5      .1       0  5704.7      .2       0
Bank Sta=4790.7,5214.5
XS Rating Curve= 0 ,0
Exp/Cntr=0.3,0.1

Type RM Length L Ch R = 1 ,2325.6  ,459.9,522.1,602.6
BEGIN DESCRIPTION:
Cross Section 2325.6-Interpolated
END DESCRIPTION:
XS GIS Cut Line= 3
      3158434.03     13826970.04      3159293.41     13826249.55
      3159822.92     13825763.44
#Sta/Elev= 30
  3863.8    18.5  3873.8    19.7  4653.8    18.2  4718.8    17.4  4818.8    12.1
  4877.2   12.15  4877.7    1.06  4899.8   -4.98  4956.7   -16.6    5005  -17.48
  5058.2  -15.39  5098.4   -7.24  5116.4   -1.61  5122.3    1.01  5163.8   11.52
  5180.2     9.2  5200.2    12.4  5244.2   12.51  5380.2    13.2  5425.2    12.9
  5465.2    15.4  5490.2    19.3  5505.2      21  5535.2    22.2  5555.2      22
  5560.2    22.3  5565.2    22.8  5580.2    25.4  5600.2    27.2    5704    27.3
#Mann= 6 , 1 , 0
  3863.8      .2       0  3863.8      .1       0  4877.2    .035       0
  5163.8     .12       0  5244.2      .1       0    5704      .2       0
Bank Sta=4877.2,5163.8
XS Rating Curve= 0 ,0
Exp/Cntr=0.3,0.1

Type RM Length L Ch R = 1 ,1803.5  ,541.3,508.5,451.6
BEGIN DESCRIPTION:
Cross Section 1803.5
END DESCRIPTION:
XS GIS Cut Line= 4
      3158930.35      13826821.8      3159441.58     13826706.05
      3159808.12     13826619.23      3160222.89      13826233.4
#Sta/Elev= 30
  4315.8    21.2  4680.8    16.9  4775.8    12.6    4860    10.8  4862.7   11.66
  4877.2   11.82  4877.7     .73  4899.8   -5.31  4956.7  -16.93    5005  -17.81
  5058.2  -15.72  5098.4   -7.57  5116.4   -1.94  5122.3     .68  5163.8   11.19
  5184.7    9.96    5205     9.5    5215     9.9  5361.6     9.8  5381.6    10.2
  5411.6    12.8  5426.6    12.9  5456.6    14.3  5466.6    16.3  5506.6    21.6
  5521.6    22.6  5561.6    22.5  5591.6    26.4  5601.6    27.1  5783.1    29.3
#Mann= 5 , 1 , 0
  4315.8      .2       0  4315.8      .1       0  4877.2    .035       0
  5163.8     .14       0  5783.1      .2       0
Bank Sta=4877.2,5163.8
XS Rating Curve= 0 ,0
Exp/Cntr=0.3,0.1

Type RM Length L Ch R = 1 ,1295.0  ,932,950.9,1077.6
BEGIN DESCRIPTION:
Cross Section 1295.0-Interpolated
END DESCRIPTION:
XS GIS Cut Line= 3
      3159449.66     13827273.86      3159987.85     13827004.76
      3160751.74     13826275.59
#Sta/Elev= 30
  4415.8    19.6  4535.8    21.4  4660.8    21.1  4685.8    19.1  4720.8    14.2
  4762.8    5.65  4772.6    1.19  4806.2   -8.97  4915.9  -17.31  4998.5  -18.08
    5150  -14.18    5213   -5.19  5237.4    1.15  5264.1     5.7  5267.5    15.3
  5302.5    13.9  5367.5    14.9  5397.5    16.9  5417.5    16.1  5457.5    17.5
  5477.5    16.6  5517.5    17.9  5562.5    22.2  5582.5    22.1  5622.5    18.3
  5792.5    24.2  5922.4    23.9  5997.5      24  6037.5    27.8  6073.6    28.9
#Mann= 6 , 1 , 0
  4415.8      .2       0  4415.8      .1       0  4762.8    .035       0
  5264.1     .14       0  5922.4      .1       0  6073.6      .2       0
Bank Sta=4762.8,5264.1
XS Rating Curve= 0 ,0
Exp/Cntr=0.3,0.1

Type RM Length L Ch R = 1 ,344.1   ,0,0,0
BEGIN DESCRIPTION:
Cross Section 344.1
END DESCRIPTION:
XS GIS Cut Line= 4
      3159626.29     13827452.28      3160389.75     13827811.57
      3160970.36     13827494.87      3161326.64     13826901.07
#Sta/Elev= 30
  3845.5    20.5  3945.5      18  4040.5      17  4075.5    11.1  4100.5    10.3
  4150.5    12.8  4670.5    13.2  4694.3    10.4  4749.3    11.4  4751.2    5.98
  4762.8    5.14  4772.6     .68  4806.2   -9.48  4915.9  -17.82  4998.5  -18.59
    5150  -14.69    5213    -5.7  5264.1    5.19  5289.6    4.55  5304.3     6.2
  5355.6     8.2  5415.6     5.3  5575.6    12.8  5810.6    19.1  5855.6      22
    5892   18.76  5990.6    24.6  6010.6    28.4  6030.6    27.9  6043.1    25.3
#Mann= 7 , 1 , 0
  3845.5      .2       0  3945.5      .1       0  4762.8    .035       0
  5264.1      .1       0  5304.3     .14       0    5892      .1       0
  6043.1      .2       0
Bank Sta=4762.8,5264.1
XS Rating Curve= 0 ,0
Exp/Cntr=0.3,0.1

Chan Stop Cuts=-1
Use User Specified Reach Order=0
Composite Channel Slope=5